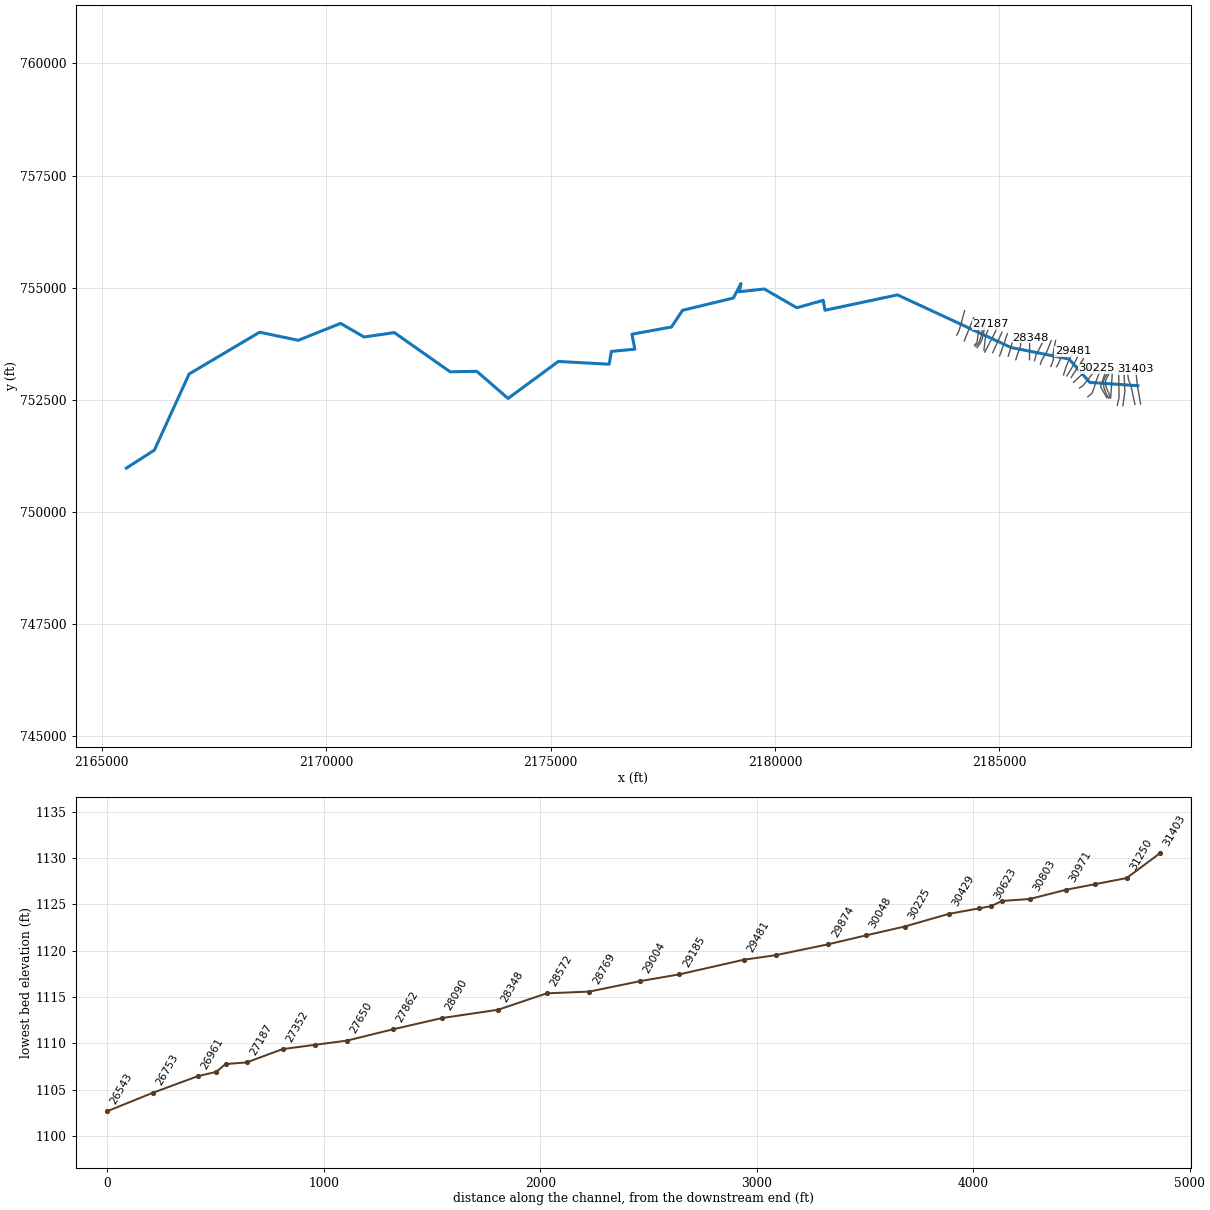
--- HACKERSCK.prj (project) ---

Proj Title=HACKERSCK
Current Plan=p01
Default Exp/Contr=0,0
English Units
Geom File=g01
Flow File=f01
Plan File=p01
BEGIN DESCRIPTION:
---------- MODELED AS PART OF WVEMD CTP PROGRAM, 2023----------
Stream Name: Hackers Creek
Flood Zone:  AFH
Upshur County, WV
HEC-RAS Version: RAS 6.3
Vertical Datum: NAVD88
Projection: NAD 1983 StatePlane West Virginia S FIPS 4702 (US Feet)
Terrain: 1-meter LIDAR (FEMA Region III 3DEP collected 2016-2018)
Land Use: 2019 NLCD
Hydrologic Method:
WV SIR2010-5033 regression equations
Additional Model Notes:
Model goes out of county into Lewis County
END DESCRIPTION:
DSS Export Rating Curves= 0
DSS Export Rating Curve Sorted= 0
DSS Export Volume Flow Curves= 0
DXF OffsetX= 0
DXF OffsetY= 0
DXF ScaleX= 0
DXF ScaleY= 0

--- HACKERSCK.p01 (plan) ---

Plan Title=Floodplain
Program Version=6.31
Short Identifier=Floodplain
Geom File=g01
Flow File=f01
Subcritical Flow
K Sum by GR= 0
Std Step Tol= 0.01
Critical Tol= 0.01
Num of Std Step Trials= 20
Max Error Tol= 0.3
Flow Tol Ratio= 0.001
Split Flow NTrial= 30
Split Flow Tol= 0.02
Split Flow Ratio= 0.02
Log Output Level= 0
Friction Slope Method= 1
Unsteady Friction Slope Method= 2
Unsteady Bridges Friction Slope Method= 1
Parabolic Critical Depth
Global Vel Dist= 0 , 0 , 0
Global Log Level= 0
CheckData=True
Encroach Param=-1 ,0,0, 0
Mapping Interval=1HOUR
Computation Time Step Use Courant=        0
Computation Time Step Use Time Series=    0
Computation Time Step Count To Double=0
Computation Time Step Max Doubling=0
Computation Time Step Max Halving=0
Computation Time Step Residence Courant=0
Run HTab= 0
Run UNet= 0
Run Sediment= 0
Run PostProcess= 0
Run WQNet= 0
Run RASMapper=-1
UNET Theta= 0
UNET Theta Warmup= 0
UNET ZTol= 0
UNET ZSATol= 0
UNET MxIter= 0
UNET Max Iter WO Improvement= 0
UNET MaxInSteps= 0
UNET DtIC= 0
UNET DtMin= 0
UNET MaxCRTS= 0
UNET WFStab= 0
UNET SFStab= 0
UNET WFX= 1
UNET SFX= 1
UNET Gravity=32.17405
UNET 1D Methodology=Finite Difference
UNET DSS MLevel= 1
UNET Pardiso=0
UNET DZMax Abort= 0
UNET Use Existing IB Tables= 0
UNET Froude Reduction=False
UNET Froude Limit= 0
UNET Froude Power= 0
UNET D1 Cores= 0
UNET WindReference=Eulerian
UNET WindDragFormulation=Hsu (1988)
UNET D2 Coriolis=0
UNET D2 Cores= 0
UNET D2 Theta= 1
UNET D2 Theta Warmup= 1
UNET D2 Z Tol= 0.01
UNET D2 Volume Tol= 0.01
UNET D2 Max Iterations= 20
UNET D2 Equation= 0
UNET D2 RampUpFraction=0.1
UNET D2 TimeSlices= 1
UNET D2 Turbulence Formulation=Non-Conservative (original)
UNET D2 Eddy Viscosity=0.3
UNET D2 Transverse Eddy Viscosity=0.1
UNET D2 Smagorinsky Mixing=0
UNET D2 BCVolumeCheck=0
UNET D2 Cores=0
UNET D2 SolverType=PARDISO (Direct)
UNET D2 Minimum Iterations= 3
UNET D2 Maximum Iterations= 30
UNET D2 Restart Number= 10
UNET D2 Relaxation Coeff=1.3
UNET D2 SOR Precondition Iterations= 10
UNET D2 ILUT Maximum Fill= 8
UNET D2 ILUT Tolerance=1E-08
UNET D2 Convergence Tolerance=0.00001
UNET D1D2 MaxIter= 0
UNET D1D2 ZTol=0.01
UNET D1D2 QTol=0.1
UNET D1D2 MinQTol=1
Write IC File= 0
Write IC File at Fixed DateTime=0
Write IC File at Sim End=0
Echo Input=False
Echo Parameters=False
Echo Output=False
Write Detailed= 0
HDF Write Warmup=0
HDF Write Time Slices=0
HDF Flush=0
HDF Compression= 1
HDF Chunk Size= 1
HDF Spatial Parts= 1
HDF Use Max Rows=0
HDF Fixed Rows= 1
Calibration Method= 0
Calibration Iterations= 20
Calibration Max Change=0.05
Calibration Tolerance=0.2
Calibration Maximum=1.5
Calibration Minimum=0.5
Calibration Optimization Method= 1
WQ AD Non Conservative
WQ ULTIMATE=-1
WQ Max Comp Step=1HOUR
WQ Output Interval=15MIN
WQ Output Selected Increments= 0
WQ Create Restart=0
WQ Fixed Restart=0
WQ System Summary=0
WQ Write To DSS=0
Sorting and Armoring Iterations= 10
XS Update Threshold= 0.02
Bed Roughness Predictor= 0
Hydraulics Update Threshold= 0.02
Energy Slope Method= 1
Volume Change Method= 1
Sediment Retention Method= 0
Sediment TS Multiplier= 1
Warm Up Method= 0
XS Weighting Method= 0
Number of US Weighted Cross Sections= 1
Number of DS Weighted Cross Sections= 1
Upstream XS Weight=0
Main XS Weight=1
Downstream XS Weight=0
Number of DS XS's Weighted with US Boundary= 1
Upstream Boundary Weight= 1
Weight of XSs Associated with US Boundary= 0
Number of US XS's Weighted with DS Boundary= 1
Downstream Boundary Weight= 0.5
Weight of XSs Associated with DS Boundary= 0.5
Percentile Method= 0
Sediment Output Level= 3
Mass or Volume Output= 0
Output Increment Type= 1
Profile and TS Output Increment= 1
Transport Output Increment 1
XS Output Flag= 0
XS Output Increment= 10
Read HDF5 Sediment Hotstart= 0
Sediment Hotstart Type= 0
Write Gradation File= 0
Read Gradation Hotstart= 0
Write HDF5 File= 1
Write Binary Output= 1
Write DSS Sediment File= 0
DSS Sediment Output Type= 1
SV Curve= 0
Specific Gage Flag= 0
Subcell Erosion Methods= 0
Subcell Deposition Methods= 0
Advection Scheme= 1
Matrix Solver= 0
Implicit Weighting Factor= 1
Maximum Outer Loop Convergence Iterations= 5
Convergence Maximum Absolute= 0.001
Convergence RMSE= 0.0001
Grain Fractions Max Abs Error= 0.001
Max Subgrid Regions= 1
Max Subgrid Length Scale= 3.402823E+38
Initial Layer Thickness= 3.402823E+38
Min Layer Thickness= 3.402823E+38
Max Layer Thickness= 3.402823E+38
Number of Layers= 5

--- HACKERSCK.f01 (steady flow) ---

Flow Title=Flows
Program Version=6.31
Number of Profiles= 1
Profile Names=01pct
River Rch & RM=HACKERSCK,Main,31403
     820
River Rch & RM=HACKERSCK,Main,30803
    1050
River Rch & RM=HACKERSCK,Main,27862
    1300
River Rch & RM=HACKERSCK,Main,25219
    1620
River Rch & RM=HACKERSCK,Main,21056
    2290
River Rch & RM=HACKERSCK,Main,12073
    2650
Boundary for River Rch & Prof#=HACKERSCK,Main            , 1
Up Type= 0
Dn Type= 3
Dn Slope=0.00238
DSS Import GetInterval= 0
DSS Import GetPeak= 0
DSS Import FillOption= 0

--- HACKERSCK.g01 (geometry) ---

Geom Title=Geometry
Program Version=6.31

River Reach=HACKERSCK       ,Main
Reach XY= 30
     2188082.813      752817.435     2187012.703      752891.637
     2186550.033      753411.654     2185256.315      753669.488
     2182727.142      754841.758     2181111.174       754498.79
     2181072.971      754720.453     2180483.359       754555.05
     2179758.792      754973.079     2179201.288      754911.754
     2179240.149      755093.296     2179070.225      754771.447
     2177937.788      754498.247      2177692.46      754126.062
     2176811.075      753965.381      2176875.09      753631.428
     2176352.755       753582.98     2176303.506      753296.387
      2175170.87      753358.485      2174050.51      752533.474
     2173354.273      753138.024      2172760.34      753127.465
     2171516.271      754001.037     2170842.326      753903.312
     2170319.534       754206.36     2169377.081      753829.768
     2168515.442      754009.565      2166943.63      753078.531
     2166170.272      751382.0942165546.23488196750980.969784418

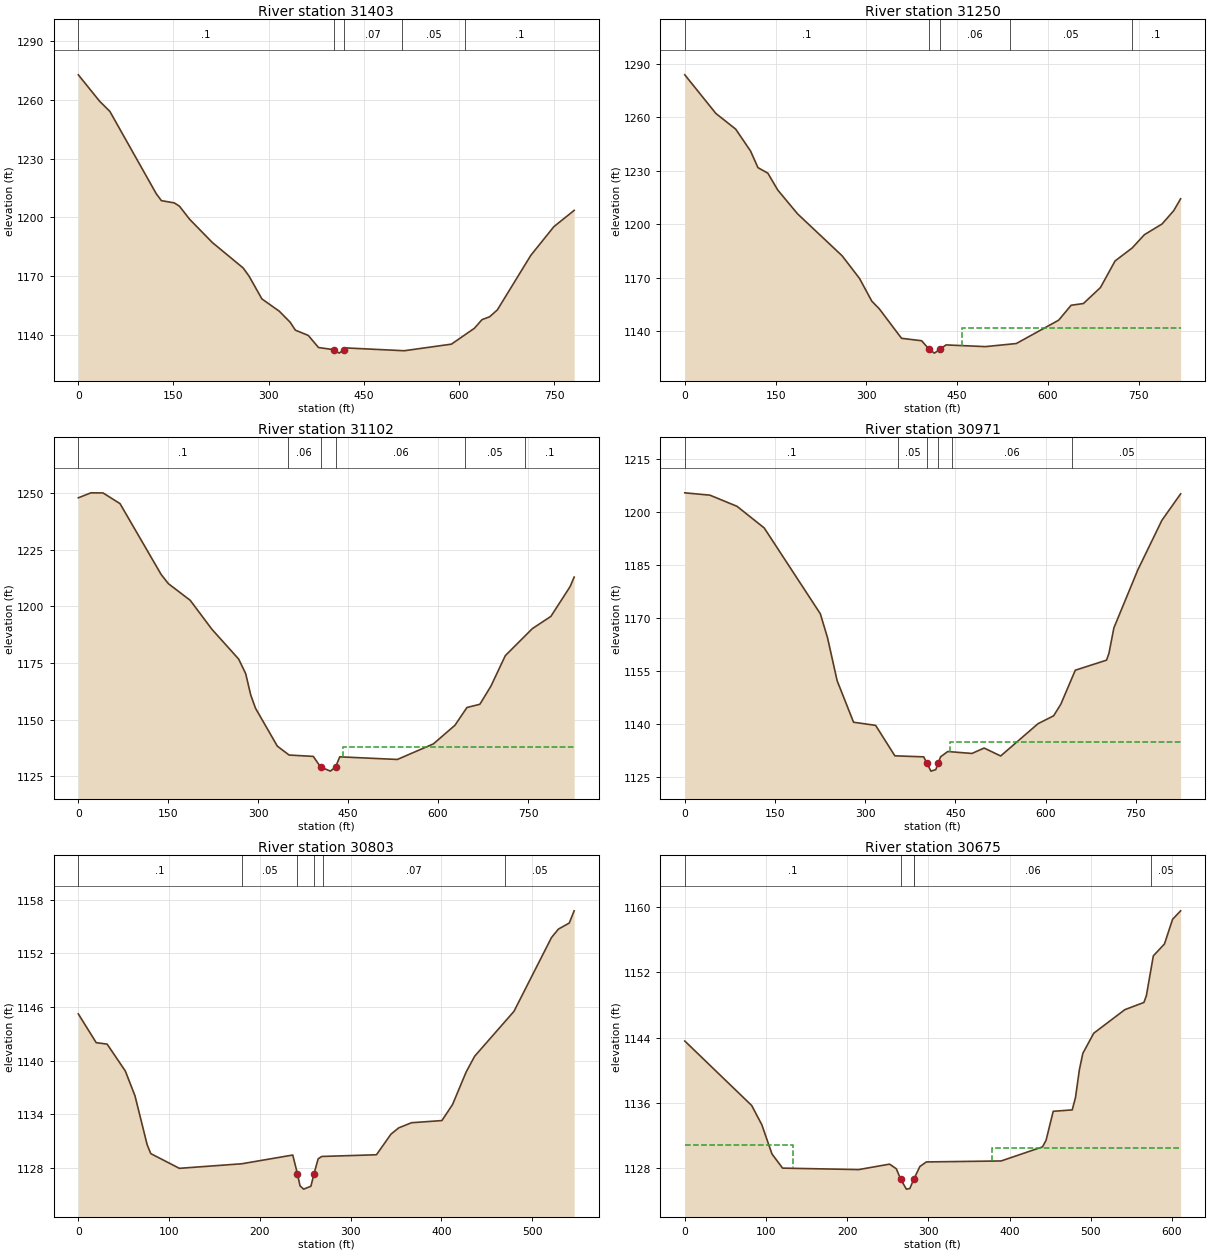
Type RM Length L Ch R = 1 ,31403   ,150.1,152.9,153.6
XS GIS Cut Line= 4
     2188144.077      752412.198     2188072.911      752816.149
2188047.45674305753059.0665668612188027.29664497753184.700997846
#Sta/Elev= 30
       0 1272.93    33.5 1259.44    49.7 1254.22   122.8 1212.12     131 1208.54
   151.3 1207.39   159.4 1205.72   175.6 1198.97   211.4 1187.08   259.8 1174.11
   269.1 1169.94   289.4 1158.26   316.9 1151.94     334 1146.32   342.2 1142.26
   362.5 1139.58   378.7 1133.37   402.71132.278   411.2 1130.51  418.26 1132.27
   423.3 1133.15   513.7 1131.73   588.2 1135.11   624.4 1143.22   636.4 1147.64
   648.5 1149.13   660.6 1152.63   713.3 1180.52   749.7 1195.23   781.7 1203.56
#Mann= 5 ,-1,0
       0      .1       0   402.7    .045       0  418.26     .07       0
  510.17     .05       0  610.17      .1       0
Bank Sta=402.7,418.26
XS Rating Curve= 0 ,0
Exp/Cntr=0.3,0.1

Type RM Length L Ch R = 1 ,31250   ,151.2,148.1,143.6
XS GIS Cut Line= 4
     2188018.395      752398.9362187940.08923161752767.212161077
2187871.57904233 752967.880715482187841.13299136753196.512562766
#Sta/Elev= 30
       0 1283.88    51.4 1262.21    84.1 1253.44   108.6 1241.18   120.9 1231.84
   137.2 1228.75   153.6 1219.29   186.3 1205.95   260.1 1182.36   288.6 1169.76
     309 1156.98   321.3 1152.71   358.1 1136.16   391.3 1134.79   403.2 1130.18
   412.4 1127.85  422.33 1130.18   431.6 1132.45   496.9  1131.5   547.7 1133.23
   617.7 1146.32   638.3 1154.69   658.5 1155.64   686.7  1164.6   710.9 1179.53
   739.2 1186.82   759.3 1194.24   788.6 1200.28   807.8 1207.72   819.2  1214.4
#Mann= 5 ,-1,0
       0      .1       0   403.2    .045       0  422.33     .06       0
  536.51     .05       0  738.55      .1       0
#XS Ineff= 2 , 0
                          458.72         1142.03
Permanent Ineff=
       F       F
Bank Sta=403.2,422.33
XS Rating Curve= 0 ,0
Exp/Cntr=0.3,0.1

Type RM Length L Ch R = 1 ,31102   ,130.7,131.1,129.5
XS GIS Cut Line= 4
      2187749.22      752372.379  2187793.303115752688.328741423
2187778.54953057753004.146769203     2187779.348      753196.012
#Sta/Elev= 30
       0 1248.01      21 1250.21    41.2 1250.16    69.5 1245.45     138 1214.18
   150.2 1210.06   186.6  1202.7   222.9 1189.86   267.4 1176.73   279.1 1170.32
   287.6 1160.79   295.6 1154.95   331.9 1138.24   351.5  1134.3   391.9 1133.69
     404 1129.03   420.4 1127.18   429.11129.027     436  1133.5   532.1 1132.34
   592.2 1139.22   628.2 1147.46   648.2 1155.31   669.7 1156.73   688.2 1164.77
   712.2 1178.25   757.3 1190.18   788.2 1195.59   820.2 1208.73     827 1212.96
#Mann= 6 ,-1,0
       0      .1       0  349.01     .06       0     404    .045       0
   429.1     .06       0  645.17     .05       0  745.17      .1       0
#XS Ineff= 2 , 0
                          440.79         1137.67
Permanent Ineff=
       F       F
Bank Sta=404,429.1
XS Rating Curve= 0 ,0
Exp/Cntr=0.3,0.1

Type RM Length L Ch R = 1 ,30971   ,169.2,168.1,166.8
XS GIS Cut Line= 4
     2187623.909      752376.4442187665.09476145 752556.21723509
2187655.94602541 753084.34881589     2187651.884      753196.356
#Sta/Elev= 30
       0 1205.35    41.8 1204.69    86.9 1201.53   132.1 1195.41   225.4 1171.13
   237.4 1164.34   253.4 1152.18   280.7 1140.43   317.4 1139.54   349.4 1130.92
   397.4 1130.63   402.6 1128.84   409.4 1126.59   417.4 1127.01  421.54 1128.84
   425.4 1130.64   437.4 1132.14   477.6 1131.59   497.9 1133.12   525.4 1130.88
   587.4    1140   613.5 1142.25   625.5 1145.55   649.5 1155.15   701.5    1158
   705.5 1159.95   713.7 1167.13   753.5 1183.54   793.5 1197.56   824.7 1205.06
#Mann= 6 ,-1,0
       0      .1       0  354.43     .05       0   402.6    .045       0
  421.54     .05       0  444.43     .06       0  644.43     .05       0
#XS Ineff= 2 , 0
                          441.08         1134.95
Permanent Ineff=
       F       F
Bank Sta=402.6,421.54
XS Rating Curve= 0 ,0
Exp/Cntr=0.3,0.1

Type RM Length L Ch R = 1 ,30803   ,122.9,127.6,131.6
XS GIS Cut Line= 2
2187477.40416998752545.535814383 2187513.3610576753090.546987826
#Sta/Elev= 30
       0 1145.22    19.7    1142    31.7 1141.84    51.8 1138.82    62.4 1136.05
    75.8 1130.57    79.8 1129.57   111.3 1127.92     180 1128.43   236.2 1129.41
   241.3 1127.34   244.2 1125.96   248.2 1125.59   256.2 1125.91  259.67 1127.34
   264.2 1128.99   268.2 1129.25   328.4 1129.44   344.4 1131.75   352.9 1132.45
     367 1133.03   400.5 1133.27   412.2 1135.06   427.2 1138.71   436.6 1140.48
   479.9 1145.51   521.2 1153.77   528.8 1154.72   540.8  1155.4   546.2 1156.77
#Mann= 6 ,-1,0
       0      .1       0     180     .05       0   241.3    .045       0
  259.67     .05       0     270     .07       0     470     .05       0
Bank Sta=241.3,259.67
XS Rating Curve= 0 ,0
Exp/Cntr=0.3,0.1

Type RM Length L Ch R = 1 ,30675   ,54.8,52.7,49.9
XS GIS Cut Line= 6
2187460.93853766752553.7086488262187429.50015379752668.234190048
  2187382.342578752760.3037427952187362.13218837752889.051410052
2187365.87485311 752944.442848292187460.19000471753122.593690192
#Sta/Elev= 30
       0 1143.57    82.4 1135.65    94.9 1133.28   107.3 1129.71   120.4 1127.96
   214.2 1127.78   252.2 1128.45   260.5 1127.88   265.8  1126.6   272.9 1125.38
   277.1 1125.45     282  1126.6   289.5 1128.16   297.5 1128.72   389.6 1128.84
   440.5 1130.57   444.9 1131.38   453.7 1134.94   477.1 1135.11   481.1 1136.61
   485.9 1140.03   490.2 1142.06   503.6 1144.53   541.9 1147.42   565.4 1148.31
   568.4 1149.13     577 1154.03   590.7 1155.49   600.7 1158.52   610.6 1159.56
#Mann= 5 ,-1,0
       0      .1       0   265.8    .045       0     282      .1       0
  282.21     .06       0  574.17     .05       0
#XS Ineff= 2 , 0
          132.97 1130.75  378.18         1130.48
Permanent Ineff=
       F       F
Bank Sta=265.8,282
XS Rating Curve= 0 ,0
Exp/Cntr(USF)=0,0
Exp/Cntr=0.3,0.1

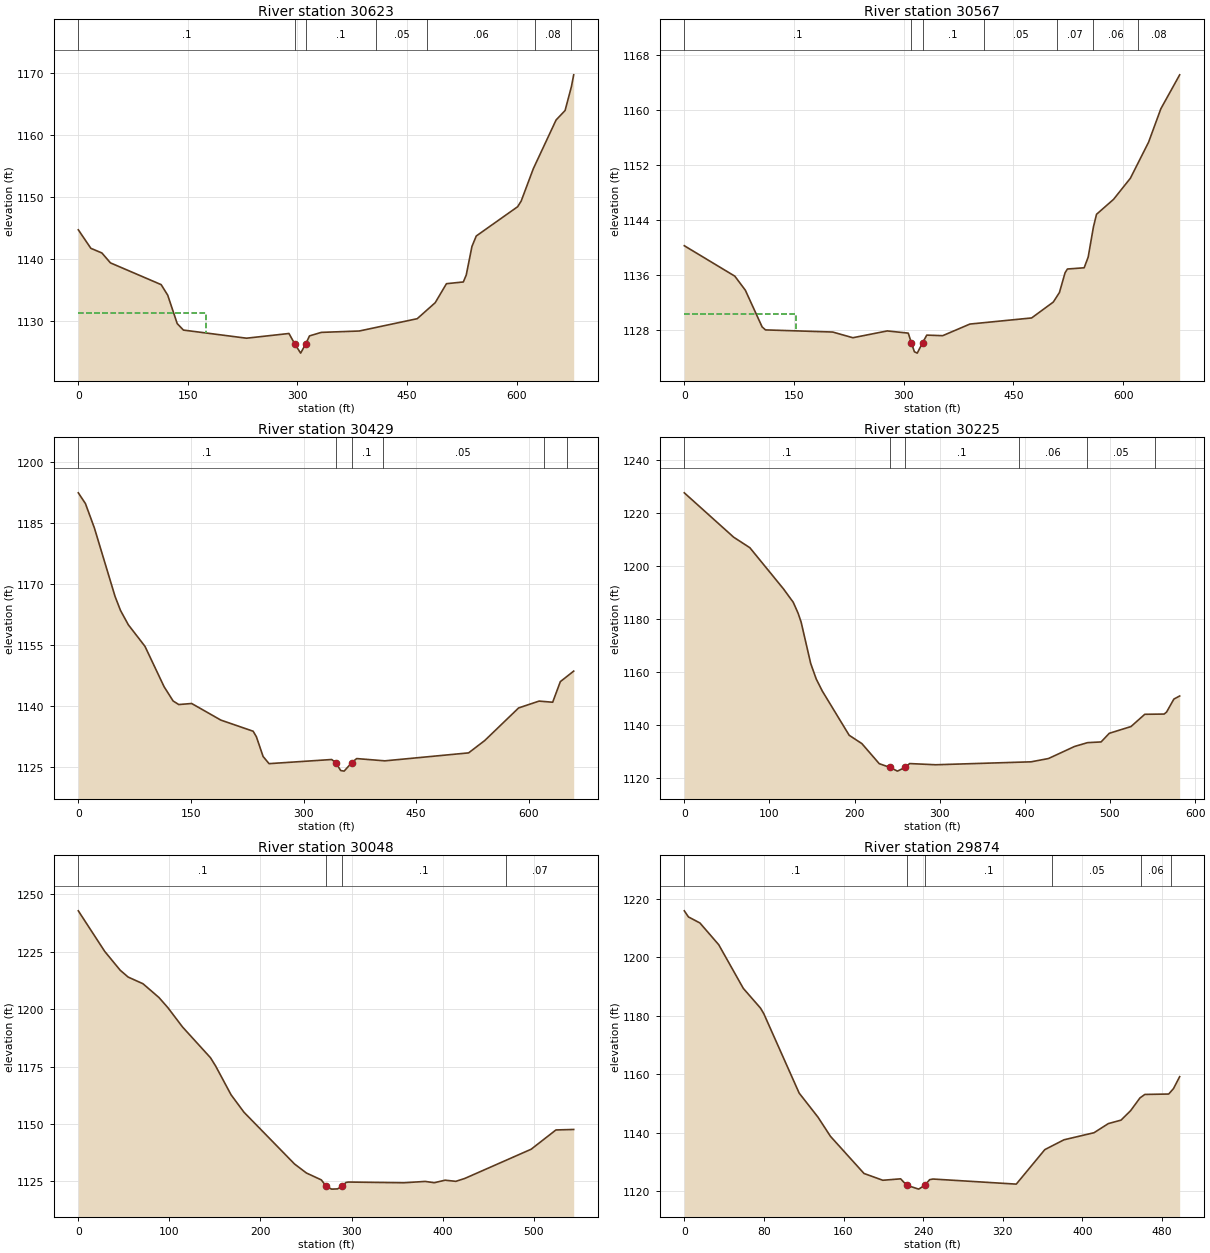
Type RM Length L Ch R = 1 ,30623   ,60.8,56,50.5
XS GIS Cut Line= 6
2187430.28565133752536.2521211592187372.99053671752648.070006158
2187329.55714336752763.5843501652187312.93575113752899.829437107
  2187342.439303 752989.243931472187444.37783681753157.260369514
#Sta/Elev= 30
       0 1144.72    17.2 1141.73    32.3 1140.98      44 1139.38   113.4 1135.87
   122.4 1134.17   135.4 1129.58   143.9 1128.53   230.3 1127.22   288.4 1127.98
  296.07 1126.35   304.4 1124.81   311.61126.348   316.5 1127.59   332.6 1128.16
   384.6 1128.38     464 1130.37   488.6 1132.95     504 1136.02   527.1  1136.3
   531.1 1137.42   538.9 1142.03   544.8 1143.72   601.5 1148.45   606.3 1149.36
   622.9 1154.58   654.1 1162.45   666.4 1163.98   675.1 1167.84   678.2 1169.74
#Mann= 7 ,-1,0
       0      .1       0  296.07    .045       0   311.6      .1       0
  407.23     .05       0   477.5     .06       0   625.1     .08       0
   675.1     .05       0
#XS Ineff= 2 , 0
          175.18 1131.29
Permanent Ineff=
       F       F
Bank Sta=296.07,311.6
XS Rating Curve= 0 ,0
Exp/Cntr=0.3,0.1

Type RM Length L Ch R = 1 ,30567   ,137.2,138.2,138
XS GIS Cut Line= 5
2187389.61875011752552.5053929192187252.18810064752795.703748103
2187280.48264612752881.2610641932187351.30864895753090.588765484
2187376.25974725753173.759093169
#Sta/Elev= 30
       0  1140.2    69.1 1135.77    83.5 1133.72   106.4 1128.39     111 1127.95
   202.9 1127.64   230.5 1126.81   277.5  1127.8   306.2 1127.48   310.4  1126.1
   314.6 1124.77   318.5 1124.57  325.88 1126.09   331.5 1127.19   353.3 1127.11
   390.5  1128.8   474.9 1129.69   504.5    1132   512.9 1133.39   520.6 1136.26
   523.8 1136.81   546.7 1136.99   552.2 1138.54   559.4 1142.94   563.6 1144.77
   586.9 1146.95   609.9 1150.02   634.8 1155.27   651.6 1160.14   677.3 1165.07
#Mann= 7 ,-1,0
       0      .1       0   310.4    .045       0  325.88      .1       0
  409.46     .05       0  509.46     .07       0  559.46     .06       0
  620.44     .08       0
#XS Ineff= 2 , 0
          152.07  1130.2
Permanent Ineff=
       F       F
Bank Sta=310.4,325.88
XS Rating Curve= 0 ,0
Exp/Cntr(USF)=0,0
Exp/Cntr=0.3,0.1

Type RM Length L Ch R = 1 ,30429   ,207.4,203.2,197.3
XS GIS Cut Line= 5
2186968.85951219752571.5202277832187060.34687265752647.297637452
  2187107.476725752764.6602109632187156.45480686752932.849095838
2187245.27531947753155.193978516
#Sta/Elev= 30
       0 1192.49     9.5 1189.84    21.4 1183.85      49 1166.96    56.2 1163.54
    66.6 1160.02    88.8  1154.7   114.3 1144.75   126.3 1141.25   133.8 1140.37
     151 1140.63   189.8 1136.55   232.9  1133.8   237.2 1132.45   246.2 1127.57
   254.1 1125.82   337.5 1126.84     343 1126.06   349.5 1124.13   354.1 1123.98
  364.18 1126.06   370.8 1127.07   408.3 1126.51   519.9 1128.47   541.4 1131.51
   586.5 1139.53   613.8 1141.22   631.9 1140.94   642.1 1146.01   659.9  1148.6
#Mann= 6 ,-1,0
       0      .1       0     343    .045       0  364.18      .1       0
  405.27     .05       0  620.44     .06       0  650.44     .07       0
Bank Sta=343,364.18
XS Rating Curve= 0 ,0
Exp/Cntr=0.3,0.1

Type RM Length L Ch R = 1 ,30225   ,179.6,177.9,175.6
XS GIS Cut Line= 3
 2186783.2231798752768.6441727642186861.77293373752818.546369375
 2187164.8825724753202.053991479
#Sta/Elev= 30
       0 1227.56      58 1210.83      77 1206.87   116.6  1191.3     128 1186.28
   133.7 1182.15   137.2 1178.87   148.5 1163.19     155 1157.35   162.1 1152.83
   193.7 1136.14   208.6    1133     229 1125.43  241.29 1124.06   250.4 1122.62
   259.6 1124.07   264.7 1125.47   295.3 1125.02   407.4 1126.13   427.8 1127.37
   458.4 1131.92   473.7 1133.36   489.6 1133.63   499.2 1136.88   524.7 1139.43
   540.9 1144.05   563.7 1144.14   566.5 1144.89   575.1 1149.79   581.9 1150.95
#Mann= 6 ,-1,0
       0      .1       0  241.29    .045       0   259.6      .1       0
  393.06     .06       0  473.06     .05       0  553.06     .06       0
Bank Sta=241.29,259.6
XS Rating Curve= 0 ,0
Exp/Cntr=0.3,0.1

Type RM Length L Ch R = 1 ,30048   ,170.4,174,177.1
XS GIS Cut Line= 2
2186647.96726818752892.3636890812187048.01654434753260.808240726
#Sta/Elev= 30
       0 1242.82      29 1225.16      46 1216.96    54.7 1213.99      71 1211.08
    88.5  1205.1    98.2 1200.74   114.5 1192.22   145.1 1178.88   150.8 1175.25
   167.7 1162.75   181.9 1155.14   237.4 1132.61   250.4  1128.7   266.8 1125.69
  272.26 1122.89   278.1 1121.67   284.6 1121.77   289.5 1122.88   293.9 1124.57
   296.4 1124.75   357.4 1124.44   380.9 1125.02   390.9 1124.46   402.7 1125.56
   414.5 1125.06   424.4 1126.33   497.2 1139.04   524.4 1147.43   543.9 1147.64
#Mann= 4 ,-1,0
       0      .1       0  272.26    .045       0   289.5      .1       0
     470     .07       0
Bank Sta=272.26,289.5
XS Rating Curve= 0 ,0
Exp/Cntr=0.3,0.1

Type RM Length L Ch R = 1 ,29874   ,235.3,243.4,237.3
XS GIS Cut Line= 3
2186598.17801892753001.5529810072186623.84787315753043.651541934
 2186870.2784737753418.431413602
#Sta/Elev= 30
       0 1215.85     4.2 1213.76    15.7  1211.7    34.6 1204.27    59.3 1189.34
    76.6 1182.59    79.9 1180.68   115.4 1153.56   134.4 1145.29   146.9 1138.75
   180.6 1126.06   199.5 1123.74   217.4 1124.23   223.5 1122.05   235.5 1120.71
  241.79 1122.05   246.5 1123.94   249.9 1124.16   333.6 1122.42   362.3 1134.22
   381.5 1137.57   411.7 1139.99   426.1 1143.11   438.9  1144.3   448.5 1147.53
   457.9 1151.89   462.8 1153.08   486.8 1153.22   491.6 1155.09   497.8 1159.16
#Mann= 6 ,-1,0
       0      .1       0   223.5    .045       0  241.79      .1       0
  369.31     .05       0  459.31     .06       0  489.31     .08       0
Bank Sta=223.5,241.79
XS Rating Curve= 0 ,0
Exp/Cntr=0.3,0.1

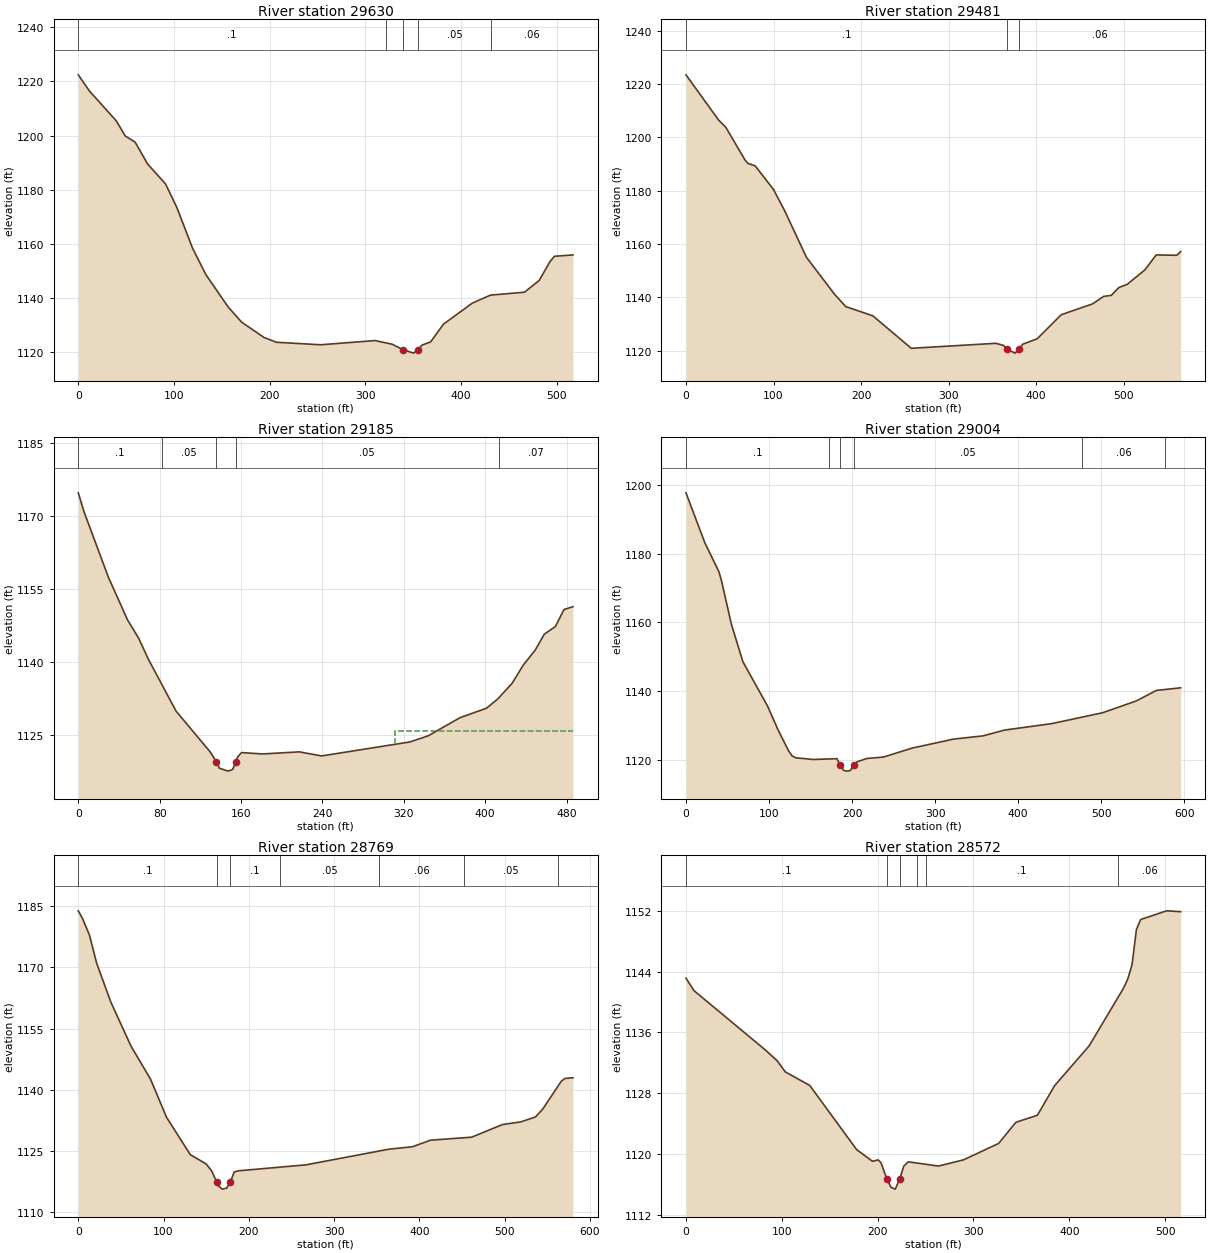
Type RM Length L Ch R = 1 ,29630   ,147.6,149,148.6
XS GIS Cut Line= 3
2186500.51000235753035.2790143922186652.03369391753284.243359839
2186751.83808713753486.624490539
#Sta/Elev= 30
       0 1222.45    11.6 1216.49    39.7 1205.45    49.1 1199.84    59.4 1197.58
    72.5 1189.47    91.2 1182.11     103 1173.44   119.3 1158.46   133.3 1148.61
   156.7 1136.58   170.8 1130.98   194.2 1125.31   207.1 1123.55   253.3 1122.62
   310.3 1124.18   328.2 1122.81  339.43 1120.82   350.5 1119.53     355 1120.83
   359.4 1122.51   368.3 1123.68   381.7 1130.23   411.7 1137.98   430.8 1140.98
   466.4 1142.06   481.7 1146.37   493.2 1153.43   497.7 1155.35   517.1 1155.84
#Mann= 5 ,-1,0
       0      .1       0  321.45     .05       0  339.43    .045       0
     355     .05       0  431.45     .06       0
Bank Sta=339.43,355
XS Rating Curve= 0 ,0
Exp/Cntr=0.3,0.1

Type RM Length L Ch R = 1 ,29481   ,295.8,296.2,293.1
XS GIS Cut Line= 3
2186427.29756525753057.6590343262186487.56835943753252.302996307
2186637.02027426753581.416471968
#Sta/Elev= 30
       0 1223.39    37.2 1206.47    45.6 1203.67    67.5 1191.43    70.7 1190.19
    79.1 1189.25     100 1180.39   112.6 1172.53   137.7 1154.94   169.8 1141.08
   182.6 1136.47   213.5 1133.02   257.4 1120.84   354.1 1122.71   362.9 1121.91
   366.81120.426   376.1 1119.03   380.4 1120.47   384.8 1122.37   401.3 1124.42
   428.8 1133.43   464.7 1137.52   477.1  1140.3   485.9 1140.69   494.7 1143.65
     504 1144.79   524.5 1150.31   537.2 1155.86   560.6 1155.72   565.2 1157.12
#Mann= 3 ,-1,0
       0      .1       0   366.8    .045       0   380.4     .06       0
Bank Sta=366.8,380.4
XS Rating Curve= 0 ,0
Exp/Cntr=0.3,0.1

Type RM Length L Ch R = 1 ,29185   ,170.2,180.7,184.3
XS GIS Cut Line= 4
2186273.29923401753241.8687139622186309.32987804753303.980403131
2186430.66906057753579.9826757462186517.87749788753651.783428504
#Sta/Elev= 30
       0 1174.82     5.7 1170.89    29.6 1157.43    48.4 1148.64    59.3 1144.87
    68.9 1140.53    96.1 1129.84   129.9 1121.36   135.6 1119.43   138.7 1118.06
   147.4 1117.46   151.8  1117.8   154.91119.428   156.8 1120.42   160.5 1121.28
   181.1    1121   217.3 1121.43   239.2 1120.59   325.9 1123.47     344 1124.74
   375.2 1128.47   401.2 1130.42   412.2 1132.31   426.4 1135.54   437.4 1139.31
   449.1 1142.38   458.2 1145.71     469 1147.25   477.5 1150.77   486.3 1151.35
#Mann= 5 ,-1,0
       0      .1       0   81.81     .05       0   135.6    .045       0
   154.9     .05       0   413.3     .07       0
#XS Ineff= 2 , 0
                          311.27         1125.72
Permanent Ineff=
       F       F
Bank Sta=135.6,154.9
XS Rating Curve= 0 ,0
Exp/Cntr=0.3,0.1

Type RM Length L Ch R = 1 ,29004   ,241.6,235,227.2
XS GIS Cut Line= 5
2186142.99514206753246.0387622722186165.45113054 753296.77266216
2186200.38266817753398.2404619362186193.72904195 753532.14468951
2186249.64100108753825.808763312
#Sta/Elev= 30
       0 1197.74    22.7 1183.22    39.7 1174.75    42.8 1172.13    54.8 1159.38
    68.6 1148.55    98.2 1135.69   110.9 1128.74   123.6 1122.64   127.8 1121.18
   132.1 1120.62   153.2 1120.12   181.8 1120.35   185.8 1118.47   189.8 1116.97
   193.8 1116.73   197.8 1116.89  202.66 1118.47   205.8 1119.42   217.8 1120.41
   237.8 1120.82   272.6 1123.45   322.3 1126.05     358    1127   383.4 1128.67
   440.1 1130.54   501.7 1133.72   542.2 1137.15   566.6 1140.22   595.8 1140.99
#Mann= 6 ,-1,0
       0      .1       0  172.79     .05       0   185.8    .045       0
  202.66     .05       0  476.86     .06       0  576.86     .07       0
Bank Sta=185.8,202.66
XS Rating Curve= 0 ,0
Exp/Cntr=0.3,0.1

Type RM Length L Ch R = 1 ,28769   ,194.8,197.2,196.4
XS GIS Cut Line= 4
2185912.19932082753296.5933661512185933.48821722753370.157620101
2186049.92667597753563.944483608 2186151.8099545753822.150773972
#Sta/Elev= 30
       0  1183.9     4.8 1182.11    13.1 1177.96    21.4 1171.16    38.1 1161.55
    61.8 1150.72    84.8 1142.56   103.4 1133.27   131.4 1124.06   150.1 1121.76
   156.5 1120.06   162.4 1117.32   164.1 1116.46   168.8  1115.6     174 1115.83
  178.33 1117.31   182.8 1119.78   187.4 1120.09   266.8 1121.55   364.2  1125.4
   391.7 1125.99   413.3 1127.61   461.4 1128.35   497.5 1131.45     519  1132.1
   536.2 1133.31   544.8 1135.26   566.3 1142.02   570.6 1142.75   580.2 1142.94
#Mann= 7 ,-1,0
       0      .1       0   162.4    .045       0  178.33      .1       0
  236.58     .05       0  352.66     .06       0  452.66     .05       0
  562.66     .06       0
Bank Sta=162.4,178.33
XS Rating Curve= 0 ,0
Exp/Cntr=0.3,0.1

Type RM Length L Ch R = 1 ,28572   ,214,224.3,226
XS GIS Cut Line= 3
2185782.16956054753377.0884807422185811.94659144753494.143016003
  2185991.635571753846.333415955
#Sta/Elev= 30
       0 1143.14     8.3  1141.5    82.6 1133.72      95  1132.3   103.7 1130.81
   129.2 1129.03   178.1  1120.6   194.6 1119.07   200.5 1119.25   203.5 1118.88
   209.5 1116.78     214 1115.64   218.4 1115.41     223 1116.75   227.3 1118.44
     232    1119   263.4 1118.44   289.7 1119.26   326.3 1121.42   344.2 1124.19
   366.7 1125.12   384.6    1129   420.6 1134.22   456.5  1141.8     461 1143.01
   465.5 1144.93     470 1149.52   474.5 1150.84   501.4 1151.98   516.2 1151.87
#Mann= 6 ,-1,0
       0      .1       0   209.5    .045       0     223      .1       0
  240.78     .05       0  250.78      .1       0  450.78     .06       0
Bank Sta=209.5,223
XS Rating Curve= 0 ,0
Exp/Cntr=0.3,0.1

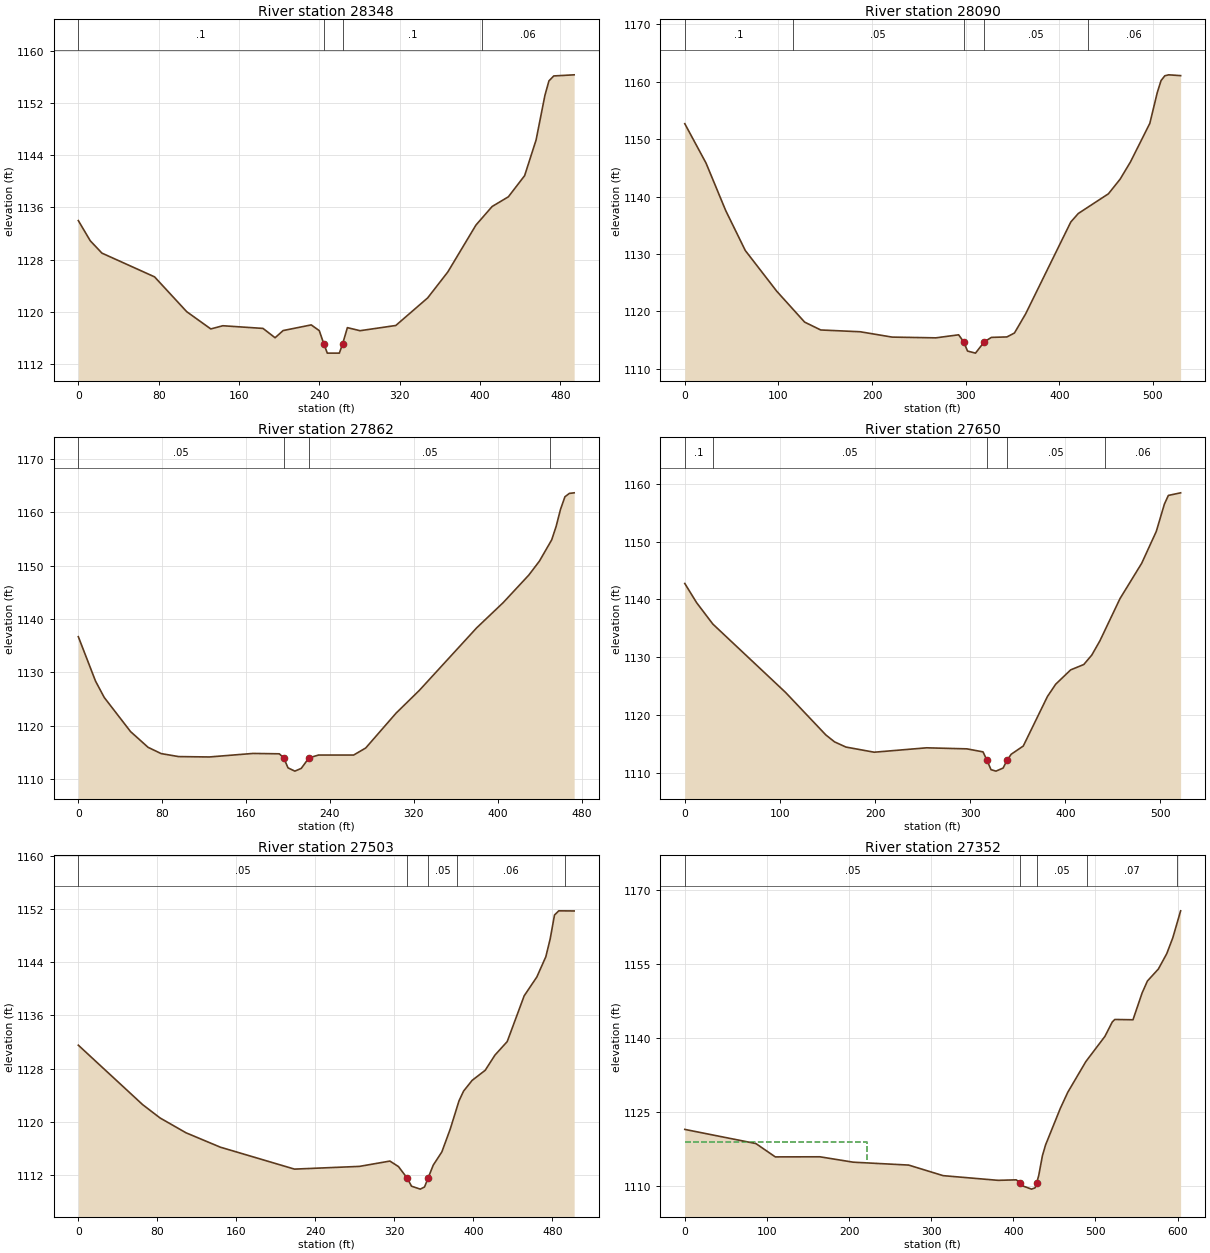
Type RM Length L Ch R = 1 ,28348   ,259.9,257.7,250.5
XS GIS Cut Line= 3
2185668.30971434753397.2844914482185673.02547192753799.471245036
2185686.44876191753890.005462607
#Sta/Elev= 30
       0 1133.97    11.9 1130.87    23.5 1128.98    75.9 1125.34   107.9    1120
   131.9 1117.35   143.9 1117.84   183.9 1117.43   195.9    1116   203.9  1117.1
   231.9 1117.97   239.9 1117.09   244.5 1115.04   247.9 1113.64   259.9 1113.64
   263.1 1115.03   267.9 1117.55   280.5 1117.08   316.1 1117.88   347.9 1122.12
   367.9 1126.09   395.9 1133.28     412 1136.13   428.2 1137.62   444.4 1140.87
   455.8 1146.34   464.6 1153.19   468.6  1155.4   473.4 1156.16   493.7 1156.33
#Mann= 4 ,-1,0
       0      .1       0   244.5    .045       0   263.1      .1       0
  402.21     .06       0
Bank Sta=244.5,263.1
XS Rating Curve= 0 ,0
Exp/Cntr=0.3,0.1

Type RM Length L Ch R = 1 ,28090   ,222.1,227.6,223.3
XS GIS Cut Line= 5
2185362.43936439753395.5044156132185387.90807603753476.909599186
 2185471.9428761753713.7349448422185467.57743194753767.211635797
 2185454.5437873753905.994362692
#Sta/Elev= 30
       0 1152.69    22.7 1145.83    43.7 1137.57    64.6 1130.62    98.2 1123.53
     128 1118.15   145.2 1116.78   187.4 1116.47   221.4 1115.54   268.1 1115.41
   292.5 1115.94   297.8 1114.73     302 1113.11   310.5 1112.75  319.92 1114.72
   327.5 1115.49   344.1 1115.57   352.1 1116.25   364.1  1119.6   412.3 1135.58
   420.3 1137.06   452.5 1140.49     465 1143.04     476 1146.03   496.7 1152.75
   504.7 1158.14   508.7  1160.2   512.7 1161.03   516.8  1161.2   529.6 1161.06
#Mann= 5 ,-1,0
       0      .1       0   115.3     .05       0   297.8    .045       0
  319.92     .05       0  430.24     .06       0
Bank Sta=297.8,319.92
XS Rating Curve= 0 ,0
Exp/Cntr=0.3,0.1

Type RM Length L Ch R = 1 ,27862   ,208.1,212.6,207.3
XS GIS Cut Line= 3
2185194.85180505753473.5031641932185289.16695665753789.458922038
2185333.57308409753925.558498928
#Sta/Elev= 30
       0 1136.69    16.4 1128.38    24.7 1125.32    49.8 1118.93    66.5 1115.99
      79 1114.81    95.7 1114.25   124.9 1114.18   166.6 1114.84   191.7 1114.77
   195.9 1114.01     200 1112.14   206.5 1111.53   212.6 1112.04  219.92    1114
   229.1 1114.54   262.6 1114.54   274.1 1115.86     303 1122.37   325.3 1126.65
   379.9 1138.34   405.2 1143.06   429.7 1148.23   439.8 1150.84   451.5 1154.82
   455.7 1157.32   459.9 1160.53   464.1 1162.87   468.3  1163.5   472.9 1163.61
#Mann= 4 ,-1,0
       0     .05       0   195.9    .045       0  219.92     .05       0
  449.73     .06       0
Bank Sta=195.9,219.92
XS Rating Curve= 0 ,0
Exp/Cntr=0.3,0.1

Type RM Length L Ch R = 1 ,27650   ,147.4,146.7,144.9
XS GIS Cut Line= 3
2185002.75891844753481.4907570562185020.50597815753529.661347699
2185175.15892705753973.337840458
#Sta/Elev= 30
       0 1142.75    12.5 1139.41    29.5 1135.73   105.9 1123.92   148.3 1116.56
   157.5 1115.36   169.4 1114.47   199.1 1113.58   254.2 1114.34   296.5 1114.16
   313.5 1113.64   317.7 1112.16   321.9 1110.56   327.1 1110.31   334.6 1110.84
  338.64 1112.17   343.1 1113.23   355.8 1114.65   381.2 1123.21   389.9 1125.34
   405.6 1127.81   419.4 1128.74   427.8 1130.37   436.3 1132.82   457.5 1140.14
   480.3 1146.25   495.6 1151.74   504.1 1156.45   508.3 1157.97   521.2 1158.42
#Mann= 5 ,-1,0
       0      .1       0      30     .05       0   317.7    .045       0
  338.64     .05       0  441.34     .06       0
Bank Sta=317.7,338.64
XS Rating Curve= 0 ,0
Exp/Cntr=0.3,0.1

Type RM Length L Ch R = 1 ,27503   ,149.1,151,148.7
XS GIS Cut Line= 3
2184849.37361665 753553.74664302     2184990.723      753866.255
2185056.00009757754011.367254124
#Sta/Elev= 30
       0 1131.51    65.2 1122.56    82.8 1120.56   109.1 1118.33   143.8 1116.17
   218.9 1112.87   284.7 1113.28   315.5 1114.08   324.2 1113.25     333 1111.52
   337.4  1110.3   346.3 1109.86   350.6 1110.19  354.19 1111.53   359.4 1113.47
   368.1 1115.45   376.6 1118.89   385.5 1123.14   390.1  1124.6   398.8 1126.22
     412 1127.73   421.9 1130.02   434.3 1132.05   451.5 1138.94   464.3 1141.77
   473.4 1144.81   477.8 1147.48   482.2 1151.09   486.5 1151.72   502.1  1151.7
#Mann= 5 ,-1,0
       0     .05       0     333    .045       0  354.19     .05       0
  382.99     .06       0  492.99     .05       0
Bank Sta=333,354.19
XS Rating Curve= 0 ,0
Exp/Cntr=0.3,0.1

Type RM Length L Ch R = 1 ,27352   ,162.6,165.4,165.4
XS GIS Cut Line= 3
2184672.63841166753567.7224116622184868.44741166753938.910411662
2184946.05250678754105.821432248
#Sta/Elev= 30
       0 1121.49    86.6 1118.62   110.2 1115.92   164.5 1115.94     205 1114.85
   272.6 1114.26   314.6 1112.12   381.5 1111.17   403.4 1111.27   408.7 1110.72
   412.3 1109.99   422.2 1109.39   426.6 1109.66   428.5 1110.67     431  1112.2
   435.4 1116.14   439.2 1118.32   457.3 1125.78   466.3 1129.01   488.3 1135.23
   511.5 1140.33   520.5 1143.26   523.6 1143.76   545.7  1143.7   556.8 1149.13
   563.3 1151.56   576.6 1153.98   586.8 1157.09   594.2 1160.32   603.7 1165.77
#Mann= 5 ,-1,0
       0     .05       0   408.7    .045       0   428.5     .05       0
  489.67     .07       0  599.67     .06       0
#XS Ineff= 2 , 0
           221.3  1118.9
Permanent Ineff=
       F       F
Bank Sta=408.7,428.5
XS Rating Curve= 0 ,0
Exp/Cntr=0.3,0.1

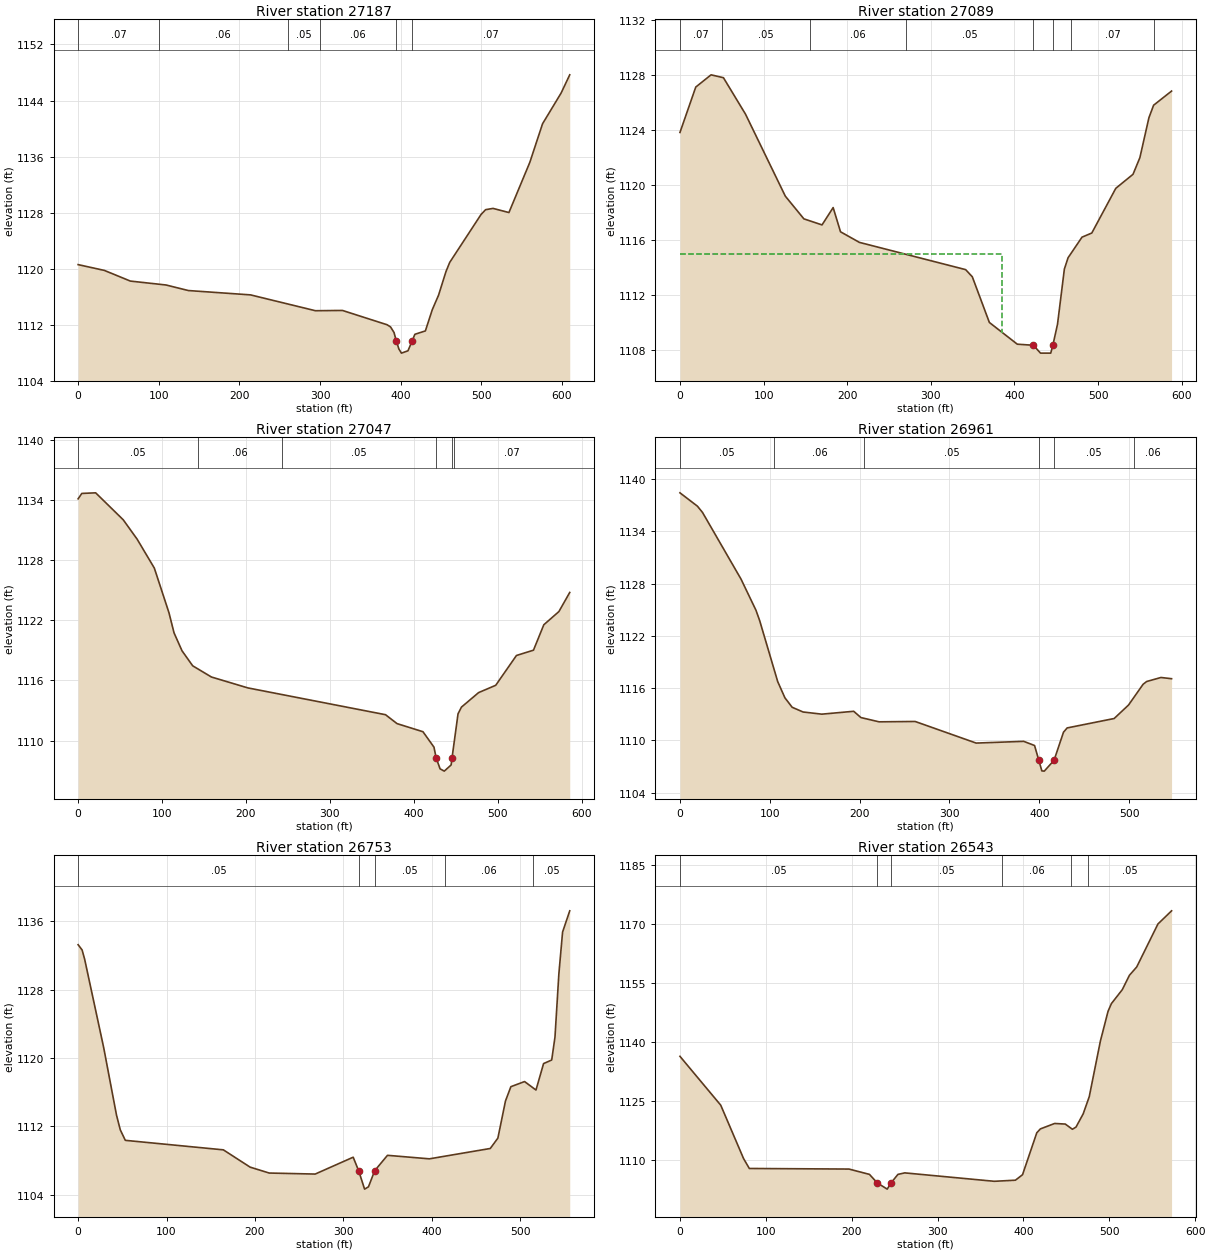
Type RM Length L Ch R = 1 ,27187   ,89.2,97.7,99.6
XS GIS Cut Line= 3
2184653.41616863753604.7458777962184689.35396454753923.052070173
2184798.19414645754191.045348272
#Sta/Elev= 30
       0 1120.59    32.6 1119.76    64.8 1118.24   109.1 1117.68   136.7 1116.89
   213.8 1116.27   294.3 1114.01   327.8 1114.05   383.1 1112.01   387.4  1111.7
   391.7 1110.91   394.7 1109.64   397.8 1108.54   400.9 1107.96     409 1108.29
  413.98 1109.64   417.6 1110.65   430.6 1111.13   439.2 1114.17   446.9 1116.22
   456.2 1119.62   460.8 1120.91   499.6 1127.74   505.3 1128.43   514.5 1128.61
   534.2 1128.02   560.1 1135.18   575.9 1140.69   598.9 1145.07   609.6 1147.67
#Mann= 6 ,-1,0
       0     .07       0     100     .06       0     260     .05       0
     300     .06       0   394.7    .045       0  413.98     .07       0
Bank Sta=394.7,413.98
XS Rating Curve= 0 ,0
Exp/Cntr=0.3,0.1

Type RM Length L Ch R = 1 ,27089   ,44.7,42.5,42.1
XS GIS Cut Line= 6
2184501.24909131753666.8225722222184574.26556555753769.501989118
 2184614.6268957753854.781205994 2184641.8345077753981.025942133
2184664.46703465754096.803172283  2184691.777066754214.103602936
#Sta/Elev= 30
       0 1123.82    18.9 1127.12    37.2 1128.01      52  1127.8    78.4 1125.15
     126 1119.19   148.2 1117.54   169.9  1117.1   183.2 1118.36     192  1116.6
   214.6 1115.83   341.6 1113.85   349.6 1113.33     370 1110.01   403.4 1108.43
   422.7 1108.35   431.2 1107.78   443.4 1107.78  445.93 1108.35   451.5 1109.88
   459.7 1113.89   464.1 1114.71   480.8 1116.21   492.5 1116.51   521.2 1119.76
   541.8 1120.78     550 1121.99   560.8 1124.89   566.4  1125.8   587.9 1126.83
#Mann= 8 ,-1,0
       0     .07       0      50     .05       0  155.99     .06       0
  270.34     .05       0   422.7    .045       0  445.93     .05       0
  467.45     .07       0  567.45     .05       0
#XS Ineff= 2 , 0
          385.67 1114.97
Permanent Ineff=
       T       F
Bank Sta=422.7,445.93
XS Rating Curve= 0 ,0
Exp/Cntr(USF)=0,0
Exp/Cntr=0.3,0.1

Type RM Length L Ch R = 1 ,27047   ,84.5,85.9,86.9
XS GIS Cut Line= 5
2184466.00558795753693.9620009692184543.46174048753776.347283577
2184590.81634667753922.7407508932184618.26255481754070.783934174
2184653.19409243754235.461182992
#Sta/Elev= 30
       0 1134.16     4.4  1134.7    20.9 1134.76    53.8 1132.06    70.3 1130.13
    90.8 1127.24   108.3 1122.76   114.3 1120.76   123.8 1118.97   136.5 1117.47
   158.8 1116.35   202.2 1115.26   366.3 1112.58     380 1111.69   410.9 1110.88
     424 1109.34   426.7 1108.24   431.3 1107.17   436.3 1106.94   444.5 1107.56
   445.51108.237   452.7 1112.67   456.8 1113.34   477.2 1114.79   497.6 1115.52
   522.3  1118.5   542.6 1119.03   554.9 1121.57   572.9 1122.89   585.8  1124.8
#Mann= 6 ,-1,0
       0     .05       0  143.08     .06       0  243.08     .05       0
   426.7    .045       0   445.5     .05       0  447.51     .07       0
Bank Sta=426.7,445.5
XS Rating Curve= 0 ,0
Exp/Cntr=0.3,0.1

Type RM Length L Ch R = 1 ,26961   ,210.5,207.5,203.8
XS GIS Cut Line= 3
2184442.27741395753719.6123338852184500.58918157753781.727042872
 2184553.8303607754240.615301099
#Sta/Elev= 30
       0 1138.42    19.4 1136.89    25.1 1136.17      68 1128.51    84.6 1124.94
    88.7 1123.76   108.8 1116.75   116.8 1114.89   124.9  1113.8     137 1113.26
   157.9 1113.01   193.4 1113.34   201.4 1112.62   221.6 1112.13   261.8 1112.17
   329.7 1109.69   382.6 1109.89   394.7 1109.41   399.4 1107.73   402.8  1106.5
   405.5 1106.47  416.37 1107.71   426.9 1110.94     431 1111.43   483.3 1112.51
   499.3 1114.06   515.5 1116.44   519.5 1116.76   535.4 1117.22   547.2 1117.08
#Mann= 6 ,-1,0
       0     .05       0   105.2     .06       0   205.2     .05       0
   399.4    .045       0  416.37     .05       0   505.2     .06       0
Bank Sta=399.4,416.37
XS Rating Curve= 0 ,0
Exp/Cntr=0.3,0.1

Type RM Length L Ch R = 1 ,26753   ,208.7,210.4,211.6
XS GIS Cut Line= 3
 2184214.7546307 753816.98892647     2184337.362      754117.937
2184423.24074995754332.675381652
#Sta/Elev= 30
       0 1133.24     4.5 1132.63     7.4 1131.54    28.9 1121.23    43.4 1113.34
    47.7 1111.61    53.4 1110.38   164.3 1109.27   194.6 1107.25   216.2 1106.56
   268.2 1106.44   311.2 1108.41   317.51106.797   324.1 1104.68   328.5 1104.95
  335.52 1106.83     350 1108.63   397.4 1108.22   466.3 1109.43   474.9 1110.64
   483.5 1114.98   489.6 1116.65   505.1 1117.25     518 1116.26   526.6 1119.35
   535.8 1119.77   539.5 1122.44   543.9 1129.83   548.1 1134.72   556.2  1137.2
#Mann= 5 ,-1,0
       0     .05       0   317.5    .045       0  335.52     .05       0
  414.97     .06       0  514.97     .05       0
Bank Sta=317.5,335.52
XS Rating Curve= 0 ,0
Exp/Cntr=0.3,0.1

Type RM Length L Ch R = 1 ,26543   ,191.4,189.7,186.2
XS GIS Cut Line= 3
2184047.26802233753945.8351152612184101.56992128754047.808544871
2184222.74316664754488.492722277
#Sta/Elev= 30
       0 1136.45    47.5 1124.03    74.1 1110.45    80.8 1107.94   196.9 1107.79
   220.7 1106.44  229.94 1104.25   241.4 1102.69   245.81104.249   253.9 1106.44
   261.9 1106.82   366.1 1104.68   390.7 1104.96     399 1106.35   415.6 1117.01
   419.8    1118   436.4 1119.38   448.8 1119.23   457.1 1117.91   461.3 1118.47
   469.6  1121.8   476.7 1126.18   489.7 1140.34   498.6 1147.89   502.5 1149.85
   515.2  1153.4   523.5 1157.05     532 1159.17   556.7 1170.09   572.6 1173.44
#Mann= 6 ,-1,0
       0     .05       0  229.94    .045       0   245.8     .05       0
  375.53     .06       0  455.53     .07       0  475.53     .05       0
Bank Sta=229.94,245.8
XS Rating Curve= 0 ,0
Exp/Cntr=0.3,0.1