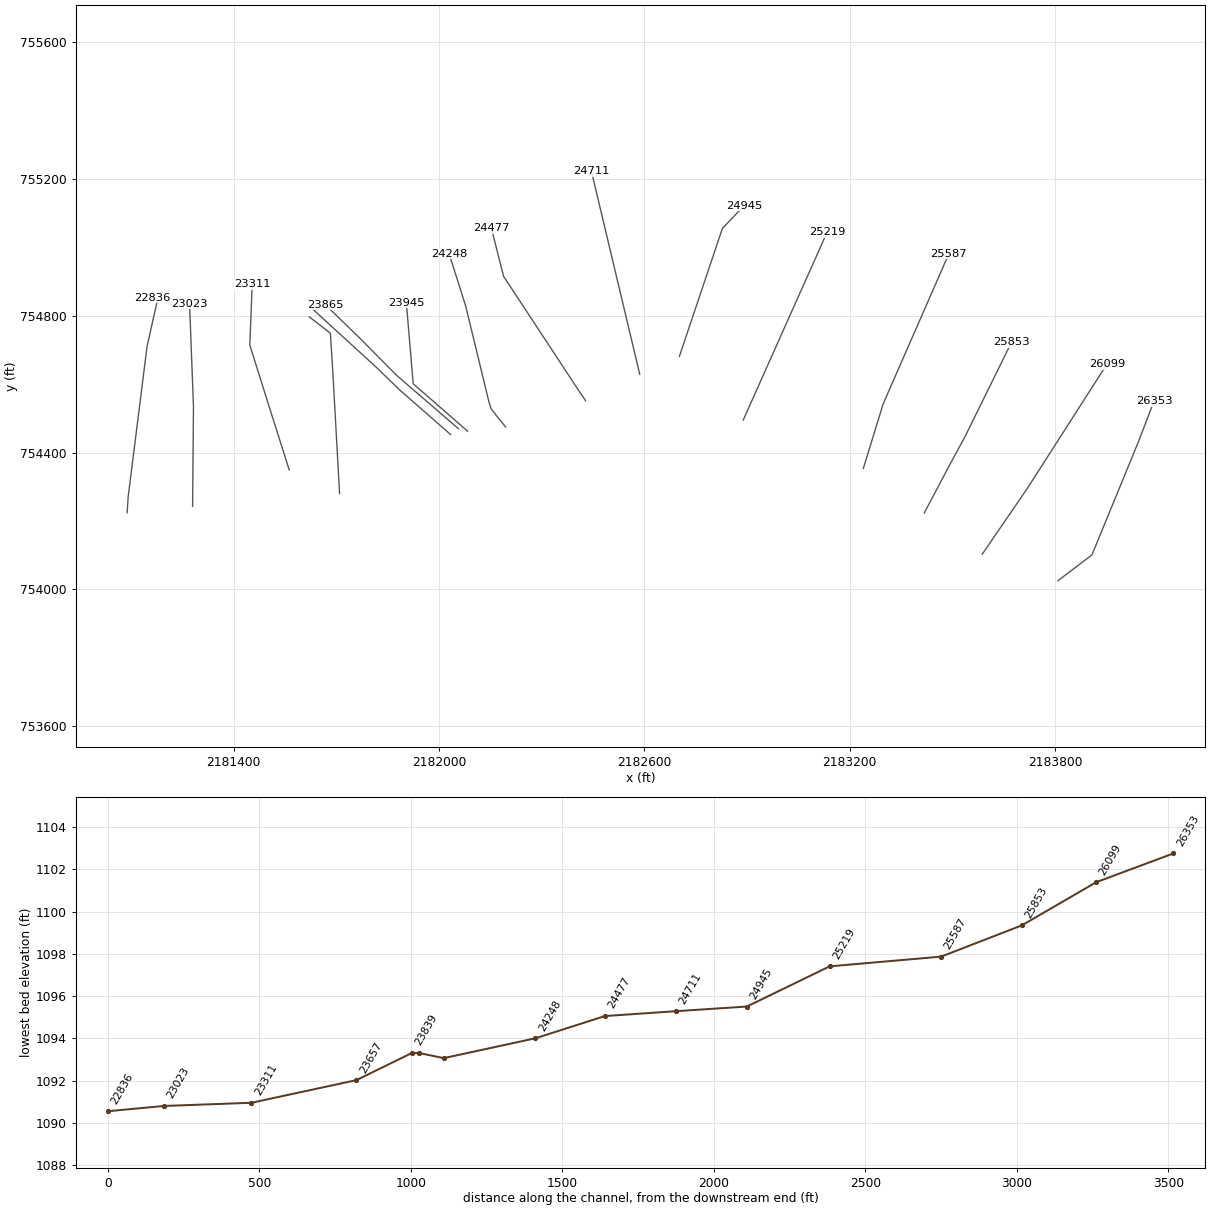
HEC-RAS study HACKERSCK.prj: HACKERSCK

--- HACKERSCK.g01 (geometry) --- (continued)

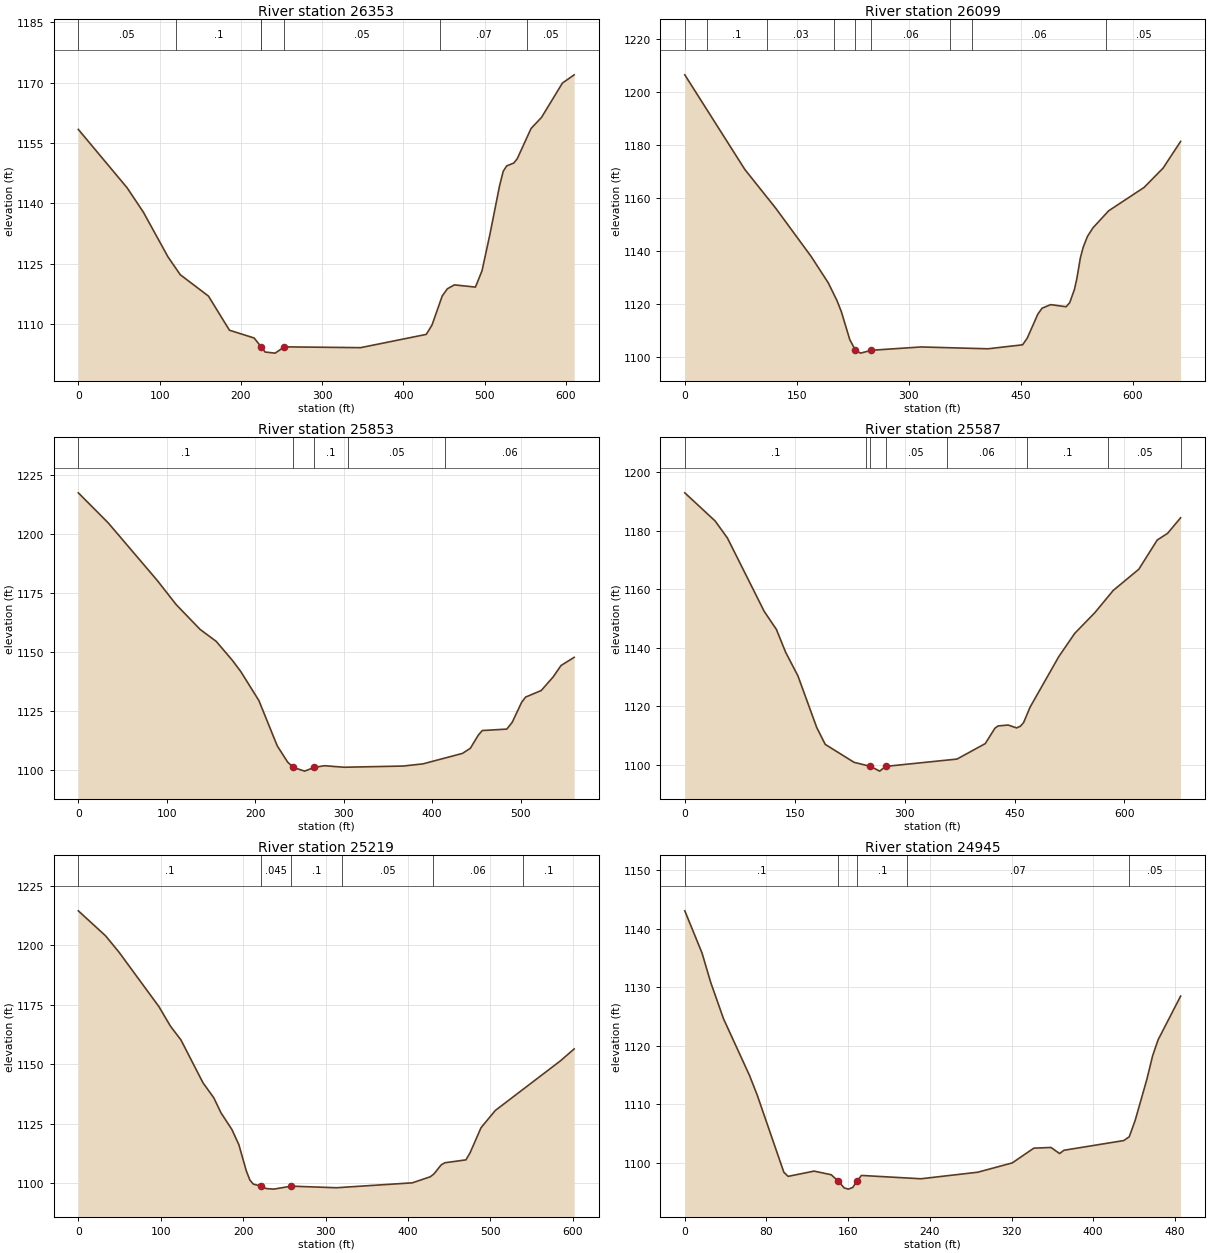
Type RM Length L Ch R = 1 ,26353   ,256.3,254.6,250.1
XS GIS Cut Line= 4
2183808.17404777754025.1466432712183907.65781232754100.578672244
2184043.50268088754431.4117534832184089.27694244754550.634115113
#Sta/Elev= 30
       0 1158.38      60 1143.87      80 1137.82   110.4 1126.66   125.5 1122.24
   160.1 1116.94     186 1108.44   216.3 1106.52     225 1104.32   229.9 1103.02
   242.2 1102.75  253.58 1104.31   347.4 1104.11   428.2 1107.41   435.3 1109.75
   447.8 1116.95   454.1 1118.74   462.8 1119.72   488.7 1119.17   496.8 1123.22
   506.7 1132.44   518.4 1144.36   522.9 1147.97   527.2 1149.31   535.8    1150
   540.1 1151.06   557.2 1158.62   570.1 1161.38   595.8 1169.91   610.2 1171.95
#Mann= 7 ,-1,0
       0     .05       0     120      .1       0  224.85     .05       0
     225    .045       0  253.58     .05       0  444.85     .07       0
  552.49     .05       0
Bank Sta=225,253.58
XS Rating Curve= 0 ,0
Exp/Cntr=0.3,0.1

Type RM Length L Ch R = 1 ,26099   ,242.8,245.4,245.6
XS GIS Cut Line= 3
2183587.28306174754102.7756712532183719.92710303754296.632932496
2183951.53210303754658.365932496
#Sta/Elev= 30
       0 1206.48    80.5 1170.73     122 1156.06   169.3 1137.89   192.3 1127.91
   203.8  1121.3   209.6 1117.18   221.1 1106.48  228.71 1102.46   235.5 1101.39
   249.9 1102.46   316.5 1103.72   406.3 1103.03   452.6 1104.53   458.8 1107.01
     473 1116.07   478.7 1118.35   490.3  1119.7     511  1118.9   515.8 1120.45
   522.1 1125.45   525.3 1129.44     530 1137.26   533.7 1141.25   539.5 1145.44
   546.9 1148.69     568 1155.14   615.5 1163.97   640.9 1171.26   664.4 1181.33
#Mann= 9 ,-1,0
       0     .03       0      30      .1       0     110     .03       0
     200      .1       0  228.71    .045       0   249.9     .06       0
  354.89     .05       0  384.89     .06       0  564.89     .05       0
Bank Sta=228.71,249.9
XS Rating Curve= 0 ,0
Exp/Cntr=0.3,0.1

Type RM Length L Ch R = 1 ,25853   ,265.1,266.4,267.4
XS GIS Cut Line= 4
2183417.90800234754223.4210842072183490.59113234754360.910717077
     2183537.683      754448.0732183672.73167884754722.406116406
#Sta/Elev= 30
       0 1217.59    33.7 1204.85    88.8 1180.55   110.6  1170.1   137.7 1159.54
   155.8  1154.5     174 1146.47   183.5 1141.72   204.1 1129.32   224.8  1110.1
   236.6 1103.17     243 1100.91   255.8 1099.35  266.46 1100.92   278.1 1101.65
   300.4    1101   367.3 1101.51   389.6 1102.44   434.2 1106.89   443.1 1109.07
     452  1114.6   456.5 1116.59   484.3 1117.21   490.3 1120.04     501 1128.56
   505.5 1130.81   523.2  1133.6   536.7 1139.39   545.6 1144.24   560.4  1147.7
#Mann= 5 ,-1,0
       0      .1       0     243    .045       0  266.46      .1       0
  304.59     .05       0  414.59     .06       0
Bank Sta=243,266.46
XS Rating Curve= 0 ,0
Exp/Cntr=0.3,0.1

Type RM Length L Ch R = 1 ,25587   ,367.4,368.1,366.3
XS GIS Cut Line= 3
2183239.93838175754353.5794922942183297.90121313754542.495387146
2183489.90977517754981.463741611
#Sta/Elev= 30
       0 1193.03    41.4 1183.41    58.2 1177.57   108.4 1152.49   125.1 1146.29
   137.7 1138.48   154.4 1130.45   180.1 1112.77   191.7 1107.01   231.1 1100.87
   253.2 1099.51     266 1097.87  274.22 1099.49   371.5 1101.99   410.1 1107.28
   423.2 1112.52   427.6 1113.32   441.3 1113.63   452.8 1112.65   458.1 1113.23
   462.5 1114.51   471.2 1119.72   510.5 1137.05   532.3    1145   559.8 1152.09
   584.7 1159.64   619.7 1166.91   644.8 1176.89     659 1179.19   676.7 1184.49
#Mann= 8 ,-1,0
       0      .1       0  247.61     .05       0   253.2    .045       0
  274.22     .05       0  357.61     .06       0  467.61      .1       0
  577.61     .05       0  676.73      .1       0
Bank Sta=253.2,274.22
XS Rating Curve= 0 ,0
Exp/Cntr=0.3,0.1

Type RM Length L Ch R = 1 ,25219   ,271.2,273.2,273.4
XS GIS Cut Line= 2
2182889.02440795754495.0797370152183134.20718467755044.567378465
#Sta/Elev= 30
       0  1214.5      33 1204.01    49.4 1197.09    97.9 1174.15   111.8 1165.97
   124.5  1160.2   151.2  1142.2   164.4 1135.83   173.1 1129.53   186.3 1122.53
   194.8 1116.12   203.8 1105.14   208.2 1101.21   212.5 1099.49     222 1098.66
   228.1 1097.64   237.2 1097.41   258.4 1098.66   313.3 1097.99   405.3 1100.06
   427.2 1102.62   431.6 1103.82   440.3  1107.6   444.7  1108.5   470.4 1109.72
   475.4  1112.7   488.7 1123.26     506  1130.5   584.9 1151.34   601.7 1156.39
#Mann= 6 ,-1,0
       0      .1       0     222    .045       0   258.4      .1       0
     320     .05       0     430     .06       0     540      .1       0
Bank Sta=222,258.4
XS Rating Curve= 0 ,0
Exp/Cntr(USF)=0,0
Exp/Cntr=0.3,0.1

Type RM Length L Ch R = 1 ,24945   ,226.6,234.3,240.8
XS GIS Cut Line= 4
2182702.58004192754681.1855773622182714.59353369754717.226052692
 2182828.2596482755055.452051948 2182890.8940925755121.166878762
#Sta/Elev= 30
       0 1143.07    16.9 1135.85    25.3 1130.88      38 1124.59    63.3 1114.97
    70.8 1111.65      97  1098.4   101.2 1097.69   126.6 1098.59   143.4 1097.97
  150.04 1096.91   156.1 1095.72   160.3 1095.51   164.5  1095.8   168.8 1096.92
     173 1097.85   231.3 1097.28   286.9  1098.4   320.7 1099.99   341.8 1102.51
   358.6 1102.63   367.1 1101.59   371.3 1102.15   429.9 1103.81   435.3 1104.46
   441.1 1107.27   452.6 1114.31   458.2 1118.31   463.5 1121.01   485.6  1128.5
#Mann= 5 ,-1,0
       0      .1       0  150.04    .045       0   168.8      .1       0
  217.99     .07       0   434.8     .05       0
Bank Sta=150.04,168.8
XS Rating Curve= 0 ,0
Exp/Cntr=0.3,0.1

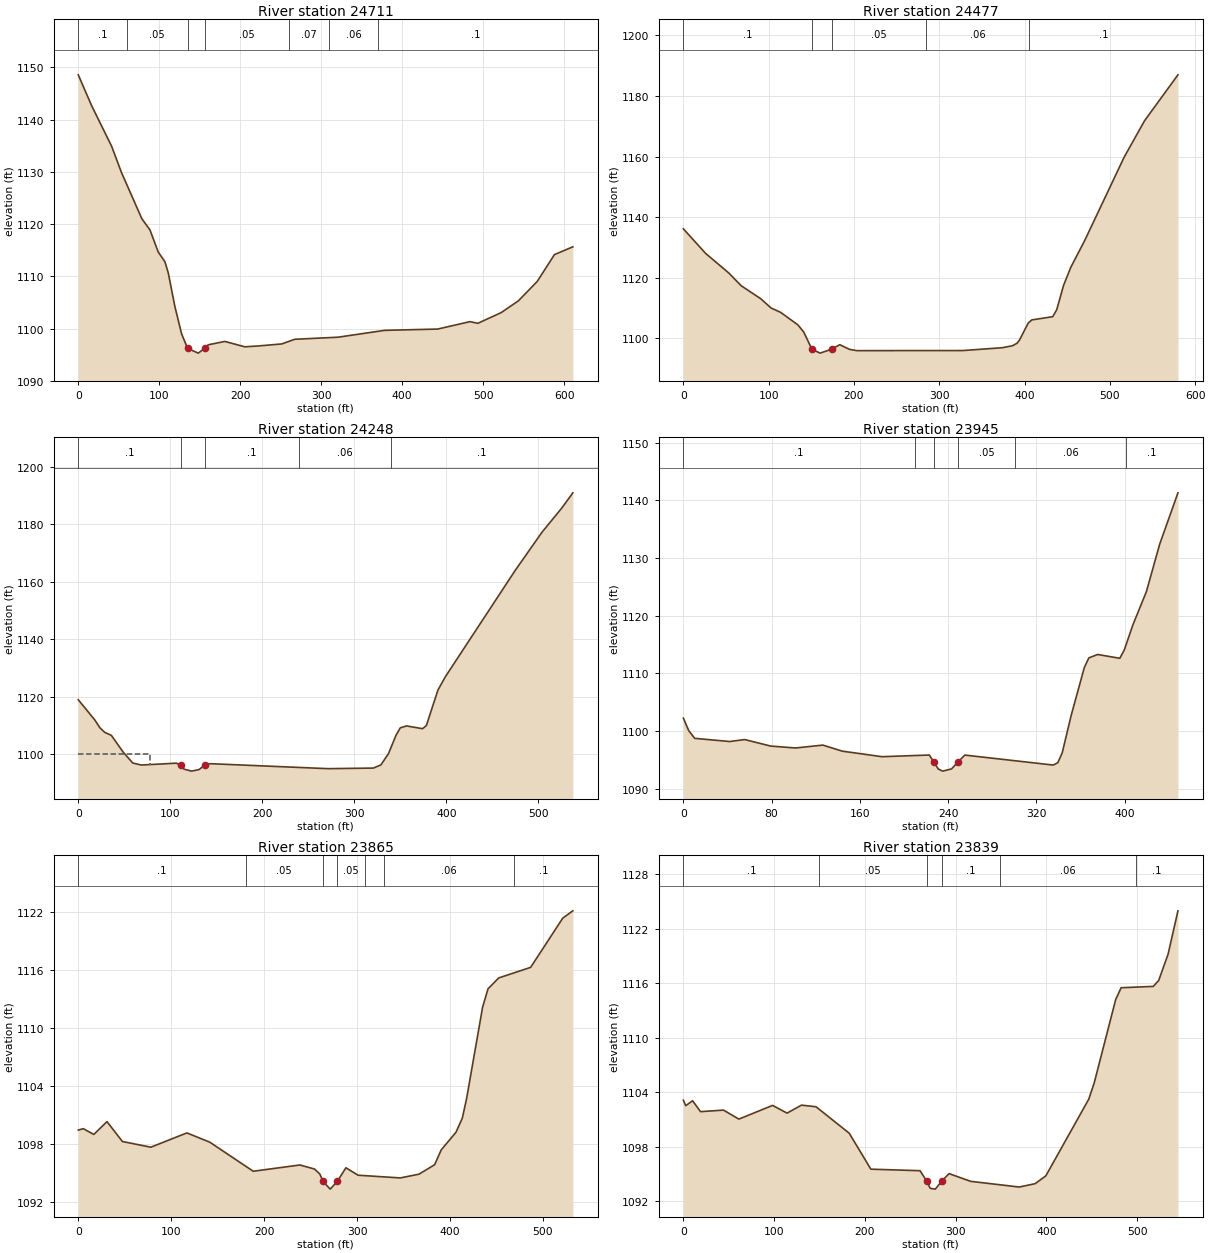
Type RM Length L Ch R = 1 ,24711   ,228.4,234.2,239.1
XS GIS Cut Line= 2
2182586.67906553754629.0916188762182445.29339335755223.350885124
#Sta/Elev= 30
       0 1148.59    16.5 1142.68    41.2 1134.91    53.5 1129.83    78.5 1121.04
    88.5  1118.9    98.8 1114.64     107  1112.8   111.1 1110.69   119.3 1104.23
   127.6 1098.98     135 1096.22   148.1 1095.29   156.3 1096.22   160.4 1096.88
     181 1097.53   205.7  1096.5   222.1 1096.66   251.3 1097.05   267.3 1097.94
   320.8 1098.34   378.4 1099.65   443.9  1099.9   483.8 1101.32   493.5    1101
   522.3 1103.05   543.5  1105.3   566.8 1109.02   588.1 1114.16   610.8 1115.65
#Mann= 7 ,-1,0
       0      .1       0      60     .05       0     135    .045       0
   156.3     .05       0     260     .07       0     310     .06       0
     370      .1       0
Bank Sta=135,156.3
XS Rating Curve= 0 ,0
Exp/Cntr=0.3,0.1

Type RM Length L Ch R = 1 ,24477   ,233.4,229.1,222
XS GIS Cut Line= 4
2182428.46783116754551.4444297012182398.04430023754597.079726099
2182188.88252507754915.259153765     2182153.543      755055.111
#Sta/Elev= 30
       0 1136.12    26.1 1128.01    53.4 1121.49    67.8 1117.32    90.9    1113
   102.8 1109.97     114 1108.54   134.3 1104.39   141.1 1102.05   150.7 1096.36
   160.3 1095.06  173.71 1096.35   183.4 1097.85   194.9 1096.29   203.4 1095.88
   327.8 1095.91     374 1096.85   385.9  1097.5   391.3 1098.34   394.2 1099.42
   404.4 1105.02   408.6 1106.03   433.1  1107.1   437.8 1109.42   445.8 1117.46
   454.2 1123.36   470.7 1132.33   516.8 1159.77   540.7  1171.8   579.9 1186.99
#Mann= 5 ,-1,0
       0      .1       0   150.7    .045       0  173.71     .05       0
  284.85     .06       0  404.85      .1       0
Bank Sta=150.7,173.71
XS Rating Curve= 0 ,0
Exp/Cntr=0.3,0.1

Type RM Length L Ch R = 1 ,24248   ,300.3,302.8,290.2
XS GIS Cut Line= 6
2182194.86279242 754474.88369798 2182169.8435173754505.525405986
2182152.26047832754528.5652501612182145.95456819754548.759400074
2182078.29045228754828.0832244442182029.99784936754980.899076625
#Sta/Elev= 30
       0 1118.88    17.8 1111.91    23.6 1109.09    28.8 1107.51    35.9 1106.49
    48.9 1100.59    59.2 1096.84    68.5 1096.13   106.6 1096.78   111.4  1096.1
   114.8 1094.71   123.1 1094.01   131.3 1094.56  137.37 1096.11   143.6  1096.6
   271.2 1094.87   320.6 1095.07   328.8 1096.17   337.1 1100.11   345.3 1106.54
   349.9 1109.09   356.6 1109.76   374.1  1108.8   378.2 1109.87   390.8 1122.24
   398.8 1126.86   474.7 1163.91   504.1 1177.34   525.1 1185.55   537.4 1190.97
#Mann= 5 ,-1,0
       0      .1       0   111.4    .045       0  137.37      .1       0
   239.7     .06       0   339.7      .1       0
#XS Ineff= 2 , 0
           77.97 1099.92
Permanent Ineff=
       F       F
Bank Sta=111.4,137.37
XS Rating Curve= 0 ,0
Exp/Cntr=0.3,0.1

Type RM Length L Ch R = 1 ,23945   ,68.8,80,83.9
XS GIS Cut Line= 3
2182083.84062819754462.3791347092181924.95595558754601.101794958
2181904.81230757754837.704948518
#Sta/Elev= 30
       0 1102.25     4.9 1100.07    10.3 1098.75      42  1098.2    55.6 1098.54
    79.2 1097.41   101.6 1097.08   126.5 1097.58   144.1 1096.53   180.1 1095.57
     223 1095.86   227.1 1094.62   231.1 1093.44   235.1 1093.07   243.1 1093.45
   248.81094.621   255.2 1095.85   335.4 1094.12   339.5 1094.54   343.5 1096.25
   351.5 1102.65   363.5 1111.01   367.6 1112.69   375.6 1113.28   395.7 1112.62
   399.7 1114.04   407.7 1118.48   419.8 1124.17   431.8 1132.37   448.4 1141.29
#Mann= 6 ,-1,0
       0      .1       0     210     .05       0   227.1    .045       0
   248.8     .05       0  300.92     .06       0  400.92      .1       0
Bank Sta=227.1,248.8
XS Rating Curve= 0 ,0
Exp/Cntr(USF)=0,0
Exp/Cntr=0.3,0.1

Type RM Length L Ch R = 1 ,23865   ,27.5,25.7,26.8
XS GIS Cut Line= 4
2182056.65476687754470.103994529 2181876.1684344754625.959499146
2181770.40072868754733.0745641732181667.54223888754832.704607747
#Sta/Elev= 30
       0 1099.42     5.4 1099.57    16.7 1098.97    30.9  1100.3    47.5 1098.24
    78.1 1097.65   116.9 1099.13   141.5 1098.17   188.3 1095.16   238.5 1095.81
   254.2 1095.39   259.9 1094.88   263.4 1094.11   271.1 1093.31  278.74 1094.11
     288 1095.52   301.1 1094.75   346.6 1094.47   366.7 1094.86   383.5 1095.84
   390.6 1097.38   406.4 1099.19   413.3 1100.67   417.9  1102.7   435.1 1112.15
   440.9 1114.04   452.4 1115.17   486.8 1116.27   521.4 1121.37   532.2 1122.12
#Mann= 7 ,-1,0
       0      .1       0     180     .05       0   263.4    .045       0
  278.74     .05       0  308.47      .1       0  328.47     .06       0
     469      .1       0
Bank Sta=263.4,278.74
XS Rating Curve= 0 ,0
Exp/Cntr=0.3,0.1

Type RM Length L Ch R = 1 ,23839   ,188.3,182.4,164
XS GIS Cut Line= 4
2182034.14351494754452.7211548732181885.06910554754583.289204361
2181820.35139587754646.2607363632181631.12742735754819.479625615
#Sta/Elev= 30
       0 1103.11     2.6 1102.51    10.2 1103.05    18.9 1101.85    44.2 1102.02
    61.2 1101.03    98.3 1102.54   114.3 1101.69   130.2 1102.57   146.2 1102.39
   182.8 1099.47   206.6 1095.51   260.8 1095.34     268 1094.23     272  1093.4
   277.6 1093.31  285.25 1094.25   292.8 1095.02   316.5 1094.17   370.1 1093.54
   387.6 1093.91   399.4 1094.77   446.8 1103.24   452.7 1105.01   476.4 1114.21
   482.4 1115.51   517.9 1115.66   523.8 1116.32   534.1  1119.2     545 1123.99
#Mann= 6 ,-1,0
       0      .1       0     150     .05       0     268    .045       0
  285.25      .1       0  348.47     .06       0  498.47      .1       0
Bank Sta=268,285.25
XS Rating Curve= 0 ,0
Exp/Cntr=0.3,0.1

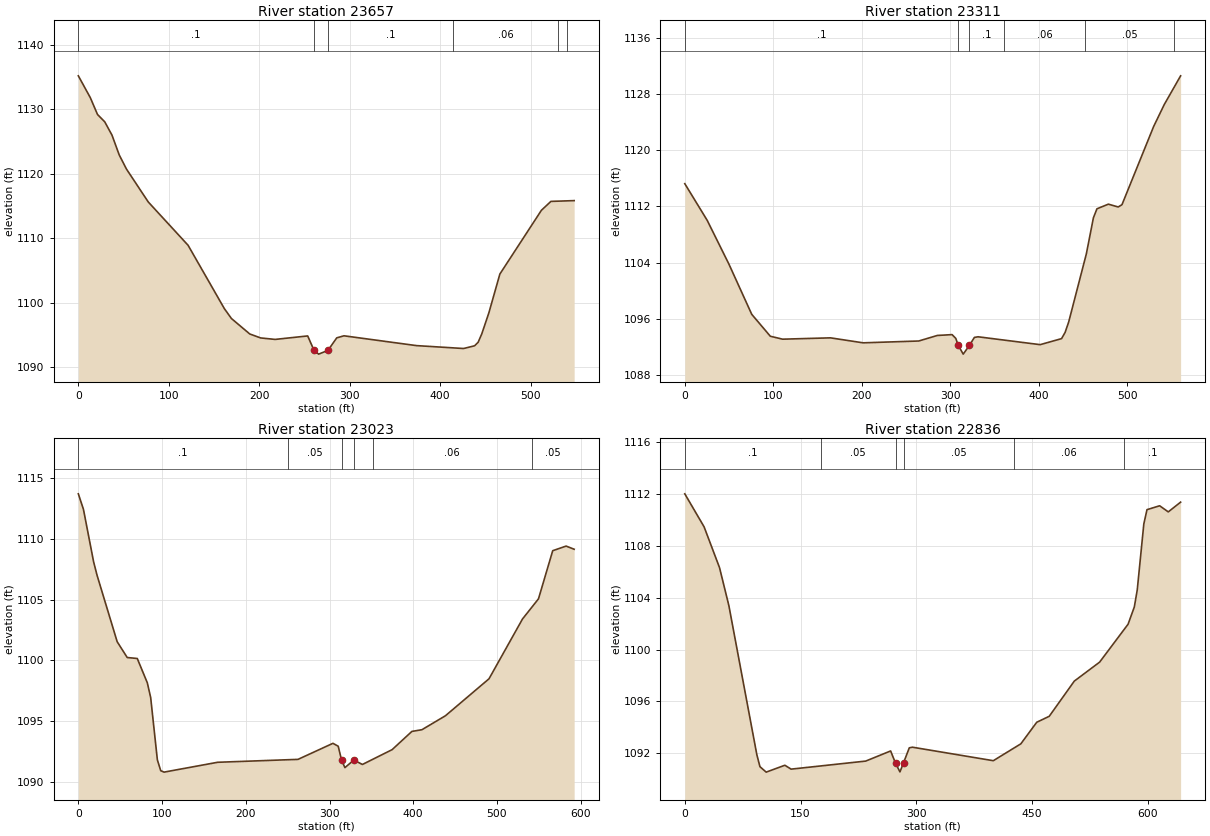
Type RM Length L Ch R = 1 ,23657   ,338.3,346.3,340.2
XS GIS Cut Line= 4
2181709.77532547754280.0177044452181690.72348331754623.963544426
2181682.93249305754749.0203645532181621.10991904754796.874655686
#Sta/Elev= 30
       0 1135.16    13.2 1131.79    21.2 1129.17    29.2 1128.03    37.2 1125.97
    45.2  1122.9    53.2 1120.71    77.3 1115.61   121.3  1108.9   161.4 1099.08
   169.2 1097.55   189.5 1095.15   201.5 1094.54   217.5 1094.31   253.5 1094.85
   260.5 1092.61   265.6 1092.03   275.9 1092.61   285.6 1094.55   293.6 1094.87
   373.7 1093.35   425.8  1092.9   437.9 1093.32   441.9 1093.87   445.9 1095.17
   453.7 1098.41   465.9 1104.44   511.8 1114.32   522.3  1115.7     548 1115.82
#Mann= 6 ,-1,0
       0      .1       0   260.5    .045       0   275.9      .1       0
  414.47     .06       0  529.77      .1       0  539.77     .05       0
Bank Sta=260.5,275.9
XS Rating Curve= 0 ,0
Exp/Cntr=0.3,0.1

Type RM Length L Ch R = 1 ,23311   ,288.9,288,284.1
XS GIS Cut Line= 4
2181562.72068894  754348.96720712181498.95677104754550.424223051
2181447.53649658754714.2712756852181454.57898059 754891.74187279
#Sta/Elev= 30
       0 1115.25    25.4 1110.01      50 1103.76    75.7 1096.63    96.7 1093.51
   110.6 1093.09   164.7 1093.28   201.6 1092.57   264.5 1092.83   285.5 1093.62
   302.2 1093.74   306.4  1093.2   309.21092.202   314.8 1090.96  321.86 1092.21
   327.4 1093.34   331.6 1093.43   401.8 1092.31     426 1093.17     430 1094.06
     434 1095.52     454 1105.24     462 1110.39     466 1111.67   478.9 1112.33
     490 1111.93   494.3 1112.26   530.1  1123.4   542.1 1126.53   560.6 1130.62
#Mann= 6 ,-1,0
       0      .1       0   309.2    .045       0  321.86      .1       0
  361.31     .06       0  453.03     .05       0  553.03      .1       0
Bank Sta=309.2,321.86
XS Rating Curve= 0 ,0
Exp/Cntr=0.3,0.1

Type RM Length L Ch R = 1 ,23023   ,185.9,186.2,183
XS GIS Cut Line= 3
  2181280.404266754242.8297897042181282.93956025754534.388627806
2181271.53073615754834.820995762
#Sta/Elev= 30
       0 1113.71     6.1 1112.44    18.3  1108.1    22.4    1107    46.4 1101.54
    58.4 1100.24    70.4 1100.16    82.4 1098.16    86.4 1096.95    94.4 1091.82
    98.4 1090.93   102.4 1090.81   166.4 1091.62   262.4 1091.86   304.1 1093.18
   310.4 1092.94   314.4  1091.8   318.4 1091.18     329  1091.8   339.3 1091.44
   374.8 1092.66   398.4 1094.16   410.4  1094.3   438.5 1095.45   490.5 1098.49
   530.5 1103.41   549.6 1105.07   566.6 1109.03   582.6 1109.41   592.2 1109.15
#Mann= 6 ,-1,0
       0      .1       0     250     .05       0   314.4    .045       0
     329     .05       0  351.57     .06       0  541.57     .05       0
Bank Sta=314.4,329
XS Rating Curve= 0 ,0
Exp/Cntr=0.3,0.1

Type RM Length L Ch R = 1 ,22836   ,428.6,433.8,428.9
XS GIS Cut Line= 5
2181089.15387518754224.2266769372181092.12444882754270.349436454
2181147.33887809754710.2425835812181176.54974716754840.790641435
2181161.42384611754852.823149894
#Sta/Elev= 30
       0 1111.99      25 1109.45      45 1106.31    57.1 1103.39    93.4  1091.9
    97.4 1090.98   105.5 1090.56   129.7 1091.09   137.8 1090.79   234.5 1091.41
   266.8 1092.19   273.31091.227   278.9 1090.58   283.51091.274     291 1092.43
     295 1092.48   399.9 1091.44   435.6 1092.74   456.2  1094.4   472.4 1094.86
   504.9 1097.57   537.7 1099.03   574.6 1101.95   582.7 1103.28   586.5  1104.6
     595 1109.67   599.1 1110.77   615.5 1111.07   626.7  1110.6   642.7 1111.35
#Mann= 6 ,-1,0
       0      .1       0  176.22     .05       0   273.3    .045       0
   283.5     .05       0  426.22     .06       0  569.56      .1       0
Bank Sta=273.3,283.5
XS Rating Curve= 0 ,0
Exp/Cntr=0.3,0.1