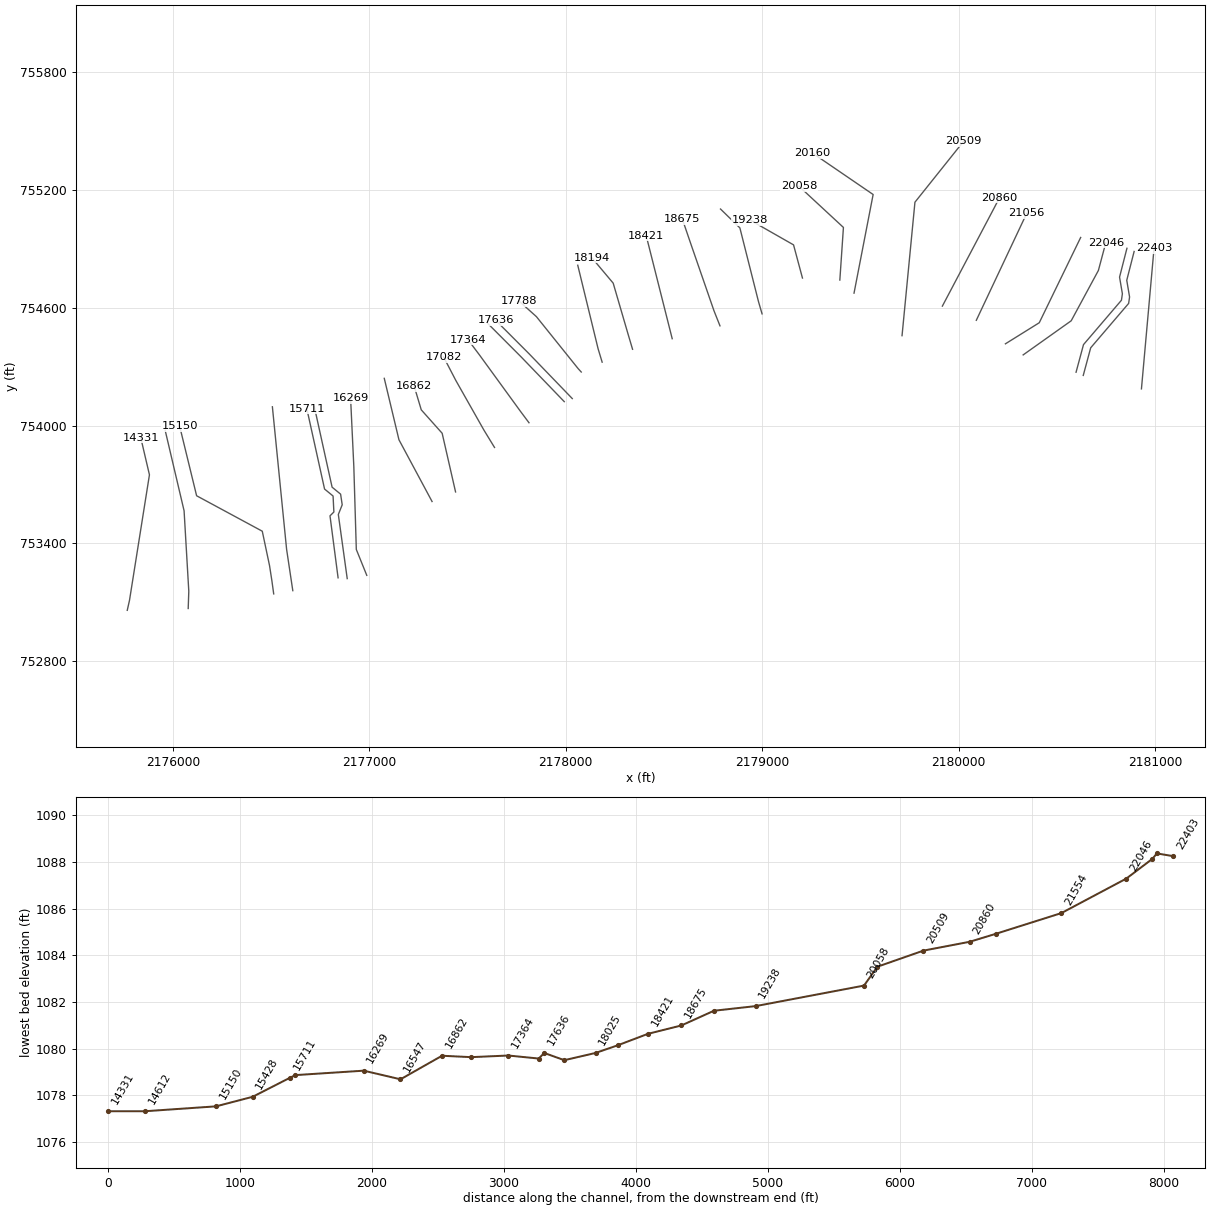
HEC-RAS study HACKERSCK.prj: HACKERSCK

--- HACKERSCK.g01 (geometry) --- (continued)

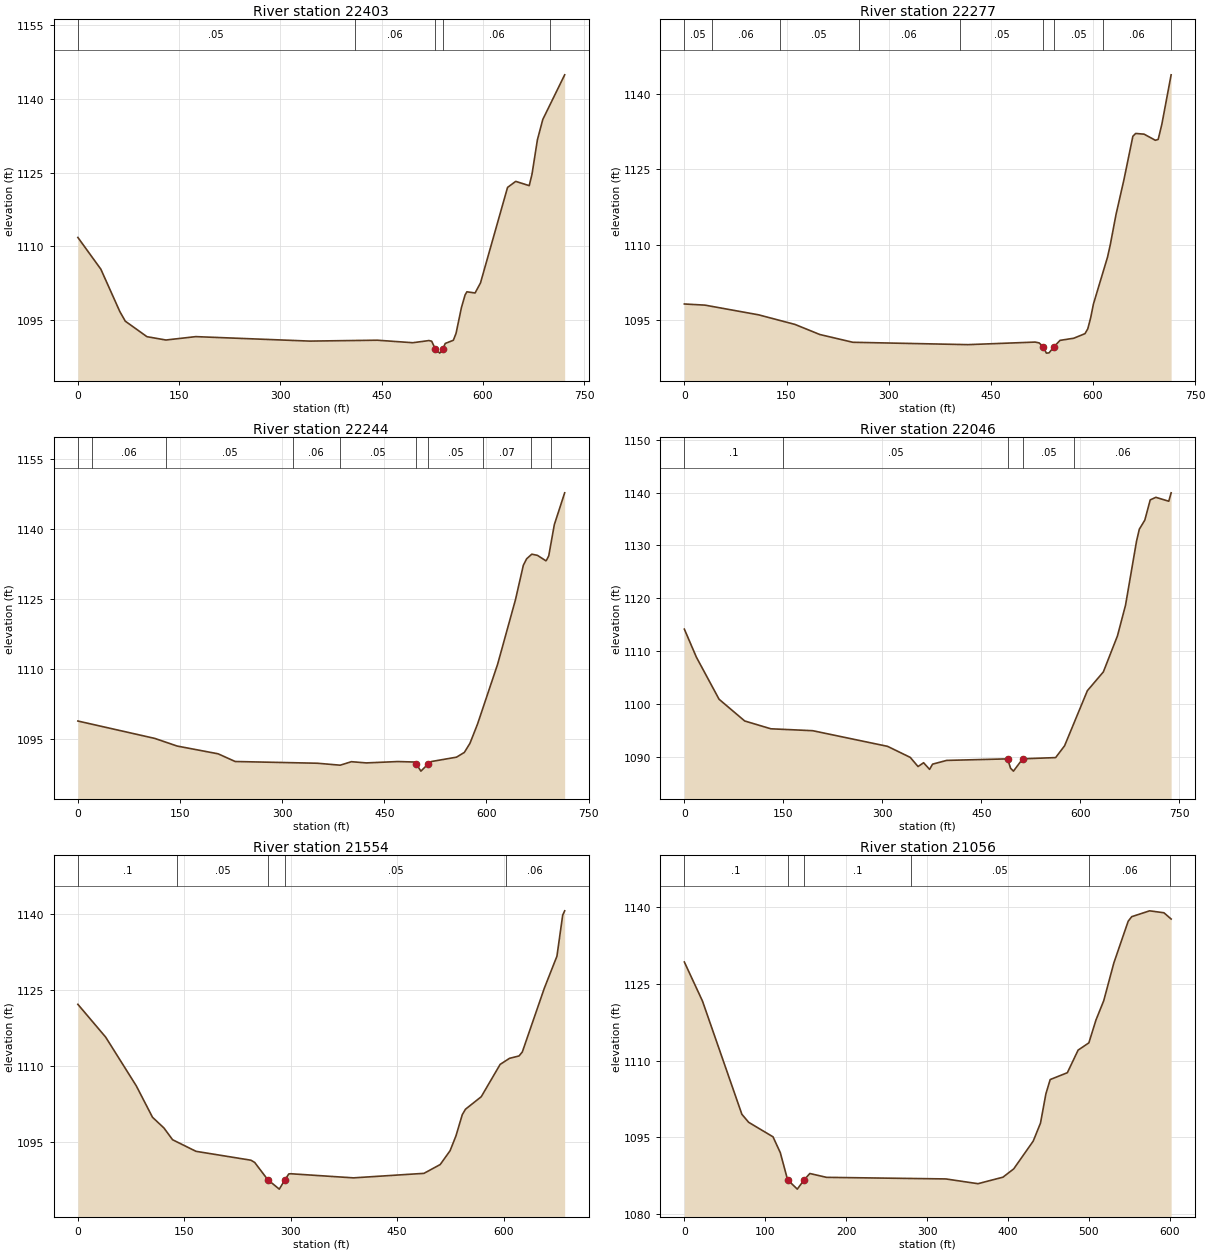
Type RM Length L Ch R = 1 ,22403   ,122.1,125.4,127.1
XS GIS Cut Line= 2
2180931.65496456754187.2991613842180995.99370739754905.458642125
#Sta/Elev= 30
       0 1111.81      34 1105.35    62.1 1096.73    70.2 1094.76   102.3  1091.6
   130.4 1090.92   174.6 1091.61   343.2  1090.7   443.6 1090.88   496.1 1090.37
     520 1090.81     524 1090.68   529.3 1089.13     536 1088.25  540.72 1089.13
   544.1 1090.22   556.1 1090.87   560.1 1092.27   568.1 1097.53   573.5  1100.1
   576.2 1100.74   588.3  1100.5   596.3 1102.54   636.4    1122   648.5 1123.23
   668.5 1122.36   672.6 1124.68   680.6 1131.68   688.6 1135.84     721 1144.93
#Mann= 5 ,-1,0
       0     .05       0     410     .06       0   529.3    .045       0
  540.72     .06       0     700      .1       0
Bank Sta=529.3,540.72
XS Rating Curve= 0 ,0
Exp/Cntr=0.3,0.1

Type RM Length L Ch R = 1 ,22277   ,33.4,33.3,34.1
XS GIS Cut Line= 6
2180635.30873413754255.9404367462180673.20998989754396.706962678
 2180866.4289792754622.7972323212180871.23941047754655.668512659
2180856.80811666754740.6527984112180894.41149678754887.570250259
#Sta/Elev= 30
       0 1098.16    30.3 1097.93     109    1096   162.4 1094.09   198.9 1092.08
   247.4 1090.53   416.4 1090.06   515.1 1090.57   520.9 1090.41   526.8 1089.67
   531.6 1088.37   535.5 1088.42  543.13 1089.68   551.6 1090.91   571.9 1091.34
   588.3 1092.25   592.4 1093.21   596.6 1095.38   600.7 1098.15   621.4 1107.49
   625.5    1110   633.8 1115.94   645.5 1122.92   658.6 1131.56   662.7 1132.13
   675.1 1131.99   691.7 1130.77   695.8 1130.95   701.2 1133.98   714.8 1143.81
#Mann= 9 ,-1,0
       0     .05       0      40     .06       0     140     .05       0
  255.78     .06       0  404.41     .05       0   526.8    .045       0
  543.13     .05       0  615.32     .06       0  714.82      .1       0
Bank Sta=526.8,543.13
XS Rating Curve= 0 ,0
Exp/Cntr=0.3,0.1

Type RM Length L Ch R = 1 ,22244   ,205.9,198.2,185.4
XS GIS Cut Line= 6
2180598.68069251754272.2445856942180636.58194828754413.011111626
2180829.80093758754639.1013812682180834.61136885754671.972661607
2180820.18007505754756.9569473582180857.78345517754903.874399207
#Sta/Elev= 30
       0 1098.87   112.8 1095.15   145.8 1093.51   205.9 1091.85     231  1090.2
   351.7 1089.83   385.2 1089.41   401.6 1090.16   423.5  1089.9     470 1090.19
   494.4 1090.09     4971089.649   503.7 1088.14   514.1 1089.64   518.9 1090.19
     556 1091.13   567.5 1092.15   575.7 1094.09   586.8  1098.2   616.3 1111.01
   642.5 1124.82   654.1 1132.22   658.9  1133.6   666.5  1134.6   674.8 1134.35
   687.2 1133.19   688.4 1133.38   691.4 1134.24   699.6 1140.92   714.8 1147.74
#Mann= 10 ,-1,0
       0     .05       0      20     .06       0     130     .05       0
  315.78     .06       0  384.41     .05       0     497    .045       0
   514.1     .05       0  595.32     .07       0  665.32     .06       0
  695.32      .1       0
Bank Sta=497,514.1
XS Rating Curve= 0 ,0
Exp/Cntr=0.3,0.1

Type RM Length L Ch R = 1 ,22046   ,483.8,491.9,483
XS GIS Cut Line= 4
2180329.30059342754360.5477649342180573.93274382754534.402382441
2180712.41836593754790.8573369512180749.96134216754931.804232082
#Sta/Elev= 30
       0 1114.16    18.2 1108.86    52.6 1100.89    91.4 1096.78   131.1  1095.3
   194.4 1094.94   307.8 1091.98   342.2 1089.89     354 1088.16   362.4 1088.88
   371.5 1087.62     376 1088.61   397.4 1089.32   489.7 1089.61   494.2 1087.83
   498.5 1087.29  512.57 1089.62   562.4 1089.85     576 1092.09   610.5 1102.51
   634.7 1106.06   656.1 1112.89   668.3 1118.69     685 1130.82   689.2 1133.07
   697.5 1134.78   705.7 1138.61   714.2  1139.1   733.8 1138.36   737.4 1139.95
#Mann= 5 ,-1,0
       0      .1       0     150     .05       0   489.7    .045       0
  512.57     .05       0  590.12     .06       0
Bank Sta=489.7,512.57
XS Rating Curve= 0 ,0
Exp/Cntr=0.3,0.1

Type RM Length L Ch R = 1 ,21554   ,487.7,497.3,489.6
XS GIS Cut Line= 3
2180238.91963004 754417.019804352180411.29341718754524.452769358
2180622.15065447754958.995060656
#Sta/Elev= 30
       0 1122.23    39.2 1115.76    82.3 1106.17   105.2 1099.97   121.3 1097.86
   133.5 1095.54   166.5 1093.26   243.9 1091.51   249.2 1091.07  267.76 1087.65
   283.9 1085.81   291.81087.643   297.3 1088.81   300.1 1088.84   388.4 1088.03
   487.8 1088.92   510.7 1090.66   524.6 1093.38   532.9 1096.31   541.8 1100.49
   546.3 1101.56   568.5 1104.02   595.2  1110.4   608.4 1111.59   621.8 1112.06
   626.4 1112.84   657.4  1125.4   675.2 1131.72   683.3  1139.8   686.1 1140.66
#Mann= 5 ,-1,0
       0      .1       0     140     .05       0  267.76    .045       0
   291.8     .05       0  603.11     .06       0
Bank Sta=267.76,291.8
XS Rating Curve= 0 ,0
Exp/Cntr(USF)=0,0
Exp/Cntr=0.3,0.1

Type RM Length L Ch R = 1 ,21056   ,196,196.5,194.6
XS GIS Cut Line= 2
2180090.66471851754536.8689590932180347.03582236755081.236127903
#Sta/Elev= 30
       0 1129.25    22.4 1121.63    71.1 1099.53    79.5 1097.96   109.6 1095.13
   118.6 1092.04   127.6 1086.75   139.6 1084.92  148.18 1086.75   155.1 1087.97
   175.7 1087.22   323.1 1086.91   362.9 1085.98   393.8 1087.25   407.1 1088.87
   431.2 1094.29   440.2  1097.8   446.9 1103.53   452.2 1106.31   473.4 1107.64
   486.7 1112.05     500 1113.47   508.8 1117.94   518.4 1121.71   530.9 1129.08
   548.6 1137.21     553  1138.1   575.1 1139.24   592.8 1138.86   601.7 1137.64
#Mann= 6 ,-1,0
       0      .1       0   127.6    .045       0  148.18      .1       0
     280     .05       0     500     .06       0     600      .1       0
Bank Sta=127.6,148.18
XS Rating Curve= 0 ,0
Exp/Cntr=0.3,0.1

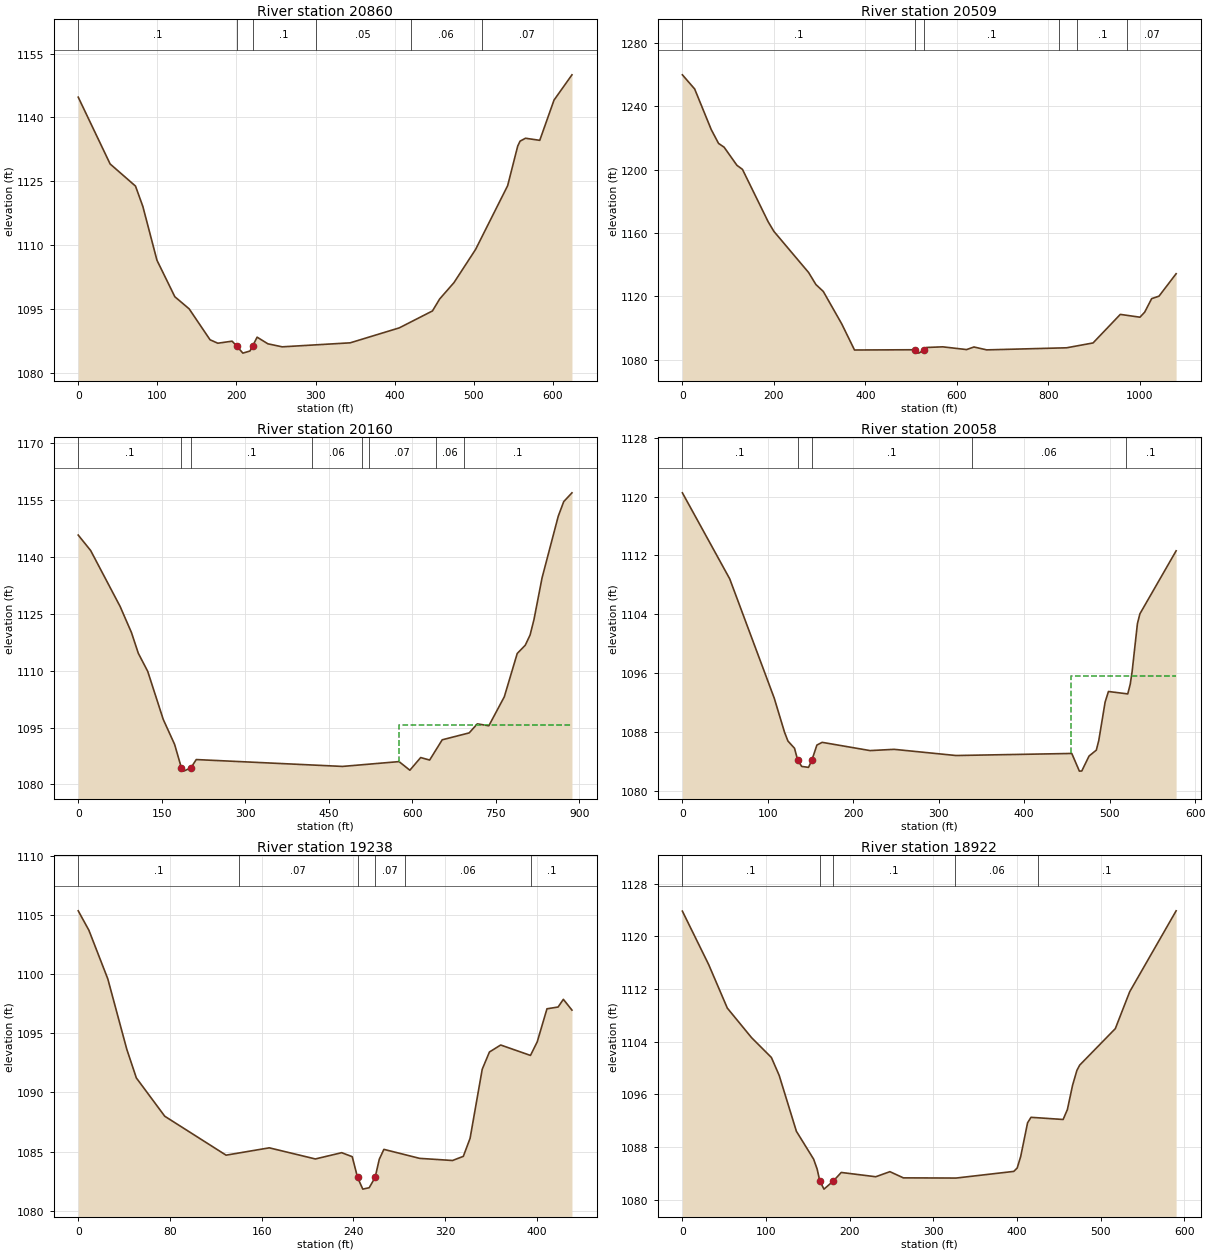
Type RM Length L Ch R = 1 ,20860   ,343.9,351.1,355.3
XS GIS Cut Line= 3
 2179917.8189199754609.1404477932180182.50363902755111.128708177
     2180208.509      755161.277
#Sta/Elev= 30
       0 1144.76    40.3 1129.06    72.4 1123.85    81.7 1119.05    99.5 1106.42
   122.1 1097.84   140.2 1094.99   166.6 1087.72   176.4 1086.91   194.5 1087.39
   200.1 1086.27   208.1 1084.58   217.1 1085.08  220.45 1086.25   226.1 1088.33
   239.7 1086.77   257.8 1086.06   343.7    1087   405.8 1090.52   447.7  1094.5
   456.8 1097.31   474.9 1101.16   502.2 1108.96   542.7 1123.94   555.4 1133.23
   558.4 1134.42   565.3  1135.1   583.3 1134.61   601.3 1144.06     624 1150.01
#Mann= 6 ,-1,0
       0      .1       0   200.1    .045       0  220.45      .1       0
     300     .05       0     420     .06       0     510     .07       0
Bank Sta=200.1,220.45
XS Rating Curve= 0 ,0
Exp/Cntr=0.3,0.1

Type RM Length L Ch R = 1 ,20509   ,345.6,348.8,340.5
XS GIS Cut Line= 3
     2179712.386        754458.4 2179778.1171549755138.717605483
2180025.57714731755448.587786828
#Sta/Elev= 30
       0 1259.71    26.9 1250.76    63.1 1225.18    79.1 1216.46    91.2 1214.09
   119.3 1202.65   131.4 1200.08   187.6 1167.06   200.2 1160.97   276.1 1135.03
   292.1 1127.44   308.2 1123.11   348.4 1102.72   376.5 1086.17   508.1 1086.33
   517.2  1084.2  528.47 1086.31   533.7 1087.76   569.4 1088.17   621.7 1086.44
   637.7 1088.07   665.6 1086.25   840.4 1087.56   898.3 1090.62   957.9 1108.63
  1000.9 1106.86  1011.2 1110.02  1026.5 1118.57  1042.5 1120.11    1080 1134.27
#Mann= 6 ,-1,0
       0      .1       0   508.1    .045       0  528.47      .1       0
  823.49     .06       0  863.49      .1       0  973.49     .07       0
Bank Sta=508.1,528.47
XS Rating Curve= 0 ,0
Exp/Cntr=0.3,0.1

Type RM Length L Ch R = 1 ,20160   ,99.8,101.5,103.2
XS GIS Cut Line= 3
2179467.87861366754675.2780532562179565.18853778755177.904443295
2179255.85065728755389.448939601
#Sta/Elev= 30
       0 1145.75    22.3 1141.68    75.3 1126.91    95.6 1120.05   107.9 1114.59
   124.8 1109.82   152.7 1097.14   173.1 1090.56   185.3 1084.37   189.4 1083.51
  202.26 1084.37     212 1086.56   474.6 1084.75   576.2 1086.02   595.6 1083.75
     615 1087.09   631.1 1086.43   653.7 1091.77   702.1 1093.59   716.7 1095.97
   737.4 1095.47   765.2 1103.11   788.4 1114.53   802.8  1116.7   811.5  1119.4
   818.5 1123.49     833 1134.47   862.1 1150.73   871.9 1154.57   886.7 1156.89
#Mann= 8 ,-1,0
       0      .1       0   185.3    .045       0  202.26      .1       0
     420     .06       0     510      .1       0  521.96     .07       0
  641.96     .06       0  691.96      .1       0
#XS Ineff= 2 , 0
                          576.49         1095.71
Permanent Ineff=
       F       F
Bank Sta=185.3,202.26
XS Rating Curve= 0 ,0
Exp/Cntr=0.3,0.1

Type RM Length L Ch R = 1 ,20058   ,795.1,820.2,821
XS GIS Cut Line= 3
2179395.63056271754741.9496429942179413.88468127 755010.05700934
2179187.24346079755220.182822315
#Sta/Elev= 30
       0 1120.51    55.4 1108.82   107.5 1092.61   119.5    1088   123.5 1086.79
   131.2 1085.81   134.9 1084.21   139.6 1083.34   147.6 1083.21  151.59  1084.2
  151.59 1084.21   157.4 1086.24   163.6 1086.61   219.7 1085.49   247.8 1085.66
   320.2 1084.82   455.7  1085.1   464.6  1082.7   467.4 1082.72   475.9 1084.75
   484.4 1085.55   487.3 1086.87   494.7 1092.08   498.6 1093.52   521.2 1093.19
   524.1 1094.51   526.3 1096.22   532.5 1102.73   535.4 1104.07   577.8 1112.63
#Mann= 5 ,-1,0
       0      .1       0   134.9    .045       0  151.59      .1       0
  338.73     .06       0  518.73      .1       0
#XS Ineff= 2 , 0
                          455.07         1095.67
Permanent Ineff=
       F       F
Bank Sta=134.9,151.59
XS Rating Curve= 0 ,0
Exp/Cntr(USF)=0,0
Exp/Cntr=0.3,0.1

Type RM Length L Ch R = 1 ,19238   ,324.1,316.6,306.4
XS GIS Cut Line= 3
2179205.23935494754752.2254096662179159.85445797 754921.24502596
2178937.62496247 755048.00973818
#Sta/Elev= 30
       0 1105.34     9.3  1103.7    25.8 1099.59    42.4 1093.63    50.7 1091.22
    75.5 1087.98     129 1084.69   166.7 1085.31   206.9 1084.37   229.9  1084.9
   239.1 1084.56   243.7 1082.81   248.3 1081.82   253.9 1081.94  259.05 1082.81
   262.7 1084.35   266.7 1085.18   297.9 1084.42   326.6 1084.24     336 1084.59
   341.9 1086.11   352.5 1091.95   358.8 1093.41   368.6    1094   394.6 1093.12
   400.5 1094.27     409 1097.06   418.7 1097.21   423.3 1097.86   430.8 1096.95
#Mann= 6 ,-1,0
       0      .1       0     140     .07       0   243.7    .045       0
  259.05     .07       0  285.01     .06       0  395.01      .1       0
Bank Sta=243.7,259.05
XS Rating Curve= 0 ,0
Exp/Cntr(USF)=0,0
Exp/Cntr=0.3,0.1

Type RM Length L Ch R = 1 ,18922   ,245.2,246.5,246.7
XS GIS Cut Line= 4
2178999.50286847754569.6166917482178981.24874992754632.365224296
2178886.55550989755007.7155371742178787.87622391755103.972208652
#Sta/Elev= 30
       0 1123.81    31.4 1115.71    53.7  1109.1    82.7 1104.61   106.4  1101.6
   115.7 1098.89   136.3  1090.4   156.9 1086.17   161.1 1084.67   164.31082.844
   169.3 1081.62  180.39 1082.84   189.9 1084.15   231.2  1083.5   248.1 1084.27
   264.2 1083.33   327.2  1083.3   396.2 1084.31   400.3 1084.83   404.5 1086.59
   412.7 1091.69   416.8 1092.52   455.2 1092.19   460.3  1093.7   466.5 1097.39
   471.7 1099.65     475 1100.44   517.6 1105.98   534.8 1111.58   590.3 1123.86
#Mann= 5 ,-1,0
       0      .1       0   164.3    .045       0  180.39      .1       0
  325.35     .06       0  425.35      .1       0
Bank Sta=164.3,180.39
XS Rating Curve= 0 ,0
Exp/Cntr=0.3,0.1

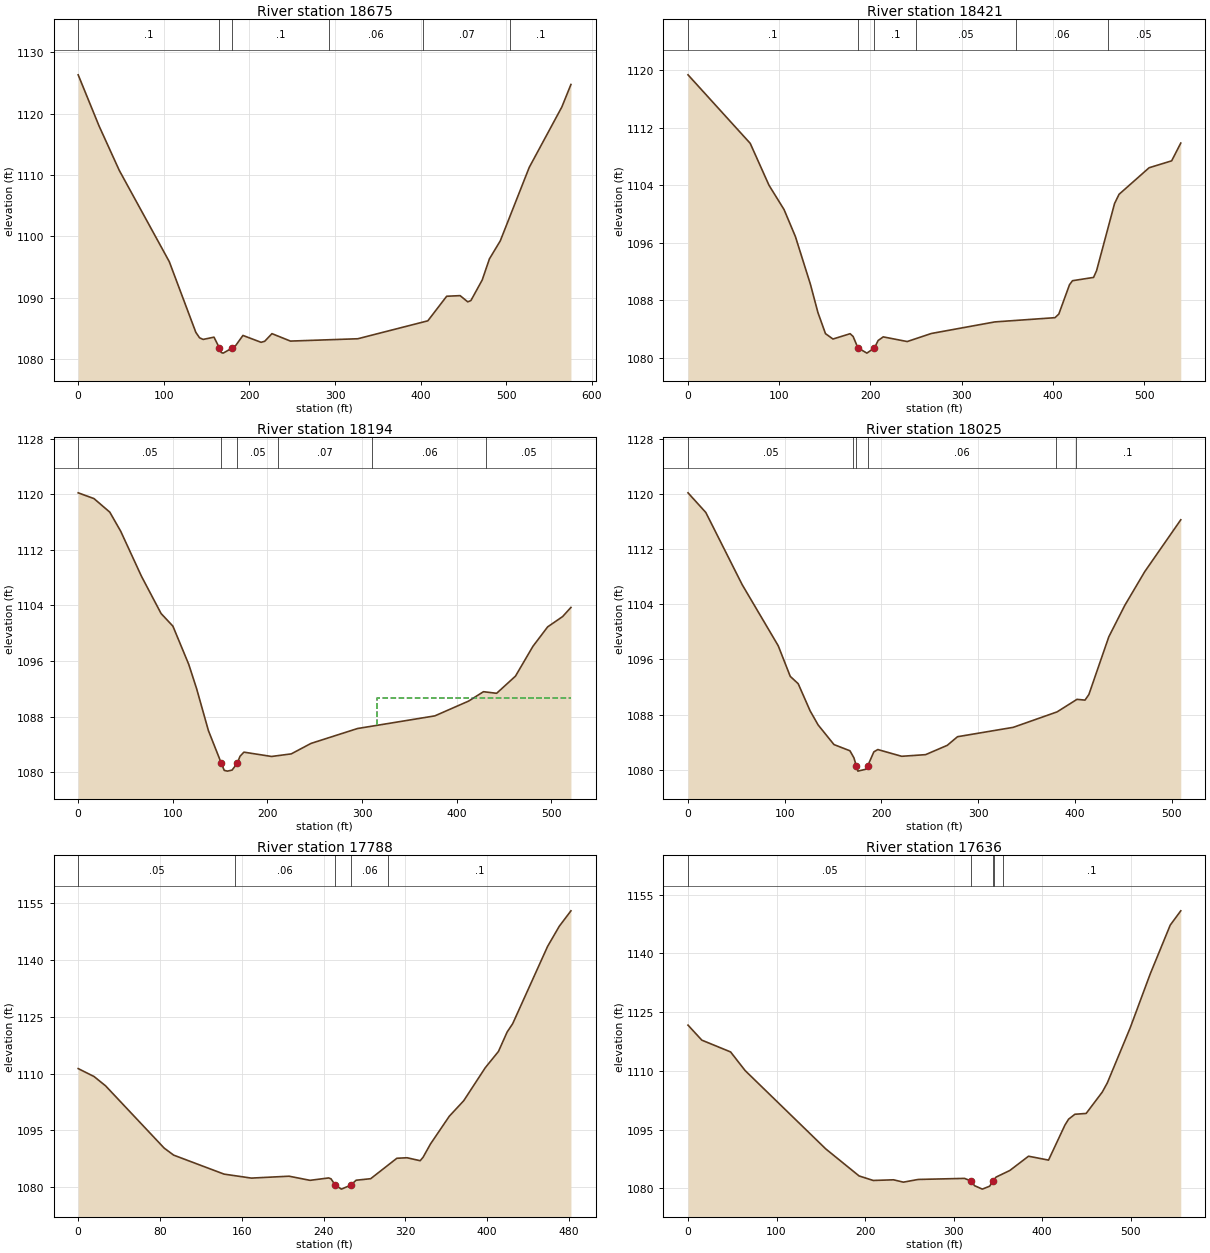
Type RM Length L Ch R = 1 ,18675   ,252.4,253.6,251.2
XS GIS Cut Line= 4
2178785.16205057754508.6164323812178754.66626375754585.317956803
2178636.37957549754927.2404150692178593.94109831755051.256540992
#Sta/Elev= 30
       0  1126.3    24.3    1118      48 1110.74   106.4 1095.88   137.4 1084.37
   141.7 1083.49   145.9 1083.22   158.6 1083.59     1651081.809     167 1081.09
   169.3 1080.99   179.7 1081.81     184 1082.24   192.4 1083.87   213.6 1082.75
   217.8 1082.92   226.3 1084.16   247.9 1082.95   326.5 1083.33   408.3 1086.25
   430.3 1090.25     446 1090.35   454.9 1089.34   458.6 1089.55   471.8  1092.9
   480.2 1096.33   492.9 1099.27   526.7 1111.23   564.8 1121.07   575.4 1124.73
#Mann= 6 ,-1,0
       0      .1       0     165    .045       0   179.7      .1       0
  292.54     .06       0  402.54     .07       0  504.35      .1       0
Bank Sta=165,179.7
XS Rating Curve= 0 ,0
Exp/Cntr=0.3,0.1

Type RM Length L Ch R = 1 ,18421   ,225.6,227.9,226.5
XS GIS Cut Line= 2
2178541.86950265754443.069967885 2178409.7451784754966.864294065
#Sta/Elev= 30
       0 1119.33    68.2  1109.8    88.8 1103.97   105.3 1100.59   117.7 1096.85
   134.2  1090.2   142.4 1086.28   150.7 1083.34   158.9 1082.59   177.7 1083.33
     181 1082.95  186.21 1081.37   196.1 1080.63   204.41081.356   208.4 1082.38
     214 1082.89   240.3 1082.24   266.7 1083.36   336.3 1084.97   402.3 1085.56
   406.5 1086.06   418.2 1090.14   421.5  1090.7   444.6 1091.16   447.9  1092.1
   467.6 1101.43   472.5 1102.71   505.5 1106.41   530.2 1107.37   540.2 1109.84
#Mann= 6 ,-1,0
       0      .1       0  186.21    .045       0   204.4      .1       0
     250     .05       0     360     .06       0     460     .05       0
Bank Sta=186.21,204.4
XS Rating Curve= 0 ,0
Exp/Cntr=0.3,0.1

Type RM Length L Ch R = 1 ,18194   ,168.9,168.8,167.9
XS GIS Cut Line= 4
2178339.97875558754389.1582663732178316.97856619754466.728002309
  2178241.293568 754726.219424692178132.34043873754855.965135881
#Sta/Elev= 30
       0 1120.19    16.7 1119.36    33.4 1117.41    44.9 1114.67    66.8  1108.2
    87.6 1102.82   100.1    1101   116.8 1095.51   125.1 1092.02   137.6 1085.97
   151.3 1081.25   154.3 1080.25   157.7 1080.14   162.6 1080.29  167.96 1081.25
     171 1082.28   175.1 1082.87   204.3 1082.25   225.1 1082.62     246 1084.13
   295.1 1086.27   376.8 1088.09   412.5 1090.22   428.2 1091.57   442.1 1091.34
     462 1093.81   480.4 1098.09     496  1100.9   511.8 1102.38   520.6  1103.7
#Mann= 6 ,-1,0
       0     .05       0   151.3    .045       0  167.96     .05       0
  210.91     .07       0  310.91     .06       0  431.21     .05       0
#XS Ineff= 2 , 0
                          316.15         1090.64
Permanent Ineff=
       F       F
Bank Sta=151.3,167.96
XS Rating Curve= 0 ,0
Exp/Cntr=0.3,0.1

Type RM Length L Ch R = 1 ,18025   ,229.6,236.4,241
XS GIS Cut Line= 3
2178185.08214518754323.5357101872178164.60681871 754391.24284164
2178060.84005073754817.423705468
#Sta/Elev= 30
       0 1120.17    18.4 1117.32      56 1106.85    93.3 1097.98   105.7 1093.55
   113.9 1092.49   126.2 1088.56   134.5 1086.51   150.9 1083.66   167.4 1082.76
   171.5 1081.74     174 1080.57   175.6 1079.81   183.9 1080.09  185.75 1080.57
   192.1  1082.6   196.2 1082.94   220.9 1081.96   245.6  1082.2     268 1083.55
   278.6  1084.8   336.2 1086.16   381.5  1088.4   402.1 1090.22   410.4 1090.11
   414.4 1090.92     435 1099.29   451.5 1103.84   472.1 1108.73   509.4 1116.26
#Mann= 6 ,-1,0
       0     .05       0  170.74     .06       0     174    .045       0
  185.75     .06       0  380.74     .05       0  400.74      .1       0
Bank Sta=174,185.75
XS Rating Curve= 0 ,0
Exp/Cntr=0.3,0.1

Type RM Length L Ch R = 1 ,17788   ,151,152.7,153.5
XS GIS Cut Line= 4
2178078.61684381754273.2618239442178062.89765188754290.478081776
2177850.31429431754555.4587457892177761.77673322 754634.91278846
#Sta/Elev= 30
       0 1111.31    15.5 1109.22    26.8 1106.76    84.1 1090.33    93.4 1088.47
   142.7 1083.46   169.4 1082.41   206.3 1082.91   226.8 1081.82     245 1082.45
   247.3 1082.22   251.5 1080.55   257.5  1079.5  266.61 1080.55   271.9 1081.85
   286.1 1082.25   311.7 1087.64   321.7 1087.78   334.5    1087   337.3 1087.88
   344.7 1091.45     363 1098.73   377.1 1102.82   398.1  1111.5   411.1 1115.83
   419.6 1120.96     425 1123.15   459.2 1143.57   470.6 1148.87     482 1152.94
#Mann= 5 ,-1,0
       0     .05       0  153.31     .06       0   251.5    .045       0
  266.61     .06       0  303.31      .1       0
Bank Sta=251.5,266.61
XS Rating Curve= 0 ,0
Exp/Cntr=0.3,0.1

Type RM Length L Ch R = 1 ,17636   ,40.6,41.2,41
XS GIS Cut Line= 3
2178032.93897146754137.9426034692177813.60813783754365.589593747
2177643.77130494754535.983799841
#Sta/Elev= 30
       0 1121.67    15.6 1117.84    48.1 1114.83    64.5 1110.08   155.6 1090.08
   193.3 1083.17   209.3 1082.02   232.2 1082.19   243.3 1081.59     260 1082.28
   312.4 1082.55   319.7 1081.88   323.8 1080.68   332.5 1079.81   340.8 1080.56
  344.44 1081.84     348 1082.88   363.5 1084.56   384.7 1088.21   407.3 1087.22
   425.8 1096.15     430 1097.68   437.1 1098.92   449.8 1099.13     468 1104.58
   473.7 1106.92   499.5 1120.95   522.1  1134.7   544.8 1147.21   556.7 1150.85
#Mann= 5 ,-1,0
       0     .05       0   319.7    .045       0  344.44     .05       0
  346.12     .06       0  356.12      .1       0
Bank Sta=319.7,344.44
XS Rating Curve= 0 ,0
Exp/Cntr=0.3,0.1

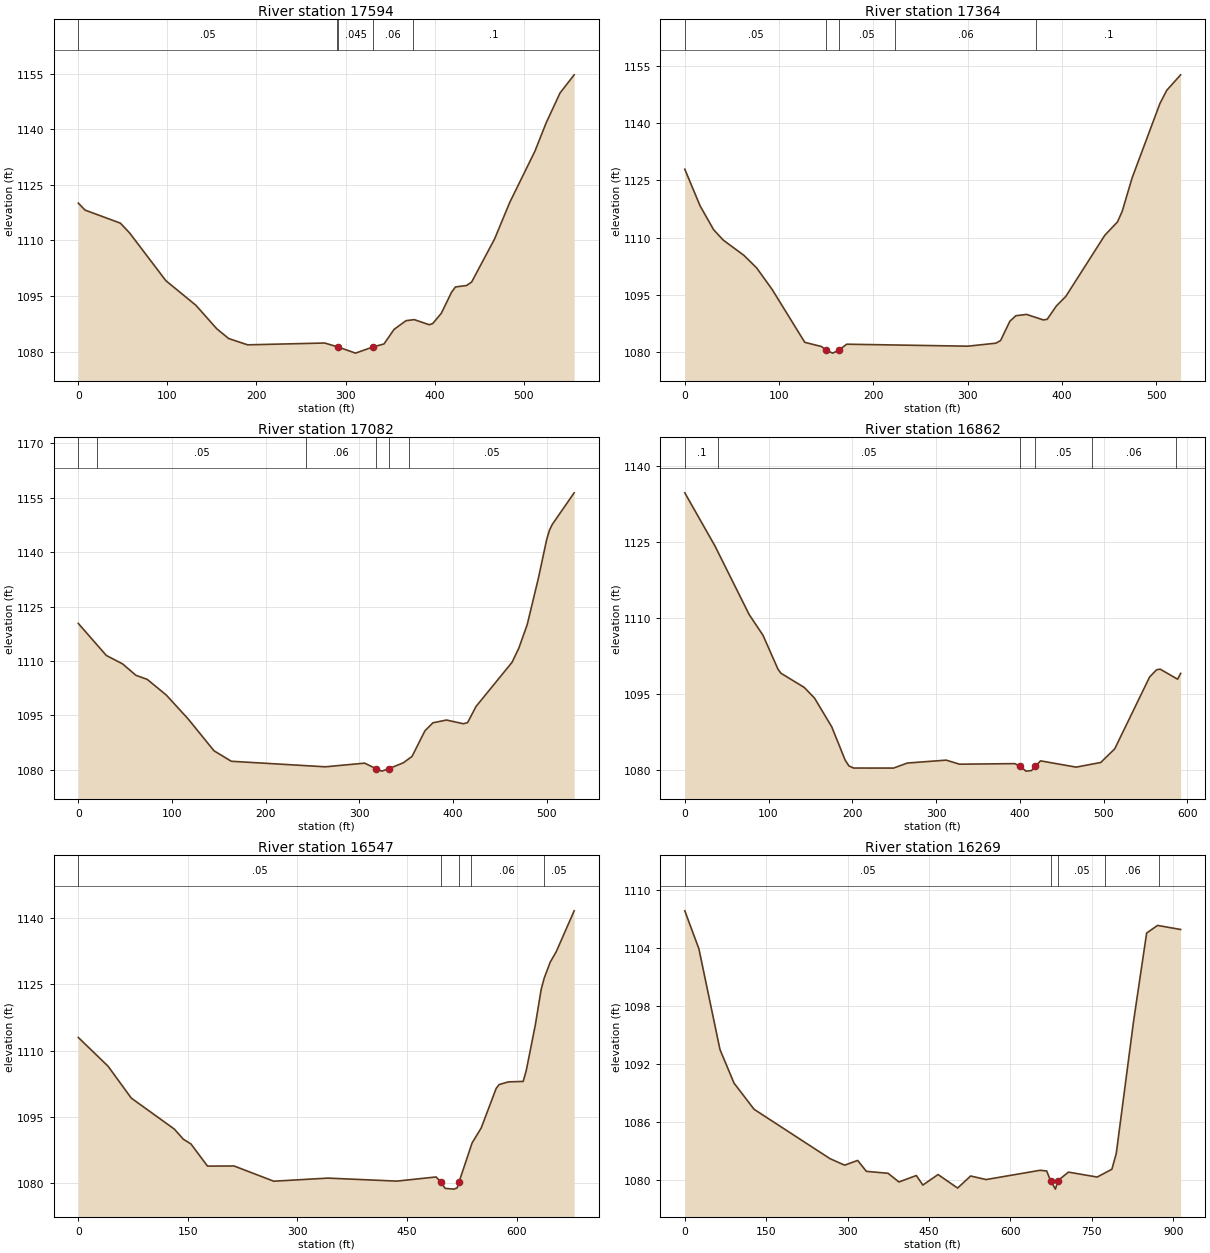
Type RM Length L Ch R = 1 ,17594   ,220.2,230.5,229.6
XS GIS Cut Line= 3
2177992.06622484754122.3698031292177772.73539121754350.016793407
2177602.89855832754520.410999501
#Sta/Elev= 30
       0 1120.07     7.6 1118.19    47.2 1114.67    57.5 1112.05    98.3 1099.13
     132 1092.49   155.5 1086.13   168.8 1083.51   190.1 1081.81   276.6  1082.3
   291.71081.224   311.2 1079.57  330.91 1081.24   343.2 1082.05   354.5 1085.98
   367.9 1088.33   377.1 1088.62     394 1087.24   397.9 1087.55   407.6 1090.35
   418.9 1095.95   423.4 1097.44   435.9 1097.83   441.6 1098.77   467.4 1110.42
   484.4 1120.28   512.6 1134.07   525.2 1141.71   540.8  1149.8   556.7 1154.72
#Mann= 5 ,-1,0
       0     .05       0     290     .06       0   291.7    .045       0
  330.91     .06       0  376.12      .1       0
Bank Sta=291.7,330.91
XS Rating Curve= 0 ,0
Exp/Cntr=0.3,0.1

Type RM Length L Ch R = 1 ,17364   ,281.9,282,280.1
XS GIS Cut Line= 4
2177812.48486208754014.7549191922177769.05146873754072.974148573
2177560.20153476754360.3738364722177501.23185828754438.732175684
#Sta/Elev= 30
       0 1127.92    16.2 1118.32    30.5 1112.09    40.7 1109.35    62.9  1105.3
    76.3 1102.02    92.7 1096.38   127.3 1082.53     145 1081.43  149.95 1080.48
   156.9  1079.7   163.31080.475   171.8 1082.04   300.3 1081.52     330 1082.31
     335    1083   344.8 1088.04   351.2 1089.51   362.6 1089.85   380.3 1088.41
   384.4 1088.56   394.3  1092.1   404.2 1094.57   445.6 1110.61     459  1114.1
     464 1116.86   474.5 1125.61     504 1145.12   511.3 1148.61     526 1152.66
#Mann= 5 ,-1,0
       0     .05       0  149.95    .045       0   163.3     .05       0
  222.64     .06       0  372.64      .1       0
Bank Sta=149.95,163.3
XS Rating Curve= 0 ,0
Exp/Cntr=0.3,0.1

Type RM Length L Ch R = 1 ,17082   ,216.6,220.3,221.6
XS GIS Cut Line= 4
2177636.96650414753888.8090287632177583.36784852753976.599930211
2177440.13006194754229.807372282 2177377.5791102754350.127350883
#Sta/Elev= 30
       0 1120.33    29.9 1111.51    47.3 1109.18    61.4 1106.05    73.6 1104.91
      94 1100.58   117.4 1093.97   144.9 1085.23   163.3 1082.35   263.7 1080.82
   305.7 1081.83   317.91080.305   324.1 1079.63   331.6 1080.31   347.1 1081.94
   356.3 1083.69   370.1 1090.75   378.6 1092.95   393.1 1093.71   411.1 1092.69
   415.6 1092.99   424.6 1097.44   463.1 1109.63   470.4 1113.57   479.3 1120.03
   491.2 1132.79   500.1  1143.5     503 1145.99     506 1147.61   529.4 1156.33
#Mann= 6 ,-1,0
       0      .1       0      20     .05       0  242.86     .06       0
   317.9    .045       0   331.6     .06       0  352.86     .05       0
Bank Sta=317.9,331.6
XS Rating Curve= 0 ,0
Exp/Cntr=0.3,0.1

Type RM Length L Ch R = 1 ,16862   ,313,314.5,304.7
XS GIS Cut Line= 4
2177438.53232983753662.1971807532177370.23536793753961.206491273
2177263.87872632 754080.520731082177227.86451114754200.566437881
#Sta/Elev= 30
       0 1134.66    35.9  1124.2    76.9  1110.6    93.3 1106.54   111.3 1099.81
   114.7 1099.04   142.6 1096.22   154.9 1094.11   175.4 1088.45   191.5 1081.84
   195.9 1080.73   201.5  1080.3   249.2 1080.29   265.7 1081.29     312 1081.86
     328 1081.06     394 1081.17  400.42 1080.64   407.3 1079.69   413.8  1079.8
   418.6 1080.64   424.6 1081.72   467.2 1080.48   496.5  1081.4   513.2 1084.08
   554.9 1098.29   563.2 1099.71   567.5 1099.83   588.3 1097.85   591.9    1099
#Mann= 6 ,-1,0
       0      .1       0      40     .05       0  400.42    .045       0
   418.6     .05       0  486.55     .06       0  586.55     .05       0
Bank Sta=400.42,418.6
XS Rating Curve= 0 ,0
Exp/Cntr(USF)=0,0
Exp/Cntr=0.3,0.1

Type RM Length L Ch R = 1 ,16547   ,276.2,278.4,278.2
XS GIS Cut Line= 3
2177318.87386073753613.2900757322177150.20202143753928.028250106
2177075.42996895754241.027539538
#Sta/Elev= 30
       0 1112.94    40.7 1106.46    72.5 1099.25   131.5 1092.24   143.7 1089.97
   154.2 1088.89   176.9 1083.88   213.2 1083.91   267.6 1080.47   341.7 1081.17
   436.1 1080.49   489.9 1081.43   496.4 1080.26   502.2 1078.85   514.5 1078.68
   518.7 1078.96  521.21 1080.27   539.2 1089.13   551.6 1092.49   572.1 1101.43
   576.2 1102.31   588.8 1102.91   609.1 1103.02   613.2  1105.4   625.6 1115.66
   633.8 1123.86   637.9 1126.36   646.1 1129.95   654.4 1132.34   678.9 1141.56
#Mann= 5 ,-1,0
       0     .05       0   496.4    .045       0  521.21     .05       0
  537.09     .06       0  637.09     .05       0
Bank Sta=496.4,521.21
XS Rating Curve= 0 ,0
Exp/Cntr=0.3,0.1

Type RM Length L Ch R = 1 ,16269   ,511.5,517.6,506.7
XS GIS Cut Line= 4
2176986.31835917753237.0882826832176933.07718004753368.923583392
2176920.40070882753791.0500750852176903.92129623 754139.65303369
#Sta/Elev= 30
       0 1107.85      26 1103.92    64.8  1093.5    90.7 1090.02   127.7 1087.31
   267.6  1082.2   294.5 1081.53   318.5 1082.02   334.5 1080.89   374.5 1080.69
   394.5 1079.79   426.6 1080.46   438.6 1079.47   466.6 1080.56   502.6 1079.16
   526.6 1080.41   555.1 1080.04   654.7    1081   666.7 1080.93   673.8 1079.93
   682.8 1079.05  687.51 1079.93   706.8 1080.81   759.8  1080.3   786.9 1081.11
   794.9 1082.73   826.9 1096.46   850.9 1105.55     871 1106.34   913.5 1105.92
#Mann= 5 ,-1,0
       0     .05       0   673.8    .045       0  687.51     .05       0
   774.5     .06       0   874.5     .05       0
Bank Sta=673.8,687.51
XS Rating Curve= 0 ,0
Exp/Cntr(USF)=0,0
Exp/Cntr=0.3,0.1

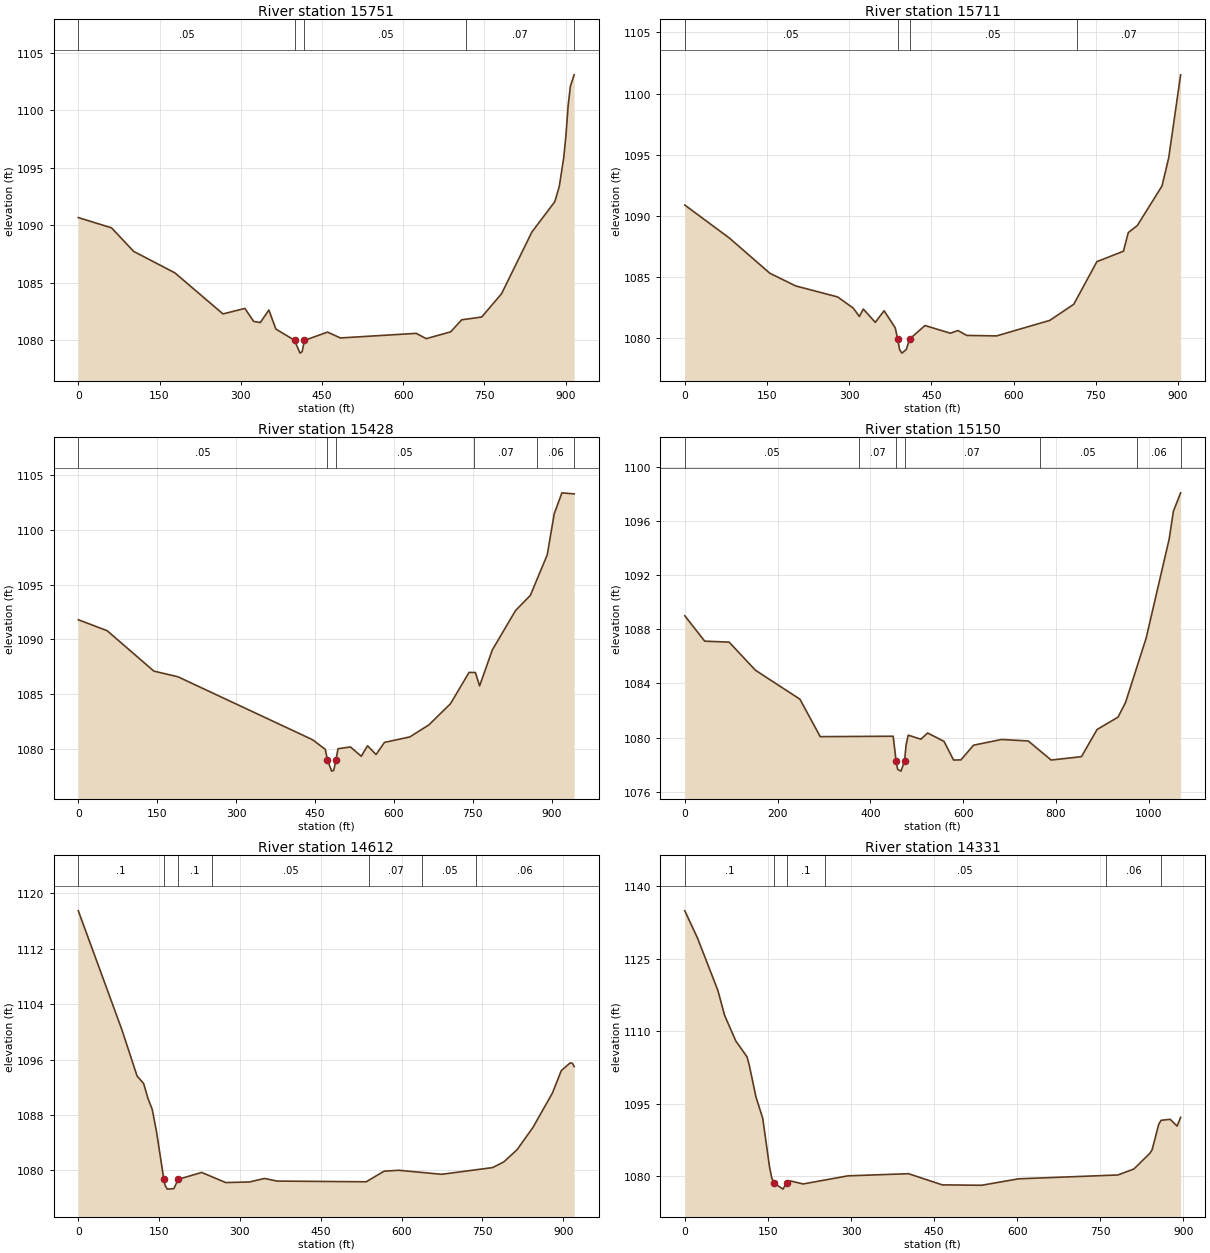
Type RM Length L Ch R = 1 ,15751   ,39.8,39.9,40.3
XS GIS Cut Line= 6
2176886.73511879753220.4881704212176841.47880631753547.289382862
2176861.21750627753596.5358611752176853.07099867  753650.8459118
2176809.71609145753686.4664429882176719.33120913754095.995143417
#Sta/Elev= 30
       0 1090.65    61.3 1089.76   102.2 1087.71   178.4 1085.84   267.2 1082.27
   307.6 1082.75   323.8 1081.62   336.1 1081.52   351.9 1082.61   364.9 1080.95
  399.29 1079.98   409.4 1078.86   413.4 1078.99   417.6 1079.97   460.3 1080.69
     484 1080.18   624.1 1080.58   642.5 1080.12   687.6 1080.71   708.1 1081.76
     745    1082   781.7 1084.03   837.6 1089.39   880.1 1092.04   888.3 1093.37
   896.5 1095.86   900.6 1097.81   904.7 1100.42   908.8 1102.08   915.7 1103.07
#Mann= 5 ,-1,0
       0     .05       0  399.29    .045       0   417.6     .05       0
  716.36     .07       0  915.75     .05       0
Bank Sta=399.29,417.6
XS Rating Curve= 0 ,0
Exp/Cntr=0.3,0.1

Type RM Length L Ch R = 1 ,15711   ,281.1,283.7,278.1
XS GIS Cut Line= 6
  2176840.231493753224.4895373762176799.04843432753540.428739692
2176818.78713428753559.8046901622176814.71388048753641.269766099
2176771.35897325753676.8902972872176680.97409094754086.418997716
#Sta/Elev= 30
       0 1090.87    81.4 1088.17   155.2 1085.29   202.4 1084.25     279 1083.35
   307.6 1082.43   318.6 1081.75   325.8 1082.36   347.7 1081.27   363.8 1082.22
   384.1 1080.82  388.59 1079.89   392.1 1079.04   396.2 1078.75   404.3 1079.05
   410.41079.901   438.4 1081.01   484.7 1080.38   498.6  1080.6   514.6  1080.2
   569.1 1080.16   666.2 1081.43     710 1082.75   752.2 1086.24   800.6 1087.09
   809.5 1088.62   825.9 1089.19     871 1092.43   883.3 1094.75     905 1101.53
#Mann= 4 ,-1,0
       0     .05       0  388.59    .045       0   410.4     .05       0
  715.63     .07       0
Bank Sta=388.59,410.4
XS Rating Curve= 0 ,0
Exp/Cntr=0.3,0.1

Type RM Length L Ch R = 1 ,15428   ,260.5,277.1,287.2
XS GIS Cut Line= 3
2176609.60531722753159.064792424 2176578.0543643753369.610787243
2176505.64636068754096.074000034
#Sta/Elev= 30
       0 1091.78    54.7 1090.78   143.7 1087.08   189.5 1086.56   445.6  1080.8
   469.7 1079.92   473.8 1078.97   473.8 1078.95   481.8 1077.93   485.8    1078
   489.8 1078.92   493.9 1079.98   517.6 1080.14   538.1 1079.29   550.1 1080.25
   566.2 1079.45   582.3 1080.56   630.5 1081.06   666.7 1082.16   707.7 1084.09
   743.1 1086.96   755.2 1086.95   763.2 1085.73   787.3 1089.01   831.5 1092.62
   859.7 1094.01   891.8 1097.72   905.1 1101.47   919.7 1103.39     943 1103.29
#Mann= 6 ,-1,0
       0     .05       0   473.8    .045       0   489.8     .05       0
   752.9     .07       0   872.9     .06       0   942.9     .05       0
Bank Sta=473.8,489.8
XS Rating Curve= 0 ,0
Exp/Cntr=0.3,0.1

Type RM Length L Ch R = 1 ,15150   ,547.1,538.6,515.7
XS GIS Cut Line= 6
2176512.33586264753142.5857948552176503.20880336753208.756974634
 2176491.1661557753286.4637432252176454.15085973 753462.03286965
 2176119.7455489753642.6725845632176033.54554459753996.346131657
#Sta/Elev= 30
       0 1089.01      43 1087.13    95.6 1087.06   152.3 1084.98   248.2 1082.84
     292 1080.07   449.3  1080.1   455.6 1078.26   458.9 1077.65   466.1 1077.52
   473.81078.273   477.1 1079.45   481.7 1080.18     509 1079.88   523.5 1080.34
   558.9 1079.72   579.5 1078.34   595.3 1078.35   622.6 1079.44   682.9 1079.86
   740.5 1079.75   789.9 1078.34   855.2 1078.59   888.9  1080.6     934 1081.51
   950.4 1082.61   994.7 1087.36  1044.3 1094.68  1053.4 1096.73    1069  1098.1
#Mann= 7 ,-1,0
       0     .05       0  374.86     .07       0   455.6    .045       0
   473.8     .07       0  764.94     .05       0  974.94     .06       0
 1068.96     .05       0
Bank Sta=455.6,473.8
XS Rating Curve= 0 ,0
Exp/Cntr=0.3,0.1

Type RM Length L Ch R = 1 ,14612   ,285.1,281.3,278.4
XS GIS Cut Line= 4
2176076.91263656753068.1243624672176079.89639214753156.410104027
2176055.93786153 753565.986889212175959.49738991753976.360431473
#Sta/Elev= 30
       0 1117.46    80.6 1100.36   109.1 1093.62   121.2 1092.55   129.2 1090.41
   137.2  1088.8   145.2 1085.56  158.65 1078.73   161.2 1077.82   165.2 1077.31
   177.3 1077.38   185.3 1078.72   228.9 1079.72   273.4 1078.26   317.5 1078.34
   345.5 1078.85   368.9 1078.47   534.3 1078.37   567.5  1079.9   594.5 1080.03
   674.5 1079.45     769 1080.42   789.5 1081.23   814.2 1082.99   843.8 1086.22
   879.9 1091.18   896.4 1094.42   912.8 1095.52     917 1095.47   920.2 1094.99
#Mann= 7 ,-1,0
       0      .1       0  158.65    .045       0   185.3      .1       0
  248.34     .05       0  538.61     .07       0  638.61     .05       0
  738.61     .06       0
Bank Sta=158.65,185.3
XS Rating Curve= 0 ,0
Exp/Cntr=0.3,0.1

Type RM Length L Ch R = 1 ,14331   ,265.6,268.6,267.1
XS GIS Cut Line= 4
2175766.50481717753058.8674037912175777.95936704753110.011611028
2175879.48451211753749.3684778992175835.06208796753939.344961616
#Sta/Elev= 30
       0 1134.88    22.9 1129.27    59.7 1118.42    71.8 1113.28      92 1107.97
   112.3 1104.67   116.4 1102.95   128.5 1096.36   140.7 1091.94   152.8 1082.01
   156.9 1079.64   160.9 1078.62   177.1 1077.31  183.94 1078.61   189.3 1079.04
   213.6 1078.38   294.6 1080.06   403.9  1080.5   464.7 1078.19   535.9 1078.11
   602.2 1079.44   781.7 1080.24   810.5 1081.47   839.3 1084.71   843.4 1085.43
   855.5 1090.77   859.8 1091.55   876.2 1091.75   888.5 1090.35   894.9 1092.16
#Mann= 6 ,-1,0
       0      .1       0   160.9    .045       0  183.94      .1       0
  252.41     .05       0  759.78     .06       0  859.78     .05       0
Bank Sta=160.9,183.94
XS Rating Curve= 0 ,0
Exp/Cntr=0.3,0.1