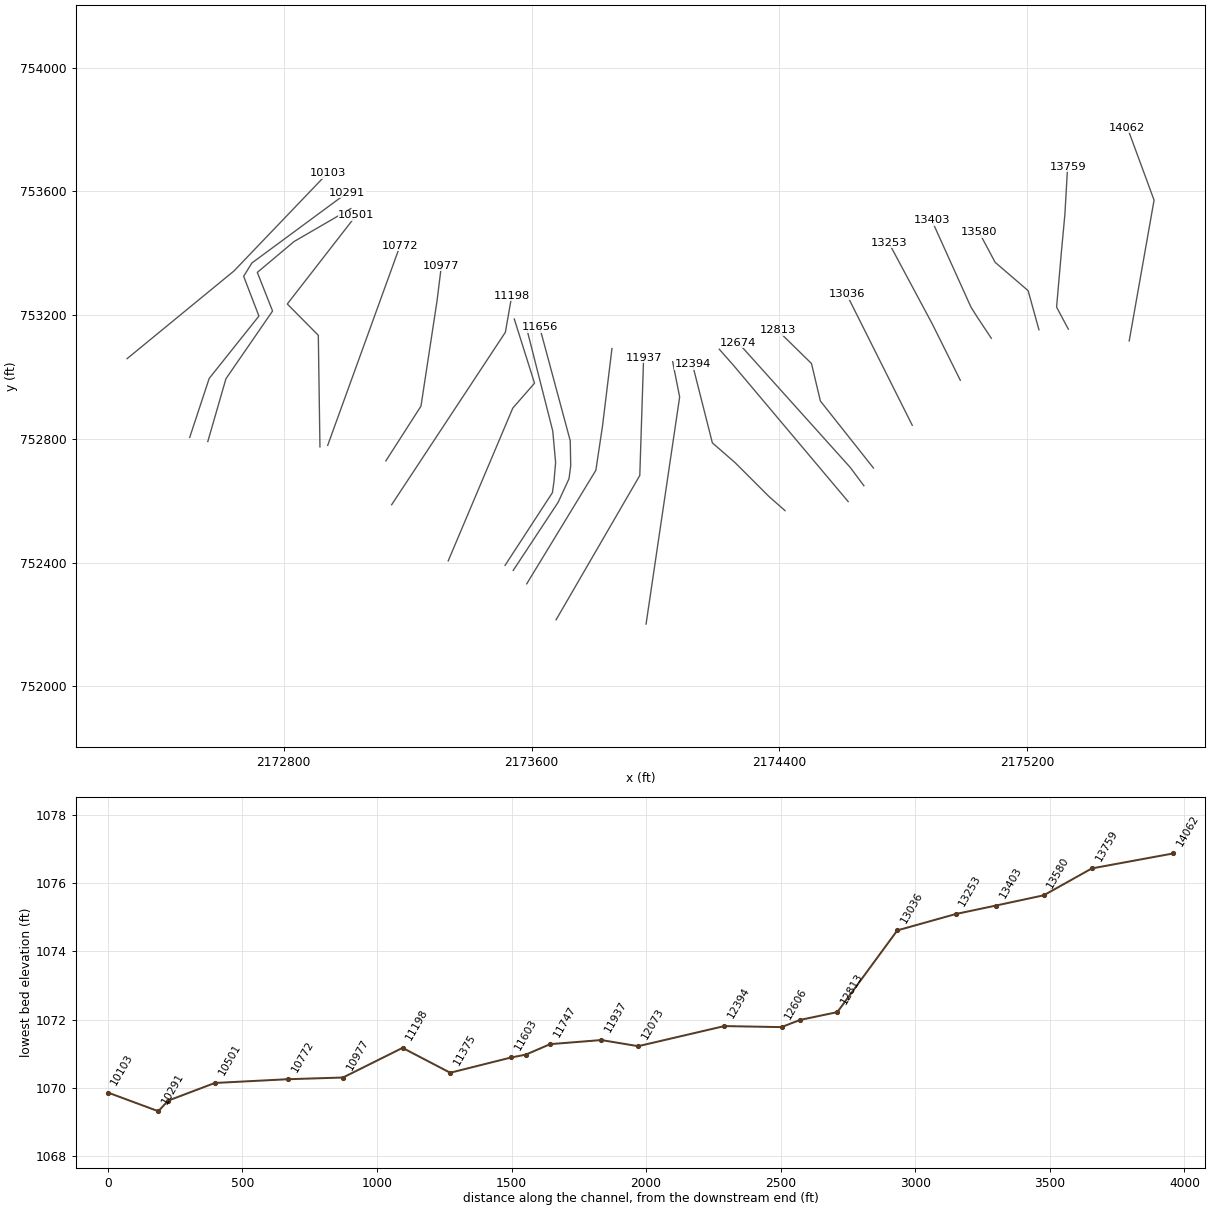
HEC-RAS study HACKERSCK.prj: HACKERSCK

--- HACKERSCK.g01 (geometry) --- (continued)

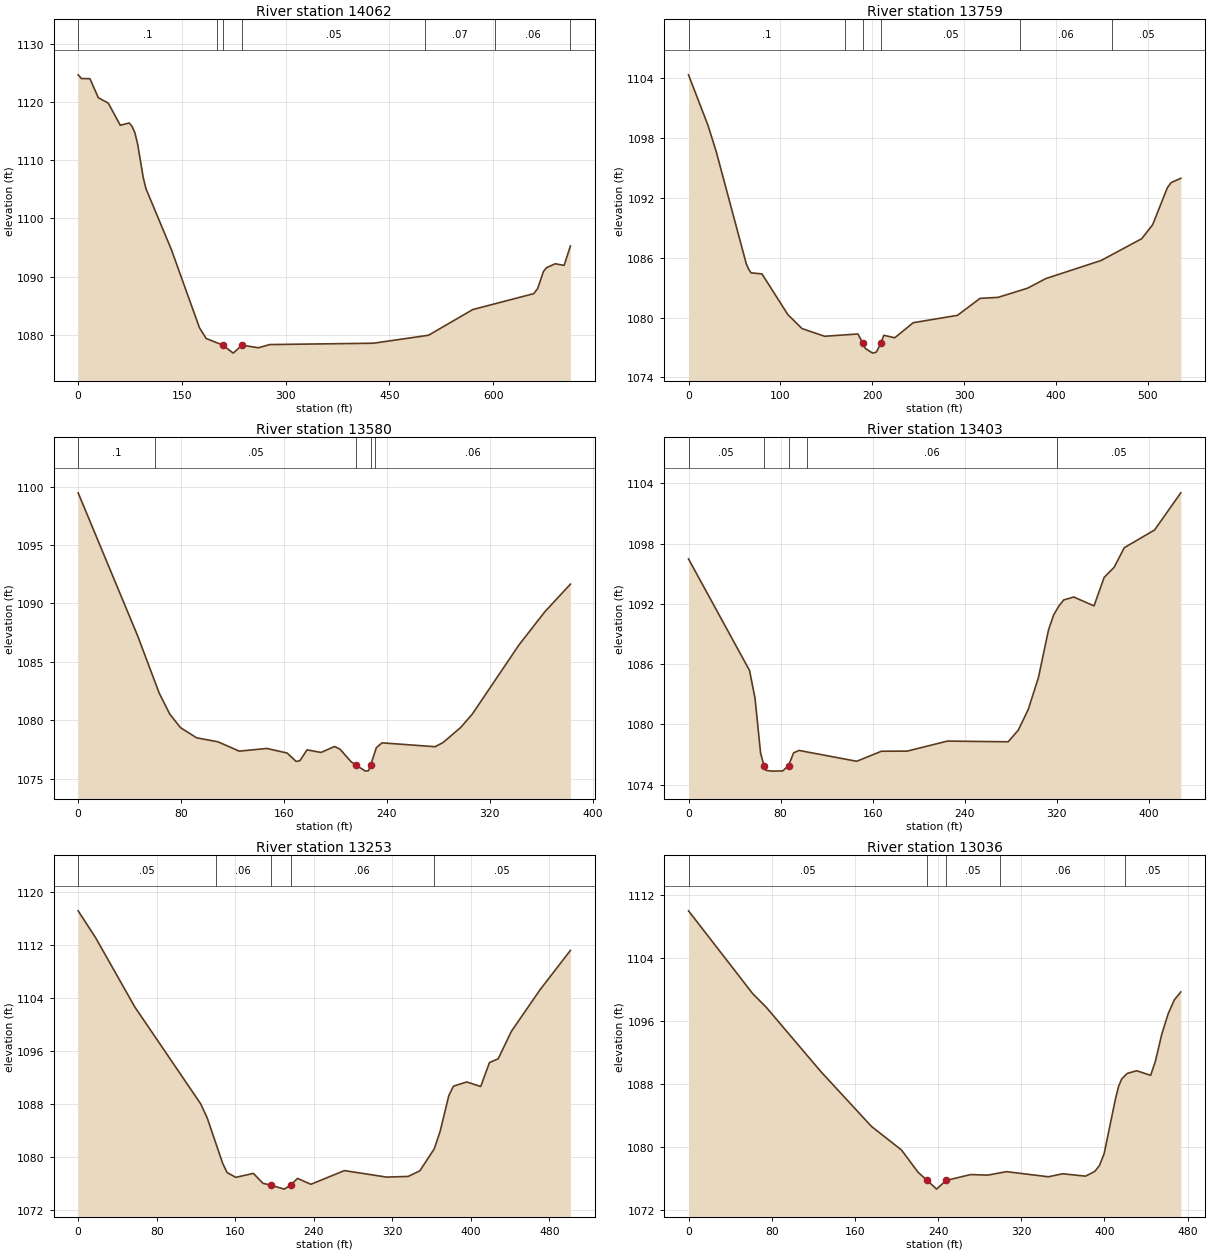
Type RM Length L Ch R = 1 ,14062   ,287.1,302.9,297.4
XS GIS Cut Line= 3
2175530.38957356753116.456874357 2175610.6738913753571.401341546
2175524.48446045753805.669808147
#Sta/Elev= 30
       0 1124.66     4.8 1124.02      17    1124    29.2 1120.73    43.6 1119.79
    60.9    1116    73.8 1116.39    77.9 1115.81      82 1114.73      86 1112.76
    94.2 1106.96    98.2 1105.06   134.8 1094.65   175.4 1081.23   185.1 1079.39
   209.3 1078.25   224.1 1076.88   236.9 1078.24   260.7  1077.8   276.9 1078.35
   426.8 1078.58   506.5 1079.95   570.4 1084.36   658.5 1087.09   664.2 1087.96
   672.7 1090.92     677 1091.55   689.6 1092.22   702.5 1091.95   711.6 1095.28
#Mann= 7 ,-1,0
       0      .1       0     200     .05       0   209.3    .045       0
   236.9     .05       0  501.97     .07       0  601.97     .06       0
  711.59     .05       0
Bank Sta=209.3,236.9
XS Rating Curve= 0 ,0
Exp/Cntr=0.3,0.1

Type RM Length L Ch R = 1 ,13759   ,168.5,179,189.4
XS GIS Cut Line= 5
2175333.70848856753154.5600932562175295.81978373753225.716929166
2175311.52973451753405.9193058222175322.61911154753525.130108841
2175331.46052767 753679.77812801
#Sta/Elev= 30
       0 1104.34    21.1  1099.3    30.2 1096.63    62.8 1085.43    65.2  1084.9
    68.1 1084.49      80 1084.38   108.2  1080.3   123.6  1078.9   148.3 1078.13
   184.5 1078.36   189.6 1077.47   192.5 1076.91   200.5 1076.44   204.5 1076.54
   209.7 1077.46   212.6 1078.23   224.6 1077.98   244.7 1079.49   292.9 1080.23
   317.5 1081.93   337.1 1082.03   369.2 1082.95   389.3 1083.92   449.4 1085.73
   493.5 1087.91   505.5 1089.32   521.5 1093.03   525.5 1093.53   536.1 1093.97
#Mann= 6 ,-1,0
       0      .1       0  170.62     .05       0   189.6    .045       0
   209.7     .05       0   361.5     .06       0  461.23     .05       0
Bank Sta=189.6,209.7
XS Rating Curve= 0 ,0
Exp/Cntr=0.3,0.1

Type RM Length L Ch R = 1 ,13580   ,184.2,176.9,174.4
XS GIS Cut Line= 4
2175238.87126417753152.4158462392175203.93972654753278.834744324
 2175097.4817071 753370.322104782175045.08440065753468.463091451
#Sta/Elev= 30
       0 1099.46    46.4 1087.19      63 1082.33    71.3 1080.52    79.6 1079.37
    92.1  1078.5   108.7 1078.16   125.3 1077.36   146.7 1077.59   162.5  1077.2
   169.5 1076.48   172.4 1076.54     178 1077.47   188.9 1077.25   199.4 1077.76
   203.6 1077.53   212.1 1076.47   216.11076.159   223.4 1075.65   225.8 1075.69
   227.51076.186   231.9 1077.66   236.3 1078.07   277.6 1077.74   283.8  1078.1
   297.4 1079.38   306.5 1080.53   342.8 1086.45   362.8 1089.27   382.8 1091.65
#Mann= 5 ,-1,0
       0      .1       0      60     .05       0   216.1    .045       0
   227.5     .05       0  231.16     .06       0
Bank Sta=216.1,227.5
XS Rating Curve= 0 ,0
Exp/Cntr=0.3,0.1

Type RM Length L Ch R = 1 ,13403   ,156.7,150,153.4
XS GIS Cut Line= 4
2175085.00615794753124.969638102     2175039.174      753194.116
2175019.30159907753225.6057346042174892.88270099 753505.88973891
#Sta/Elev= 30
       0 1096.47      53 1085.37    57.8  1082.6    62.6 1077.15    65.61075.896
    67.4 1075.42    72.9 1075.35    81.8 1075.37   86.86 1075.89    91.3 1077.17
      96 1077.41   146.1 1076.33   167.6 1077.33   189.9 1077.34     225 1078.34
   277.7 1078.27   286.5 1079.43   295.2  1081.5     304 1084.66   312.8 1089.42
   317.2 1090.89   321.8 1091.79     326 1092.39   334.7 1092.68   352.3  1091.8
   361.1 1094.63   369.8 1095.64   378.6 1097.59   404.9 1099.35   427.7 1103.05
#Mann= 5 ,-1,0
       0     .05       0    65.6    .045       0   86.86     .05       0
  102.96     .06       0  320.19     .05       0
Bank Sta=65.6,86.86
XS Rating Curve= 0 ,0
Exp/Cntr=0.3,0.1

Type RM Length L Ch R = 1 ,13253   ,216.1,217,213.7
XS GIS Cut Line= 3
2174984.82299176752989.328987497     2174894.837      753170.338
2174753.60948079753434.290240625
#Sta/Elev= 30
       0 1117.17    17.7 1113.13    57.9  1102.6   124.9 1087.98   131.5 1085.86
   147.2 1079.02   151.7 1077.61   160.6 1076.88   178.5 1077.48   188.3 1075.98
   196.4  1075.7   209.9  1075.1  216.52 1075.71   223.5 1076.72   237.1 1075.83
   271.2  1077.9   314.2 1076.92   336.2 1077.02   348.1 1077.87   362.8  1081.2
   368.8 1083.86   377.6 1089.23   382.3 1090.66   395.9  1091.3   410.1 1090.62
     419 1094.23   427.9  1094.8   441.3 1098.94   470.6 1105.25   501.5 1111.19
#Mann= 5 ,-1,0
       0     .05       0     140     .06       0   196.4    .045       0
  216.52     .06       0  362.14     .05       0
Bank Sta=196.4,216.52
XS Rating Curve= 0 ,0
Exp/Cntr=0.3,0.1

Type RM Length L Ch R = 1 ,13036   ,223.8,222.9,214.5
XS GIS Cut Line= 2
2174829.65654757752843.8189984332174617.67683089 753267.15026195
#Sta/Elev= 30
       0 1109.98    61.7 1099.46    74.8 1097.72   127.3 1089.55     176 1082.58
   204.8 1079.59   220.7 1076.77  229.56 1075.72   238.6 1074.62   247.6 1075.72
   271.3 1076.47   287.8  1076.4   305.7 1076.84     346 1076.19   359.8 1076.57
   381.8 1076.27   390.7 1076.87   395.2 1077.63   399.7 1079.14   410.5 1086.04
   413.5 1087.65   416.5 1088.61     422 1089.33     431 1089.66   444.4 1089.08
   448.9 1090.84   455.2 1094.35   461.2 1096.88   467.1 1098.65   473.4 1099.67
#Mann= 5 ,-1,0
       0     .05       0  229.56    .045       0   247.6     .05       0
     300     .06       0     420     .05       0
Bank Sta=229.56,247.6
XS Rating Curve= 0 ,0
Exp/Cntr=0.3,0.1

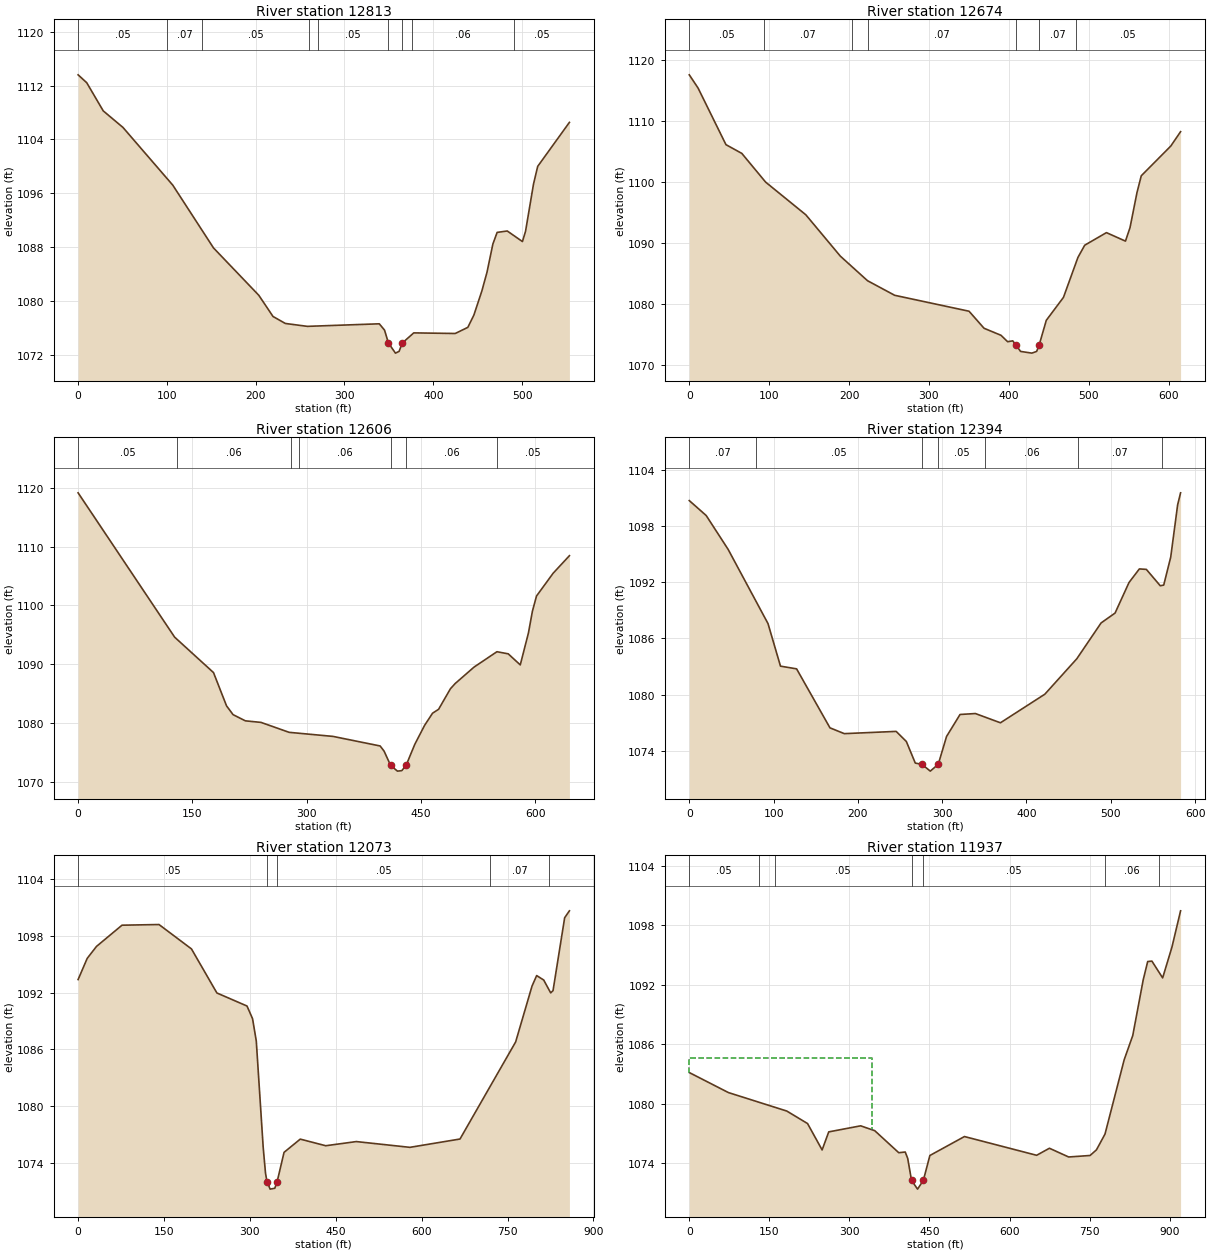
Type RM Length L Ch R = 1 ,12813   ,134.9,138.9,142.6
XS GIS Cut Line= 4
2174704.41953706752705.6030550482174532.94491084752922.256624703
2174504.19467411753043.418336643 2174395.3544922753150.204930216
#Sta/Elev= 30
       0  1113.6     9.7 1112.43    28.3 1108.24    50.5 1105.78   106.6  1097.2
   152.5 1087.86   203.5 1080.82   219.5 1077.67   233.4 1076.63   258.2  1076.2
   339.2 1076.58   345.1 1075.64  349.49 1073.72   357.4 1072.22   361.5 1072.48
   365.11073.725     378 1075.23   424.7 1075.14   438.9 1076.05   445.7 1077.87
   454.7 1081.46   460.5 1084.25   467.1 1088.44   471.9 1090.17   483.3 1090.38
   500.4 1088.81   503.9 1090.33   512.9 1097.38   517.6 1099.99   553.3 1106.53
#Mann= 9 ,-1,0
       0     .05       0     100     .07       0     140     .05       0
     260     .07       0     270     .05       0  349.49    .045       0
   365.1     .05       0   376.3     .06       0  490.83     .05       0
Bank Sta=349.49,365.1
XS Rating Curve= 0 ,0
Exp/Cntr=0.3,0.1

Type RM Length L Ch R = 1 ,12674   ,66.9,68.4,69.8
XS GIS Cut Line= 3
2174673.50058989752648.3937667592174629.46311212752707.481098658
2174267.80338816 753110.21258938
#Sta/Elev= 30
       0 1117.56      11  1115.4    45.9 1106.13    65.8 1104.69    95.6 1099.99
   145.9 1094.64   189.1 1087.87   223.1 1083.85   257.1 1081.46   350.2 1078.85
     369 1076.06   390.2 1074.91   398.5 1073.86   404.9    1074   409.3 1073.24
   414.7 1072.27   428.8 1071.99   434.8 1072.27   437.9 1073.28   446.9 1077.36
   468.4 1081.12   486.5 1087.66     495 1089.66   522.2 1091.72     546 1090.33
   551.7 1092.54   560.5 1098.32   565.8 1101.03   602.7 1105.89     615 1108.25
#Mann= 7 ,-1,0
       0     .05       0   93.69     .07       0  203.69     .06       0
  223.69     .07       0   409.3    .045       0   437.9     .07       0
  483.69     .05       0
Bank Sta=409.3,437.9
XS Rating Curve= 0 ,0
Exp/Cntr=0.3,0.1

Type RM Length L Ch R = 1 ,12606   ,210,212.5,214.6
XS GIS Cut Line= 3
2174622.71250087752597.1821766762174252.65923054753037.129915792
2174206.42109751 753089.53585632
#Sta/Elev= 30
       0 1119.14   126.7 1094.58   177.7 1088.55   194.8 1082.89   203.4 1081.39
   219.5 1080.34   240.1 1080.07     277 1078.38   334.5 1077.69   396.4 1076.06
   401.6 1075.18  410.08 1072.77   419.1 1071.78   424.8 1071.86   430.5 1072.77
   441.8 1076.32   454.7 1079.56   465.2 1081.64   473.1  1082.3   488.6 1085.79
   494.9 1086.69   519.7 1089.49   549.7  1092.1   564.5 1091.74   580.3 1089.86
     591 1095.28   596.3 1099.02   601.6 1101.57   623.4 1105.45   644.8 1108.44
#Mann= 7 ,-1,0
       0     .05       0     130     .06       0     280     .05       0
     290     .06       0  410.08    .045       0   430.5     .06       0
     550     .05       0
Bank Sta=410.08,430.5
XS Rating Curve= 0 ,0
Exp/Cntr=0.3,0.1

Type RM Length L Ch R = 1 ,12394   ,332.2,320.1,304.2
XS GIS Cut Line= 5
2174418.82100682752567.9345909552174367.17612406752613.319487923
2174257.62637276752722.8692392242174184.07153975752787.034093557
2174119.90668541753040.563517997
#Sta/Elev= 30
       0 1100.75    20.1 1099.15    46.1 1095.53    93.4 1087.59   108.2 1083.04
   127.3 1082.75   166.9 1076.44   183.9 1075.82   245.4 1076.06   257.5 1074.98
   268.1 1072.67   275.9 1072.54   285.9 1071.81  295.36 1072.54   305.2 1075.52
   321.2 1077.87   339.4 1077.97   369.1 1076.98   421.8 1080.04   459.7 1083.83
   488.5 1087.66   505.1 1088.72   521.6 1091.98   533.9 1093.44   542.2 1093.39
   558.7 1091.64   562.8 1091.71   571.1  1094.7   579.3 1100.29   582.8 1101.58
#Mann= 7 ,-1,0
       0     .07       0   78.75     .05       0   275.9    .045       0
  295.36     .05       0  351.29     .06       0  461.29     .07       0
  561.29     .05       0
Bank Sta=275.9,295.36
XS Rating Curve= 0 ,0
Exp/Cntr=0.3,0.1

Type RM Length L Ch R = 1 ,12073   ,142.2,136.8,131.2
XS GIS Cut Line= 3
2173969.98496335752201.3508106882174078.43921714 752935.17764476
 2174055.9032683753049.265885758
#Sta/Elev= 30
       0 1093.39    15.9 1095.63    32.2  1096.9    76.7 1099.14   141.3 1099.21
     198 1096.63   242.4 1091.97     295 1090.59   304.7 1089.25   311.2 1086.89
   323.3 1075.61   327.3 1072.92   329.81072.024   335.4 1071.22   343.5 1071.31
   347.6    1072   359.7 1075.11     388 1076.51   432.5 1075.81   485.9 1076.25
   579.5 1075.64     667 1076.52   764.2 1086.79   792.8  1092.7   800.9 1093.81
   813.2 1093.34   825.4 1091.98   829.5 1092.22   849.8 1099.93   858.1 1100.66
#Mann= 5 ,-1,0
       0     .05       0   329.8    .045       0   347.6     .05       0
     720     .07       0   821.8     .05       0
Bank Sta=329.8,347.6
XS Rating Curve= 0 ,0
Exp/Cntr=0.3,0.1

Type RM Length L Ch R = 1 ,11937   ,187.1,190,197.3
XS GIS Cut Line= 3
2173679.37223992752215.1169338252173949.71523884752681.579650354
2173962.06086467753062.754416247
#Sta/Elev= 30
       0 1083.15    73.4 1081.13   182.7 1079.27   221.6 1078.01   248.9 1075.35
   261.3 1077.17   321.1 1077.78   347.5 1077.29   392.5 1075.07   404.6 1075.14
   409.2 1074.51   416.4 1072.28   427.7  1071.4  438.54 1072.28   450.8 1074.79
   515.6  1076.7   650.8 1074.81   674.8 1075.52   710.8 1074.64   750.9 1074.79
   762.9 1075.36   778.9 1076.95   814.9 1084.45   830.9 1086.88   850.5  1092.5
   858.9 1094.34   866.8 1094.38   886.9 1092.69   904.3 1095.79   920.5 1099.45
#Mann= 7 ,-1,0
       0     .05       0     130     .06       0     160     .05       0
   416.4    .045       0  438.54     .05       0  779.14     .06       0
  879.14     .05       0
#XS Ineff= 2 , 0
          342.54 1084.66
Permanent Ineff=
       T       F
Bank Sta=416.4,438.54
XS Rating Curve= 0 ,0
Exp/Cntr=0.3,0.1

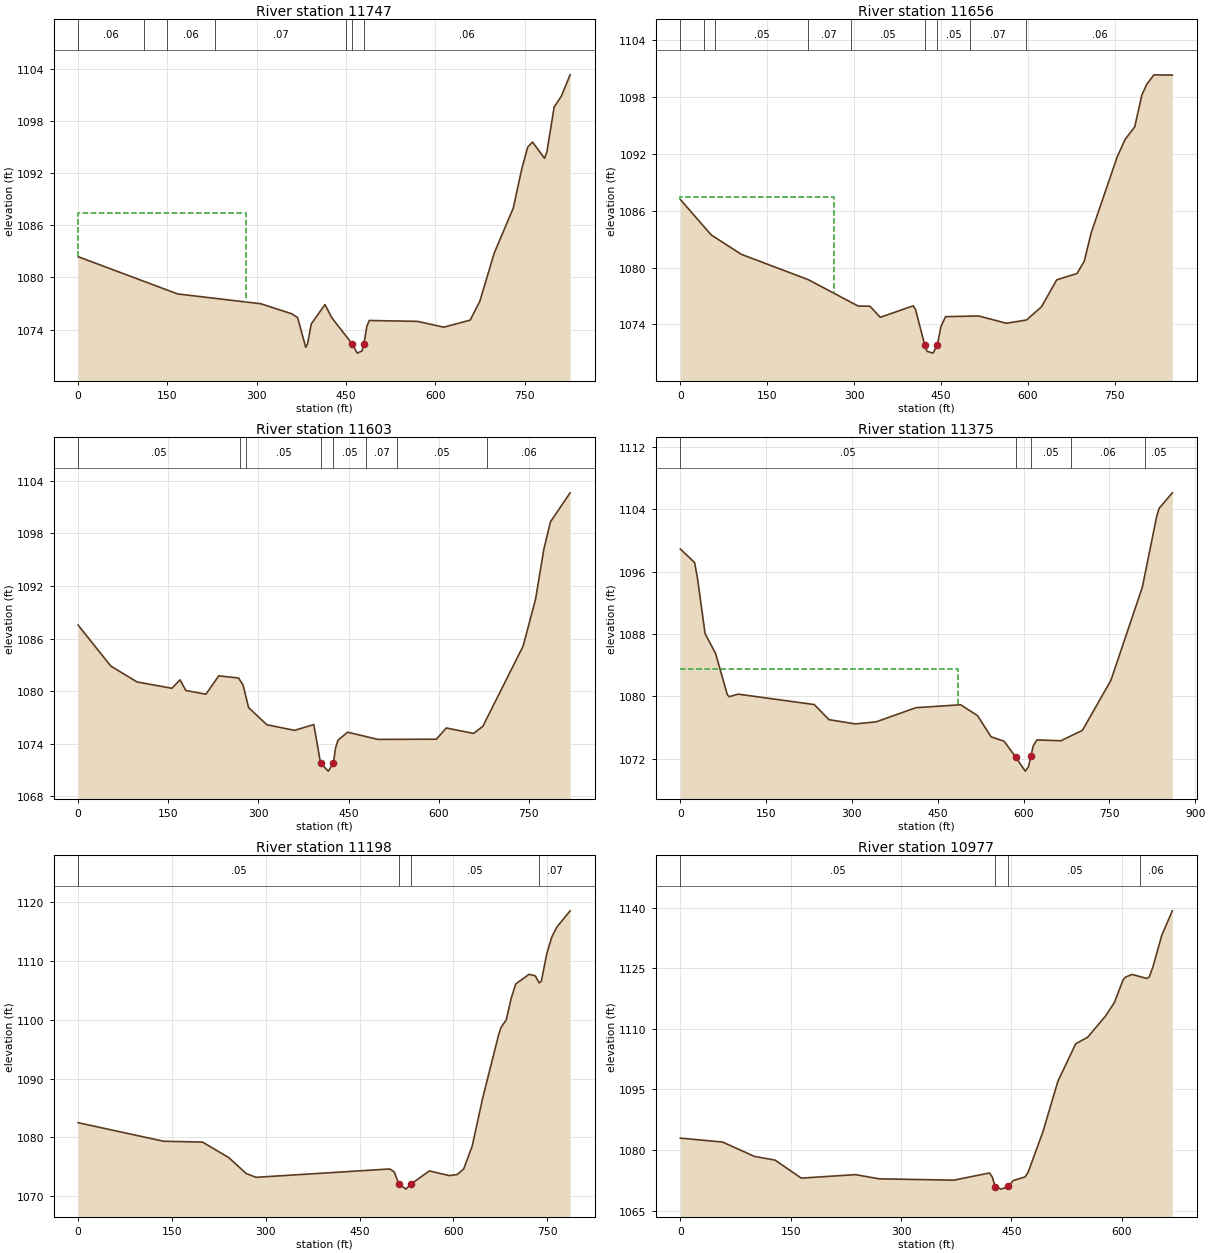
Type RM Length L Ch R = 1 ,11747   ,88.6,91.1,93.3
XS GIS Cut Line= 4
2173584.57620758752331.3534973822173807.83521196752698.248763634
2173829.39788951752841.9999472912173859.82142044753091.815165663
#Sta/Elev= 30
       0 1082.39     167  1078.1   306.7 1076.97   359.1 1075.81   368.6 1075.38
   382.4 1071.95   385.3 1072.32   391.7 1074.65   414.7 1076.88     426 1075.37
   460.5 1072.33   468.9 1071.28   476.9 1071.53   480.2 1072.36     485 1074.37
   489.1 1075.04     570 1074.94   614.3 1074.27   658.6 1075.08   674.8 1077.25
   698.9 1082.78   731.1 1088.01   745.4 1092.54   755.3 1095.02   763.4 1095.59
   783.6 1093.72   787.6 1094.51   799.7 1099.63   811.8 1100.88   826.5 1103.34
#Mann= 7 ,-1,0
       0     .06       0     110     .05       0     150     .06       0
     230     .07       0  449.48     .06       0   460.5    .045       0
   480.2     .06       0
#XS Ineff= 2 , 0
        282.2155  1087.4
Permanent Ineff=
       T       F
Bank Sta=460.5,480.2
XS Rating Curve= 0 ,0
Exp/Cntr=0.3,0.1

Type RM Length L Ch R = 1 ,11656   ,50.7,52.9,53.2
XS GIS Cut Line= 6
2173540.91167207752374.697557437 2173686.1313982752595.084165958
2173721.09521857752670.9960870732173726.63990708752712.581250917
2173725.14957662752793.460799405 2173626.5773364753159.820958896
#Sta/Elev= 30
       0 1087.18    53.2 1083.45   105.2  1081.4   220.7 1078.73   307.1 1075.94
   327.4 1075.92   345.3 1074.75   402.1 1075.96   406.1 1075.59   422.1 1071.83
   426.1 1071.16   436.5 1070.97   443.9 1071.84   450.1 1073.78   458.1 1074.82
   515.4 1074.89   563.3 1074.12   597.9 1074.47   623.8 1075.86   650.1 1078.71
   685.1 1079.37   697.6 1080.66   709.7 1083.68   754.4 1091.66   768.4 1093.54
   784.8 1094.84   797.2 1098.22   805.5 1099.33     818 1100.34   849.8 1100.31
#Mann= 9 ,-1,0
       0     .05       0      40     .06       0      60     .05       0
     220     .07       0  293.93     .05       0   422.1    .045       0
   443.9     .05       0  500.37     .07       0  597.52     .06       0
#XS Ineff= 2 , 0
        264.5811  1087.4
Permanent Ineff=
       T       F
Bank Sta=422.1,443.9
XS Rating Curve= 0 ,0
Exp/Cntr=0.3,0.1

Type RM Length L Ch R = 1 ,11603   ,238.6,227.5,217.5
XS GIS Cut Line= 6
2173514.57268472752391.010867194 2173667.5650159 752626.14673189
2173672.69898674752663.1113219742173677.83295759752723.692177943
2173668.59181006752825.3448006722173585.42148238753152.892140576
#Sta/Elev= 30
       0 1087.54    54.3 1082.88      98 1081.06     156 1080.34   169.6  1081.3
   179.2 1080.09   212.6 1079.66     234 1081.76     267 1081.51   274.5  1080.7
   283.6 1078.14     314 1076.18   360.1 1075.54   392.2  1076.2   403.41071.798
   416.3 1070.89   424.81071.797   428.3 1073.51   432.4 1074.42   448.4 1075.33
   498.7 1074.51   596.2 1074.53   612.6 1075.81     658 1075.19   673.5    1076
   740.5 1085.15   761.2  1090.5     775 1096.19   785.9 1099.31   818.7 1102.63
#Mann= 8 ,-1,0
       0     .05       0     270     .07       0     280     .05       0
   403.4    .045       0   424.8     .05       0  478.64     .07       0
  530.72     .05       0  680.72     .06       0
Bank Sta=403.4,424.8
XS Rating Curve= 0 ,0
Exp/Cntr=0.3,0.1

Type RM Length L Ch R = 1 ,11375   ,172.4,177,178.5
XS GIS Cut Line= 4
2173331.04008353752405.6560401872173539.52493513752899.327267808
2173609.75765629752979.725251239 2173544.3850942753187.160491021
#Sta/Elev= 30
       0 1098.89    24.9 1097.16    29.9 1095.16    43.2 1088.06    61.6 1085.51
      82 1080.25    85.2 1079.98   101.2  1080.3     234 1078.97     260 1077.03
   305.8 1076.49   342.2 1076.75     412 1078.57   490.1 1078.94   519.5 1077.55
   543.3 1074.83     566 1074.27   585.9 1072.27   602.9 1070.44   608.5 1070.99
   612.7 1072.33     617 1073.69   623.3 1074.44   665.1 1074.33   702.9 1075.66
   752.7 1082.07   807.7 1094.02   832.9 1103.13   837.1 1104.12   860.1 1106.09
#Mann= 5 ,-1,0
       0     .05       0   585.9    .045       0   612.7     .05       0
  682.64     .06       0  812.64     .05       0
#XS Ineff= 2 , 0
        485.6098 1083.47
Permanent Ineff=
       T       F
Bank Sta=585.9,612.7
XS Rating Curve= 0 ,0
Exp/Cntr=0.3,0.1

Type RM Length L Ch R = 1 ,11198   ,212.6,221.3,225.4
XS GIS Cut Line= 3
2173148.32193975752587.0610524932173515.56640452753144.354582999
 2173536.1022879753261.865471227
#Sta/Elev= 30
       0 1082.48   136.7 1079.32   198.9 1079.18   241.1 1076.52   268.7 1073.83
   284.4 1073.18   498.1  1074.6   505.5 1074.11   512.5  1072.1   524.1 1071.17
   532.21072.028   561.6 1074.27   593.4 1073.48   606.1 1073.65   616.5  1074.6
   630.1 1078.49   646.7 1086.57   672.3 1097.42   676.4 1098.75   684.5 1099.96
   692.6 1103.71   699.8 1106.11     721 1107.74   730.9 1107.49   737.3 1106.27
   740.7 1106.57   749.5  1111.3   757.6 1114.14   765.7 1115.81   786.7 1118.55
#Mann= 4 ,-1,0
       0     .05       0   512.5    .045       0   532.2     .05       0
  737.42     .07       0
Bank Sta=512.5,532.2
XS Rating Curve= 0 ,0
Exp/Cntr=0.3,0.1

Type RM Length L Ch R = 1 ,10977   ,206.5,204.8,200.9
XS GIS Cut Line= 4
2173129.63288166752728.7287057562173243.00840989752905.644530148
 2173294.9819419753246.6416060192173308.92606025753359.462199894
#Sta/Elev= 30
       0 1082.94    57.5 1081.96   100.3 1078.43   128.8 1077.48   164.3 1073.03
     238 1073.89   270.4 1072.85   371.5 1072.52   420.1  1074.3   424.1 1073.28
   427.8 1070.92   436.2  1070.3     446 1070.98   452.4 1072.42   468.6 1073.33
   472.7 1074.49   492.9 1084.56   513.1 1097.01   537.4 1106.32   553.6 1107.94
   577.8 1113.17   589.9 1116.52   601.5 1122.04     605 1122.83     614  1123.5
   634.2 1122.49   637.3 1122.89   642.3 1125.36   654.3 1133.17   668.7 1139.26
#Mann= 4 ,-1,0
       0     .05       0   427.8    .045       0     446     .05       0
  625.06     .06       0
Bank Sta=427.8,446
XS Rating Curve= 0 ,0
Exp/Cntr=0.3,0.1

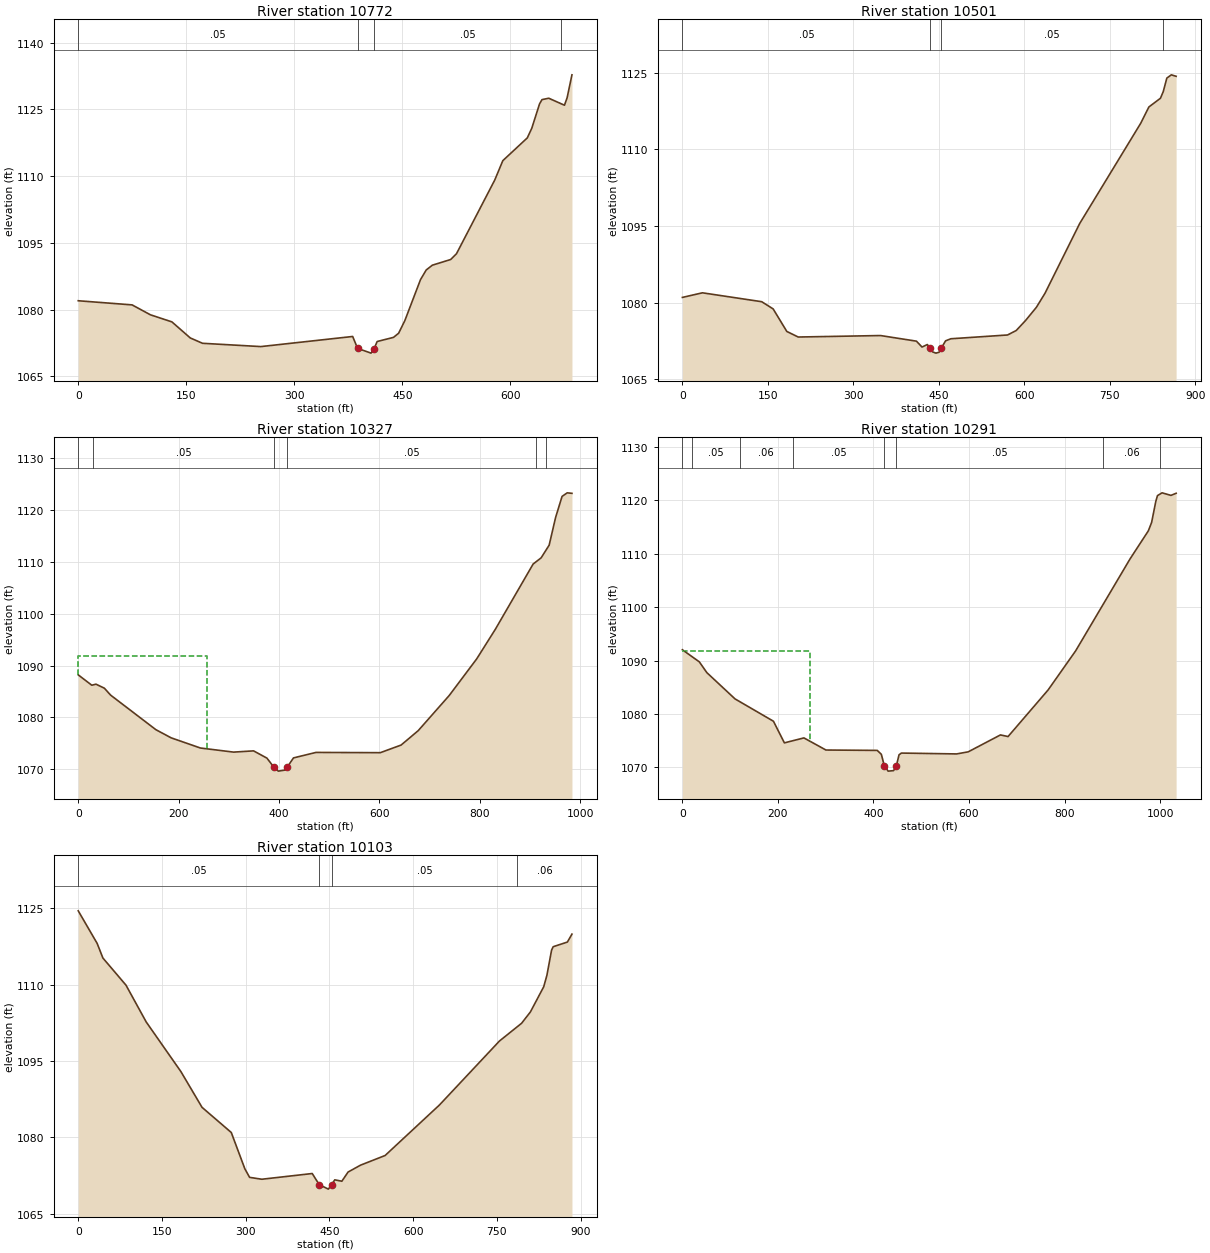
Type RM Length L Ch R = 1 ,10772   ,252.2,271.2,284.2
XS GIS Cut Line= 2
2172941.74276116752778.8530010772173175.16929168753423.472293467
#Sta/Elev= 30
       0 1082.02    74.8 1081.09   100.3 1078.86   130.1 1077.27   155.6 1073.66
   172.6 1072.46   253.6 1071.72   381.1 1073.99   387.9 1071.32   406.6 1070.25
   410.9 1071.27   415.1 1072.86   437.8 1073.79   444.9 1074.72   453.5 1077.54
   475.3 1086.77   483.2 1088.93   491.7 1090.01   517.2 1091.29   525.3  1092.6
   578.4 1109.15   589.6  1113.5   623.6 1118.62   629.8 1120.78   640.6 1126.26
     644 1127.22   653.4 1127.53   675.2 1125.96   678.9 1127.65   685.6 1132.79
#Mann= 4 ,-1,0
       0     .05       0   387.9    .045       0   410.9     .05       0
     670     .07       0
Bank Sta=387.9,410.9
XS Rating Curve= 0 ,0
Exp/Cntr=0.3,0.1

Type RM Length L Ch R = 1 ,10501   ,202.1,173.9,154.9
XS GIS Cut Line= 4
2172916.73290725752773.944662733 2172911.4239797753134.602290147
2172811.26256738753235.785757695 2173034.2018669753522.931296619
#Sta/Elev= 30
       0 1081.04    35.2 1081.94   139.2  1080.2   159.3 1078.79   183.3 1074.38
   203.3 1073.29   347.8 1073.58   410.8 1072.48   420.6 1071.33   429.9 1071.82
  435.26 1071.11   439.2 1070.38   444.9 1070.14   450.6 1070.31   454.4 1071.12
     462 1072.55   471.3 1072.95   570.7 1073.69   585.9 1074.56   602.4 1076.53
   621.3  1079.1   636.5 1081.86   697.3 1095.49   804.6 1115.14   818.8  1118.3
   839.1 1120.01     844  1121.3   850.3 1123.95   858.2 1124.59   866.6  1124.3
#Mann= 4 ,-1,0
       0     .05       0  435.26    .045       0   454.4     .05       0
  843.07     .07       0
Bank Sta=435.26,454.4
XS Rating Curve= 0 ,0
Exp/Cntr=0.3,0.1

Type RM Length L Ch R = 1 ,10327   ,38.4,36,36.4
XS GIS Cut Line= 6
 2172554.5084823 752791.196053082172613.10904084 752994.21710352
2172763.67650094753212.9894129962172714.46643442753337.907274165
2172833.07531271753437.589203785 2173016.3698631753544.025832732
#Sta/Elev= 30
       0  1088.2      27  1086.2    35.4  1086.4      52 1085.63    64.5 1084.29
   154.8 1077.61   185.2 1076.04   243.4 1074.08   309.4 1073.29   349.2 1073.53
   375.8 1072.13   388.9 1070.48   398.5 1069.62   413.8 1069.85  416.72 1070.46
   428.7 1072.17   473.5 1073.23   601.6 1073.18     643 1074.65   677.1 1077.43
   738.9 1084.22   793.5 1091.27   830.5 1096.96     906 1109.59   921.9 1110.78
   937.9 1113.23   950.7 1118.57   963.6 1122.64   973.9 1123.33   983.3 1123.23
#Mann= 6 ,-1,0
       0     .06       0      30     .05       0   388.9    .045       0
  416.72     .05       0  911.39     .06       0  931.39     .07       0
#XS Ineff= 2 , 0
        257.0772  1091.8
Permanent Ineff=
       T       F
Bank Sta=388.9,416.72
XS Rating Curve= 0 ,0
Exp/Cntr=0.3,0.1

Type RM Length L Ch R = 1 ,10291   ,189.7,188,183.1
XS GIS Cut Line= 6
2172496.12002573752804.543317442 2172559.0147238752995.219739698
 2172719.6122261753196.7509826072172670.30355421 753325.28930839
2172696.80128234753368.1903920242173004.79540492753595.529747169
#Sta/Elev= 30
       0 1092.03    35.4 1089.77    51.2 1087.75   110.2 1082.83   190.6 1078.65
   213.5  1074.6   254.4 1075.53   300.5 1073.26   407.9 1073.19   416.5 1072.45
  422.72 1070.29   430.7 1069.31   442.1  1069.4   447.8 1070.28   453.5 1072.37
   458.5 1072.69     574 1072.53   598.3 1072.92   665.8 1076.09   681.7 1075.78
   765.5  1084.5   823.2 1091.83   937.2 1109.06   975.4  1114.3   982.2 1115.86
   990.9 1119.78   994.5 1120.89  1004.1 1121.41  1022.7 1120.93  1033.5 1121.33
#Mann= 8 ,-1,0
       0     .06       0      20     .05       0     120     .06       0
  230.78     .05       0  422.72    .045       0   447.8     .05       0
  879.73     .06       0  999.73     .07       0
#XS Ineff= 2 , 0
        268.1557  1091.8
Permanent Ineff=
       T       F
Bank Sta=422.72,447.8
XS Rating Curve= 0 ,0
Exp/Cntr=0.3,0.1

Type RM Length L Ch R = 1 ,10103   ,133.1,136.3,135.4
XS GIS Cut Line= 3
     2172294.009      753059.199     2172639.056      753342.484
2172941.82717806753659.004881656
#Sta/Elev= 30
       0 1124.47    33.9 1118.08    44.2 1115.21    85.6 1109.88   121.8 1102.66
   183.9 1092.93   221.8 1085.91   274.2 1080.97   298.5 1073.85     307 1072.17
   328.9  1071.8   419.2 1072.92  431.77 1070.74   448.1 1069.86   453.8 1070.73
   459.6 1071.68   472.3 1071.41   483.4 1073.21   505.7 1074.56   549.8 1076.46
   647.2 1086.38   754.6 1098.92   794.3 1102.41     810 1104.62   833.9 1109.57
   839.6 1111.81     848 1116.76   850.9 1117.43   876.3 1118.34   884.5  1119.9
#Mann= 4 ,-1,0
       0     .05       0  431.77    .045       0   453.8     .05       0
  786.44     .06       0
Bank Sta=431.77,453.8
XS Rating Curve= 0 ,0
Exp/Cntr=0.3,0.1