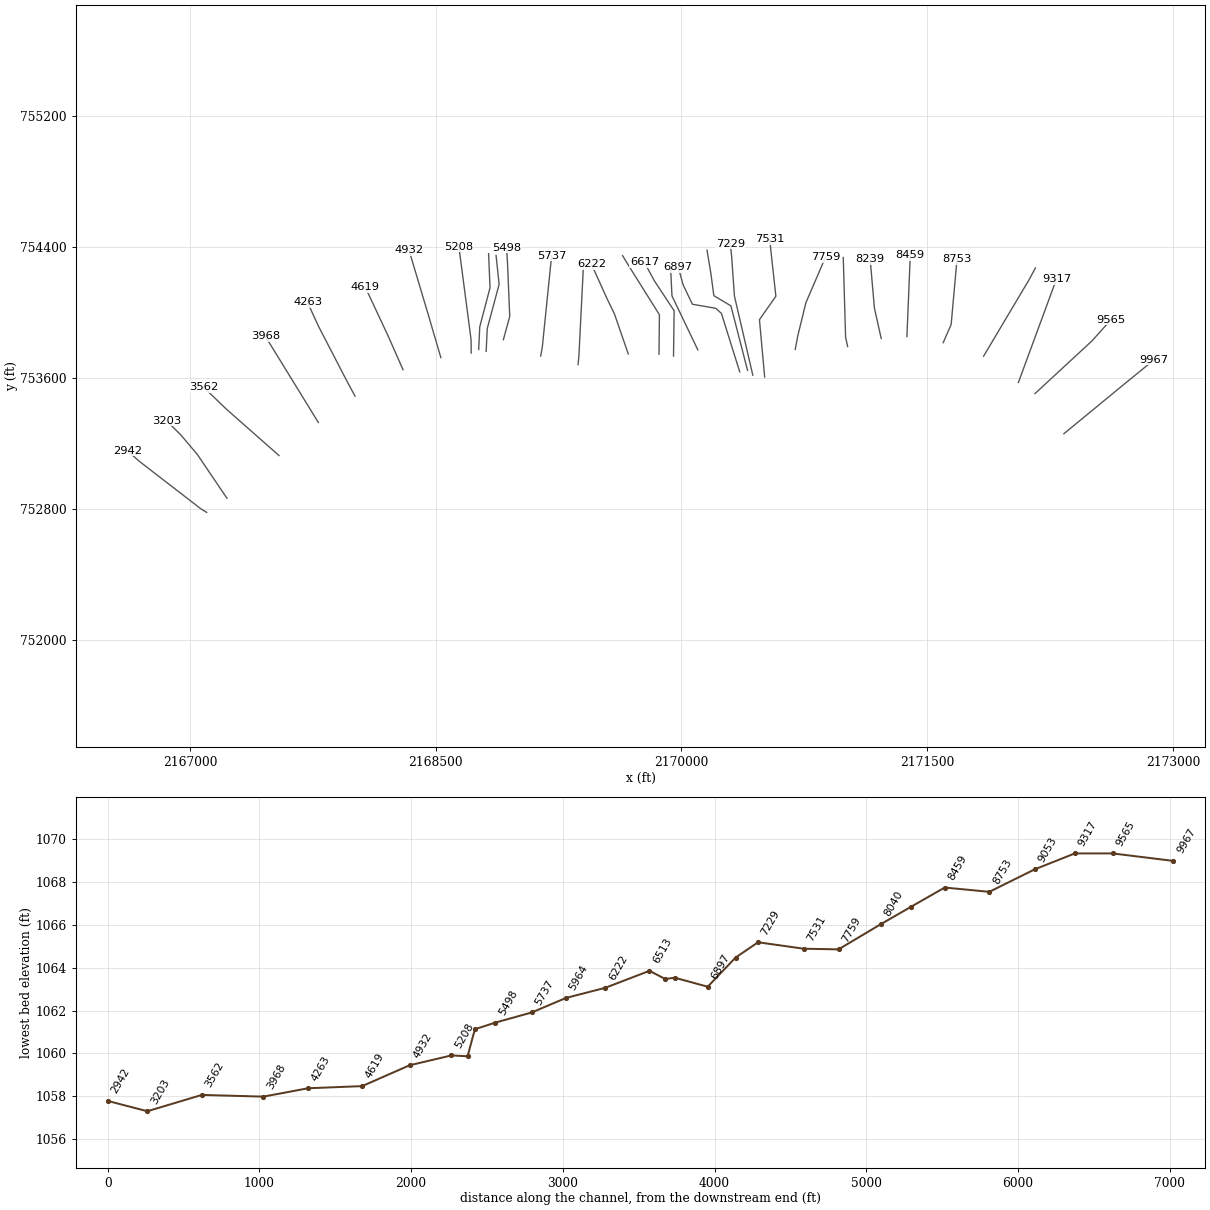
HEC-RAS study HACKERSCK.prj: HACKERSCK

--- HACKERSCK.g01 (geometry) --- (continued)

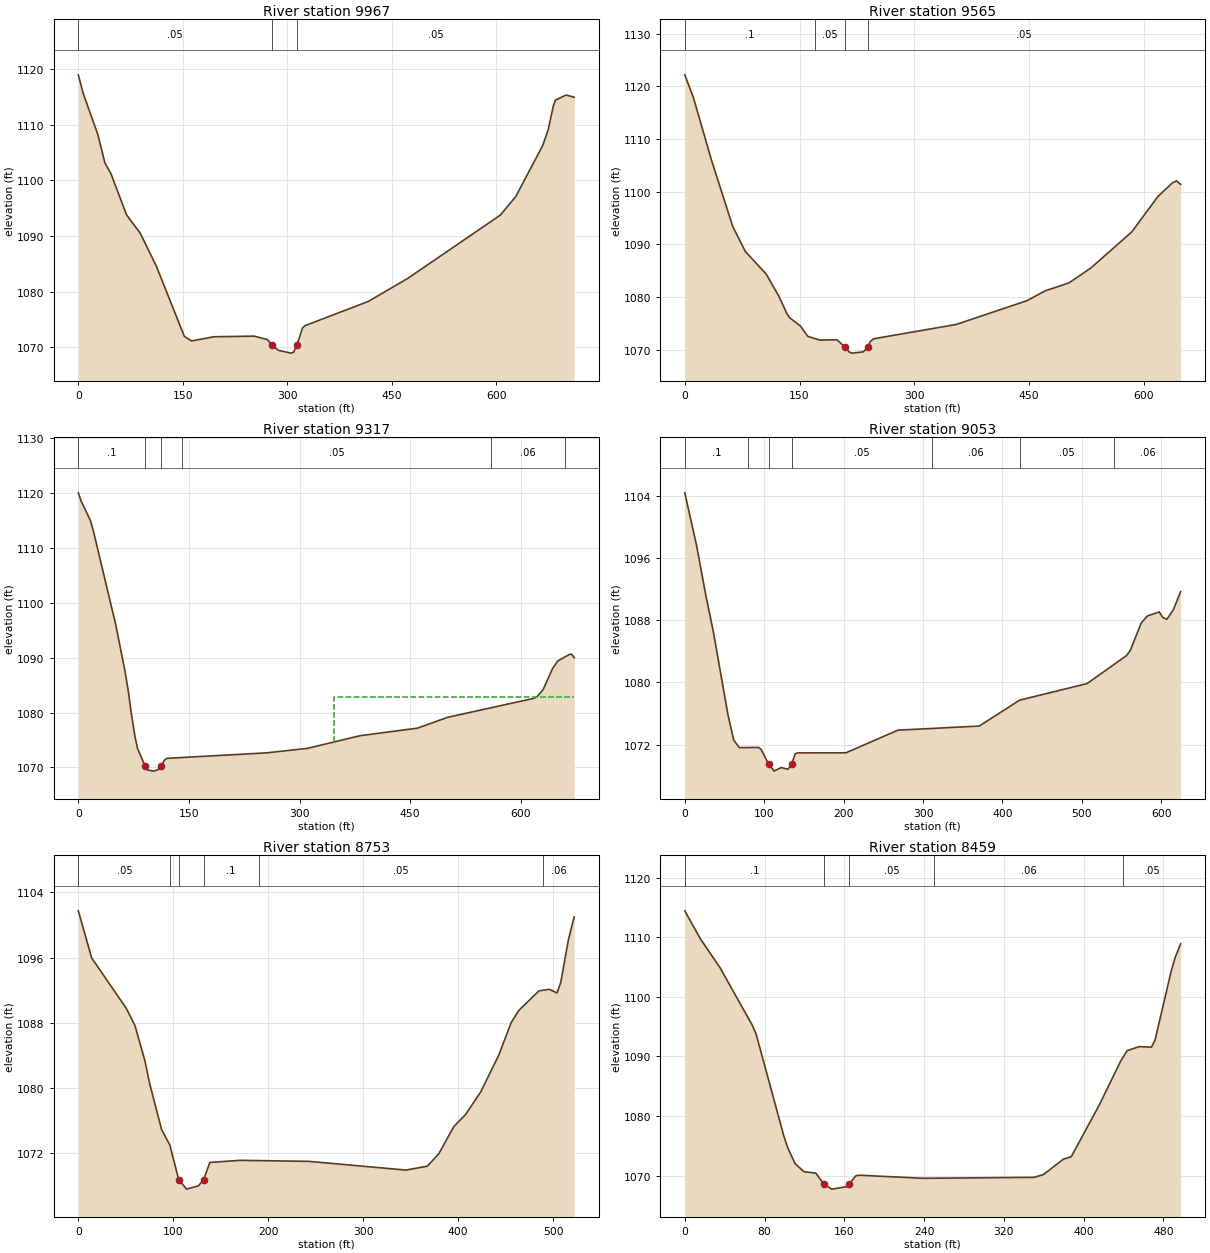
Type RM Length L Ch R = 1 ,9967    ,390.3,401.6,398
XS GIS Cut Line= 3
 2172334.6653384753260.750094443 2172722.7844573753580.009369663
2172885.14792184753712.033056846
#Sta/Elev= 30
       0 1118.94     7.1 1115.56    27.9 1108.26    38.2 1103.11    46.8  1101.2
    69.3 1093.78    88.8 1090.52   112.2 1084.53   152.2 1071.98   162.5 1071.16
   194.6 1071.91   252.5 1072.02   271.3 1071.41  277.98 1070.49   286.8 1069.49
   305.4 1068.97   309.2 1069.15     314 1070.48   321.8 1073.48   325.3  1073.9
   416.3 1078.25   473.3 1082.42   605.9 1093.76   628.1 1097.11   666.5 1106.21
   674.5 1109.06   681.9 1113.35   684.8 1114.39   700.3 1115.32   711.8 1114.92
#Mann= 3 ,-1,0
       0     .05       0  277.98    .045       0     314     .05       0
Bank Sta=277.98,314
XS Rating Curve= 0 ,0
Exp/Cntr=0.3,0.1

Type RM Length L Ch R = 1 ,9565    ,232,248.3,254.5
XS GIS Cut Line= 3
 2172158.1372164753505.6733238352172505.91420466753827.367037973
2172622.26813534753957.182898031
#Sta/Elev= 30
       0 1122.18    11.1 1117.93    34.6 1106.12    62.7 1093.37    79.1 1088.63
   106.3 1084.36     123 1080.12   133.5 1076.81     137 1076.06   151.1 1074.47
   160.8  1072.5   176.6 1071.79   198.9 1071.86   209.8 1070.41   215.3 1069.49
     219 1069.32   233.2 1069.56  239.05 1070.42   242.5 1071.53   246.7 1072.04
   354.9 1074.77     447 1079.27   471.4 1081.17   502.1 1082.65   531.1 1085.53
   584.3 1092.35   618.3 1099.05   637.3 1101.66   642.7 1102.04   648.1 1101.38
#Mann= 4 ,-1,0
       0      .1       0     170     .05       0   209.8    .045       0
  239.05     .05       0
Bank Sta=209.8,239.05
XS Rating Curve= 0 ,0
Exp/Cntr=0.3,0.1

Type RM Length L Ch R = 1 ,9317    ,263,263.8,259.4
XS GIS Cut Line= 2
2172056.91558588753573.7061005162172289.28800175754204.599152757
#Sta/Elev= 30
       0 1120.04     3.7 1118.57    16.5 1114.96    20.8 1112.86    50.6 1096.08
    63.4 1087.46    67.6 1084.03    71.9 1079.79    76.9 1075.54    80.4 1073.41
   90.59 1070.23    93.2 1069.56   101.8 1069.32     108 1069.57     1121070.257
   117.4 1071.43   120.5 1071.65   255.2 1072.65   310.3 1073.46   382.2 1075.78
   459.8 1077.15   500.6 1079.12   617.5 1082.58   622.1  1082.9   630.3 1084.19
   643.1 1088.04   650.1  1089.4   665.7 1090.58   668.7 1090.65   672.3    1090
#Mann= 6 ,-1,0
       0      .1       0   90.59    .045       0     112      .1       0
     140     .05       0     560     .06       0     660     .05       0
#XS Ineff= 2 , 0
                          347.18         1082.77
Permanent Ineff=
       F       F
Bank Sta=90.59,112
XS Rating Curve= 0 ,0
Exp/Cntr=0.3,0.1

Type RM Length L Ch R = 1 ,9053    ,294.9,300,305.1
XS GIS Cut Line= 4
2171844.69909415 753734.43953012     2171906.831      753839.026
2172121.23067987754199.495595852 2172160.8875032754272.849221812
#Sta/Elev= 30
       0 1104.39    14.6 1097.73    26.4 1091.24    35.8  1086.6    54.4 1075.81
    61.6 1072.58    68.7  1071.6      93 1071.63    96.2 1071.37   105.5  1069.5
   112.5 1068.58   121.3 1069.04     130 1068.82   134.7 1069.51   138.8 1070.75
   141.7 1070.93     203 1070.94   268.4 1073.85   370.8 1074.38   421.6 1077.71
   506.5 1079.84   556.6 1083.47   561.2 1084.15   574.8 1087.64   582.8 1088.56
   597.5 1089.06   602.1 1088.33   607.2 1088.13   615.3 1089.36   624.4 1091.68
#Mann= 7 ,-1,0
       0      .1       0      80     .05       0   105.5    .045       0
   134.7     .05       0  311.65     .06       0  421.65     .05       0
  541.06     .06       0
Bank Sta=105.5,134.7
XS Rating Curve= 0 ,0
Exp/Cntr=0.3,0.1

Type RM Length L Ch R = 1 ,8753    ,283.4,294.1,291
XS GIS Cut Line= 4
2171598.17032137753816.8589881622171616.65261641753859.984343259
     2171646.386      753926.4632171682.36744323754327.175690143
#Sta/Elev= 30
       0 1101.74      14 1095.96    50.5 1089.75    59.6 1087.65    70.1 1083.31
    75.1 1080.51    87.7 1074.85    96.4 1072.94   105.7  1068.7     114 1067.53
   126.5 1067.94  131.84 1068.68   138.5 1070.81   170.7 1071.07     243 1070.94
     345 1069.87   367.5 1070.35   379.5 1071.87   395.6 1075.25   407.7 1076.69
   423.7 1079.48   442.9 1084.05   455.8 1088.01   463.8 1089.49     485  1091.9
   496.1 1092.09     504 1091.64     508 1092.94     516 1098.16   522.1 1100.98
#Mann= 6 ,-1,0
       0     .05       0   96.92      .1       0   105.7    .045       0
  131.84      .1       0  189.74     .05       0  489.74     .06       0
Bank Sta=105.7,131.84
XS Rating Curve= 0 ,0
Exp/Cntr=0.3,0.1

Type RM Length L Ch R = 1 ,8459    ,211.5,220.3,221
XS GIS Cut Line= 2
2171376.48841813 753853.772872362171397.02430151754350.741250145
#Sta/Elev= 30
       0 1114.45    15.4 1109.81    35.4 1104.89    67.5 1095.31    71.5 1093.79
    99.5 1076.56   103.5 1074.58   110.6 1072.03   119.5 1070.66   131.5 1070.41
   139.5 1068.55   147.5 1067.73   163.5 1068.17  164.86 1068.56   171.6 1069.97
   175.6 1070.06   239.6 1069.55   350.5 1069.71   359.7 1070.17   379.7 1072.75
   387.7 1073.18   415.8 1081.85   437.4 1089.27   443.8 1090.98   455.8 1091.65
   468.2 1091.57   471.8 1092.79   487.8 1104.22   491.8 1106.55   497.4 1108.91
#Mann= 5 ,-1,0
       0      .1       0   139.5    .045       0  164.86     .05       0
     250     .06       0     440     .05       0
Bank Sta=139.5,164.86
XS Rating Curve= 0 ,0
Exp/Cntr=0.3,0.1

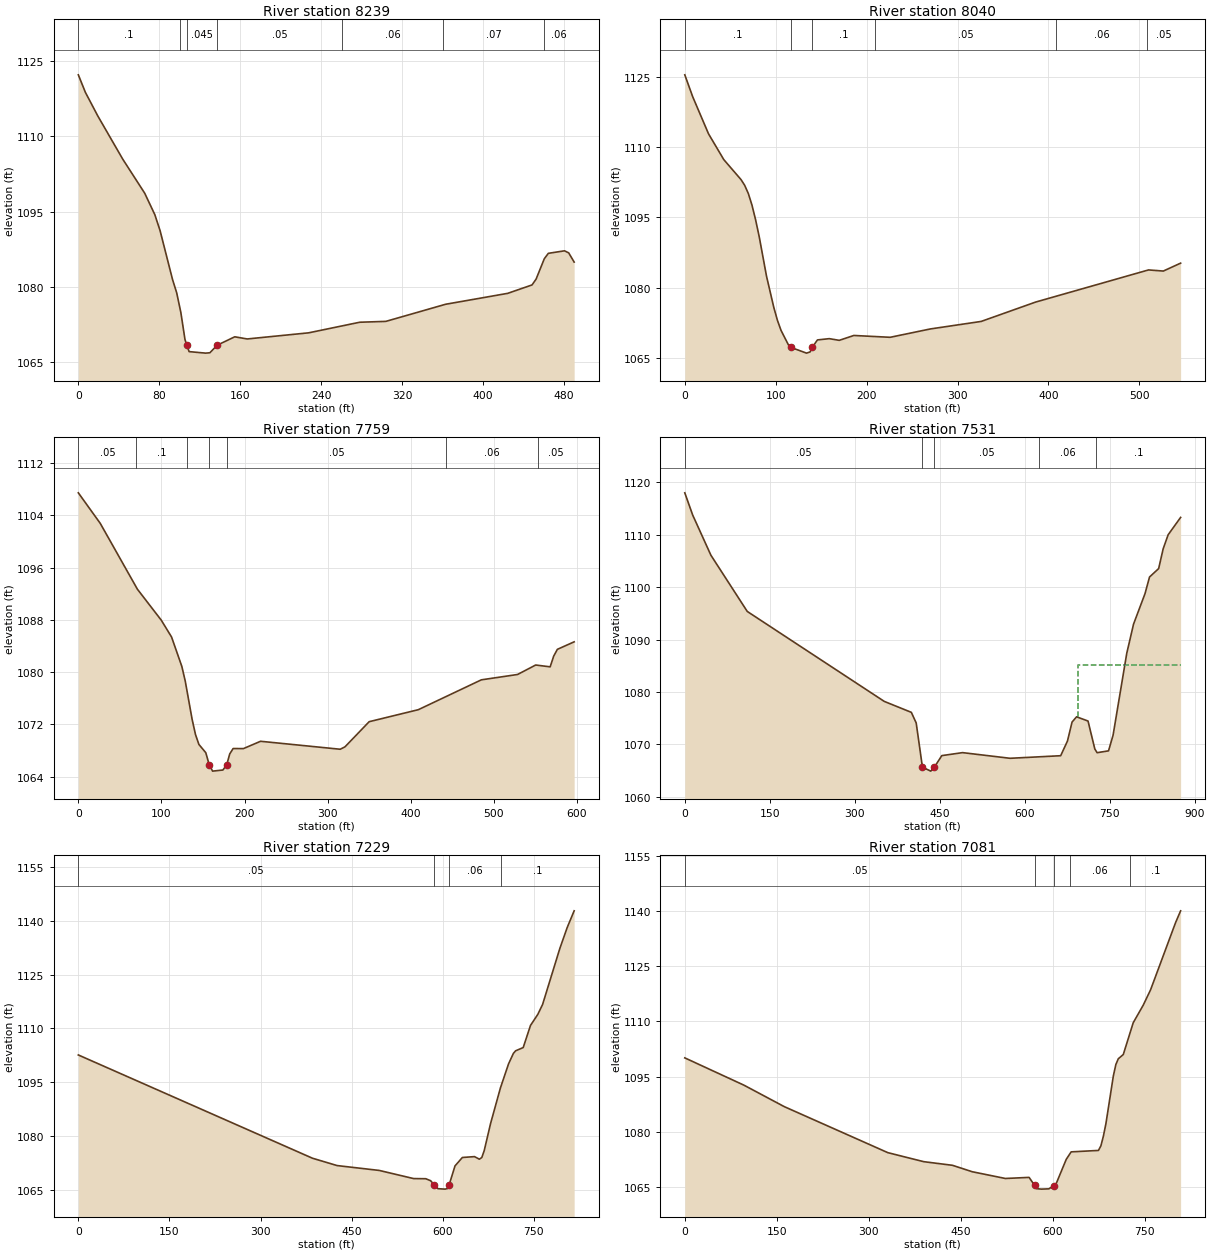
Type RM Length L Ch R = 1 ,8239    ,201.4,199.2,196.1
XS GIS Cut Line= 3
2171219.60835408753842.3147508722171178.02319024 754028.06181604
2171152.14797718754326.550880962
#Sta/Elev= 30
       0 1122.25       7 1118.75    19.3 1114.04    43.9 1105.46    65.6 1098.68
    75.6 1094.41    80.8 1091.22    93.1  1081.5    97.2 1078.85   101.3 1074.95
   105.4 1069.55   107.3 1068.37   109.5 1067.14   125.8 1066.84     130 1066.91
  137.15 1068.41   154.6 1070.09   166.9 1069.66   227.6 1070.88   278.1 1072.99
   303.9 1073.16     363 1076.57   424.3 1078.74   448.4 1080.42   452.4 1081.58
   460.5 1085.63   464.5 1086.71   480.5 1087.21   484.6  1086.8     490 1084.97
#Mann= 7 ,-1,0
       0      .1       0     100     .05       0   107.3    .045       0
  137.15     .05       0  260.35     .06       0  360.35     .07       0
  460.35     .06       0
Bank Sta=107.3,137.15
XS Rating Curve= 0 ,0
Exp/Cntr=0.3,0.1

Type RM Length L Ch R = 1 ,8040    ,283.7,280.3,275.9
XS GIS Cut Line= 3
2171014.64923759 753792.648209862171002.17368844753850.035735964
2170987.90588144 754336.53970554
#Sta/Elev= 30
       0 1125.47     8.7 1120.79    26.1 1112.87    42.9 1107.36    61.9 1103.08
    65.9 1101.86    69.9 1100.11    73.9 1097.64    77.9  1094.5    81.9 1090.85
    89.9 1082.45    97.9  1075.8   101.9 1073.03   105.9 1070.87   113.9 1067.83
  116.87 1067.24   133.9 1066.03   137.9 1066.29   140.21067.261   145.9 1068.85
   158.9 1069.12   169.9 1068.76   185.9  1069.8   225.9 1069.41     270 1071.19
     326  1072.8     386 1076.94   510.1  1083.8   526.4 1083.56   545.4 1085.25
#Mann= 6 ,-1,0
       0      .1       0  116.87    .045       0   140.2      .1       0
  208.73     .05       0  408.73     .06       0  508.73     .05       0
Bank Sta=116.87,140.2
XS Rating Curve= 0 ,0
Exp/Cntr=0.3,0.1

Type RM Length L Ch R = 1 ,7759    ,233.3,228.2,222.2
XS GIS Cut Line= 4
2170694.63788338753775.247600554 2170709.5669068753855.171569155
2170759.76573284 754060.53040295     2170879.982  754339.7328241
#Sta/Elev= 30
       0 1107.47    26.4 1102.79    71.1 1092.71    99.8 1087.97   112.2 1085.39
   124.6 1080.87   128.7 1078.62   136.9 1072.81     141 1070.45   145.1 1068.94
   153.4 1067.67   157.5 1065.83   161.6 1064.85     174 1065.02  178.56 1065.82
   182.2 1067.48   186.3 1068.31   198.7  1068.3   219.3 1069.42   315.2  1068.2
   320.9 1068.57     350 1072.42   409.2 1074.26     485 1078.83   528.6 1079.65
   550.4  1081.1   567.8 1080.82   572.1 1082.47   576.5  1083.5   596.7 1084.65
#Mann= 7 ,-1,0
       0     .05       0      70      .1       0  131.31     .05       0
   157.5    .045       0  178.56     .05       0  442.71     .06       0
  552.71     .05       0
Bank Sta=157.5,178.56
XS Rating Curve= 0 ,0
Exp/Cntr=0.3,0.1

Type RM Length L Ch R = 1 ,7531    ,281.3,302.2,306.7
XS GIS Cut Line= 4
2170508.08300421753607.2971724342170476.39182616753957.167778159
2170576.53594881754100.4119029672170538.50653514754447.747214448
#Sta/Elev= 30
       0    1118    13.9 1113.77    46.1 1106.09   110.3 1095.36   352.2 1078.19
     400  1076.1   408.6 1074.07   419.6 1065.64   434.3 1064.88  440.71 1065.64
   453.8 1067.84   490.5 1068.41   574.3 1067.33   663.7 1067.82   675.7 1070.63
   683.8 1074.24   691.8 1075.25     712 1074.44     724 1069.11     728  1068.4
   748.2 1068.75   756.2 1071.72   780.4 1087.37   792.4 1092.95   812.6 1098.75
   820.6 1101.93   836.7 1103.54   844.7 1107.32   853.5    1110   875.5 1113.31
#Mann= 5 ,-1,0
       0     .05       0   419.6    .045       0  440.71     .05       0
  626.08     .06       0  726.08      .1       0
#XS Ineff= 2 , 0
                          694.04          1085.1
Permanent Ineff=
       F       F
Bank Sta=419.6,440.71
XS Rating Curve= 0 ,0
Exp/Cntr(USF)=0,0
Exp/Cntr=0.3,0.1

Type RM Length L Ch R = 1 ,7229    ,142,147.9,141.9
XS GIS Cut Line= 4
2170435.85435727753618.1244758862170323.72781558754100.831494164
2170305.52183926754355.3544137362170297.79055927754420.605826326
#Sta/Elev= 30
       0  1102.6   385.5  1073.8   426.1 1071.75   495.6 1070.39   552.1 1068.12
   572.1 1068.08   580.1 1067.52  585.76 1066.41   592.2  1065.3     604 1065.18
   608.2 1065.36   610.61066.393   620.2 1071.65   632.3    1074   652.3 1074.25
   660.3 1073.53   664.3 1073.99   668.3 1075.91   678.8  1083.5   695.1 1093.46
   708.4 1100.12   716.3 1103.02     720 1103.76   732.5 1104.66   744.5 1110.83
   756.6 1113.93   764.4 1116.67   792.8 1132.29   804.9 1138.12   816.4  1142.8
#Mann= 4 ,-1,0
       0     .05       0  585.76    .045       0   610.6     .06       0
  695.56      .1       0
Bank Sta=585.76,610.6
XS Rating Curve= 0 ,0
Exp/Cntr=0.3,0.1

Type RM Length L Ch R = 1 ,7081    ,174.2,184.2,206.8
XS GIS Cut Line= 5
2170403.51855267753647.9700806512170302.05104979754041.505608846
2170197.99456324754103.6465077352170179.59756914754240.704113776
2170156.29470995754381.441118637
#Sta/Elev= 30
       0 1100.12    96.3 1092.72   162.4 1086.86     331 1074.38   389.5 1071.93
   436.5 1070.94   468.8 1069.19   522.8 1067.36   561.4 1067.66   570.51065.467
   573.5 1064.59   581.6 1064.47   593.7 1064.55  601.97 1065.45   605.8 1066.05
     622 1072.56     630 1074.59   674.5 1074.98   678.5 1076.23   682.6 1078.89
   686.7 1082.27   698.8 1095.21   702.9 1098.32   706.9 1099.88     715 1101.03
   731.2 1109.66   747.5 1114.43   759.5  1118.6   800.2 1136.83   808.5 1140.06
#Mann= 5 ,-1,0
       0     .05       0   570.5    .045       0  601.97     .05       0
  627.61     .06       0  725.89      .1       0
Bank Sta=570.5,601.97
XS Rating Curve= 0 ,0
Exp/Cntr=0.3,0.1

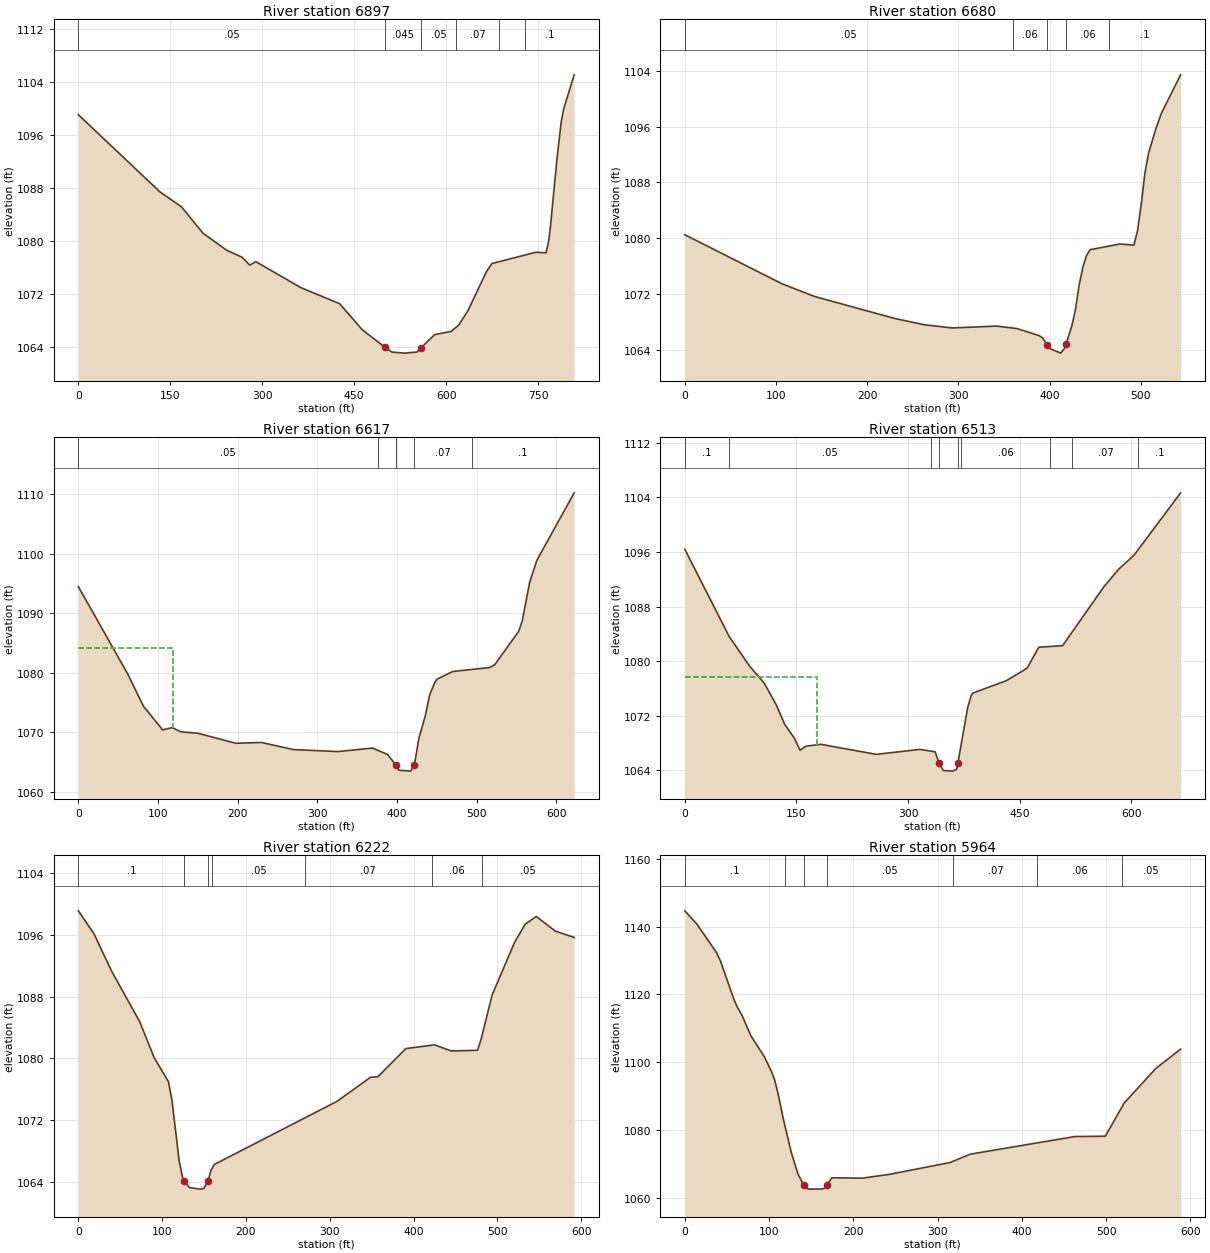
Type RM Length L Ch R = 1 ,6897    ,276.6,216.8,186.2
XS GIS Cut Line= 6
2170356.05541469753638.2804561192170244.18776493753995.350310586
 2170209.5575173754026.5144117062170066.87960054754051.451517432
2170009.97637965754170.7802495352169980.83039769754277.413274213
#Sta/Elev= 30
       0 1099.12   132.8 1087.49   168.2 1085.21   203.3 1081.23     242 1078.65
   267.1 1077.59   279.7  1076.4   289.5 1076.93   363.5 1072.98   426.3 1070.58
   463.2 1066.64  500.66 1063.97   511.4 1063.27   531.9 1063.11   552.5 1063.27
   559.61063.958   581.4 1065.91     608 1066.38   620.5 1067.34   635.5  1069.5
   665.7 1075.38   674.5 1076.63   746.5 1078.35     763 1078.25   767.2 1079.98
   770.2 1082.19     781  1092.6   787.9 1098.08   792.1 1100.09   808.9 1105.14
#Mann= 6 ,-1,0
       0     .05       0  500.66    .045       0   559.6     .05       0
  616.16     .07       0  686.16     .06       0  728.36      .1       0
Bank Sta=500.66,559.6
XS Rating Curve= 0 ,0
Exp/Cntr=0.3,0.1

Type RM Length L Ch R = 1 ,6680    ,57.7,63,70.7
XS GIS Cut Line= 3
2170100.10330846753772.8232995412169942.46226936754102.050546586
2169933.36759403754280.306183107
#Sta/Elev= 30
       0 1080.51   106.8 1073.46   142.3 1071.65   231.1 1068.47   262.1 1067.61
   293.1 1067.14   341.9 1067.41   364.1 1067.05   388.2 1066.05   392.2 1065.71
   396.9 1064.76   400.2 1064.18   412.1 1063.53   416.2 1064.21  417.85 1064.81
   424.2  1067.4   428.2 1069.75   432.2 1073.23   436.2 1075.78   440.2 1077.49
   444.3 1078.36   476.9 1079.18   492.3 1079.02   496.3  1081.1     501 1085.57
   504.3  1089.3   508.3 1092.18   516.3 1095.68   522.6 1097.98   543.5 1103.44
#Mann= 5 ,-1,0
       0     .05       0     360     .06       0   396.9    .045       0
  417.85     .06       0  465.02      .1       0
Bank Sta=396.9,417.85
XS Rating Curve= 0 ,0
Exp/Cntr(USF)=0,0
Exp/Cntr=0.3,0.1

Type RM Length L Ch R = 1 ,6617    ,96.7,103.8,96.5
XS GIS Cut Line= 4
2169951.80750228753735.3262358932169955.50396129754011.636546764
2169835.36904352754193.6871529242169774.37746989754306.429152677
#Sta/Elev= 30
       0 1094.45    61.9 1079.81    81.9 1074.34   105.9 1070.39   117.9 1070.78
   128.5 1070.08   149.9 1069.83   197.9 1068.15   229.9 1068.28   269.9 1067.09
   326.1 1066.75   369.4 1067.34   388.4 1066.26   398.6 1064.51   402.8 1063.62
   417.2 1063.47     422 1064.49   427.6 1068.96   435.8 1072.82   441.1 1076.23
   447.3 1078.27   450.7 1078.93   470.4  1080.2   516.6 1080.86     523 1081.36
     553 1086.94   557.5 1088.75   566.6 1095.09   575.7 1098.84   622.6 1110.19
#Mann= 5 ,-1,0
       0     .05       0  376.34     .07       0   398.6    .045       0
     422     .07       0  494.45      .1       0
#XS Ineff= 2 , 0
          119.48  1084.2
Permanent Ineff=
       F       F
Bank Sta=398.6,422
XS Rating Curve= 0 ,0
Exp/Cntr(USF)=0,0
Exp/Cntr=0.3,0.1

Type RM Length L Ch R = 1 ,6513    ,294,291.2,281.2
XS GIS Cut Line= 4
2169863.23462313753746.3309090192169865.76991738753987.183862235
2169680.69343754754282.5456417062169640.69212835754348.040743019
#Sta/Elev= 30
       0 1096.41    59.2 1083.68    86.9 1079.28   106.9 1076.73   122.9 1073.57
   134.4 1070.68   146.9 1068.74   154.9 1066.92   162.9 1067.51   182.9 1067.78
   257.4 1066.31     316 1067.04   336.3 1066.69   341.8 1064.97   347.1 1063.95
   359.6 1063.85   365.4 1064.14  366.85 1064.99   380.1 1073.17   384.8 1074.94
     387  1075.3   431.8 1077.11   455.6 1078.66   460.4 1079.04   475.6 1082.03
   507.6 1082.25   562.7 1090.84     583 1093.48   603.4  1095.5   666.2 1104.68
#Mann= 9 ,-1,0
       0      .1       0      60     .05       0  330.87     .07       0
   341.8    .045       0  366.85     .07       0  370.87     .06       0
  490.87      .1       0  520.87     .07       0  609.42      .1       0
#XS Ineff= 2 , 0
          176.97 1077.69
Permanent Ineff=
       F       F
Bank Sta=341.8,366.85
XS Rating Curve= 0 ,0
Exp/Cntr=0.3,0.1

Type RM Length L Ch R = 1 ,6222    ,262.7,258,247.7
XS GIS Cut Line= 4
2169675.62284905753747.5985561412169590.69049186753993.522097846
2169546.32284258754084.792690644     2169451.399      754294.321
#Sta/Elev= 30
       0 1099.14    18.6 1096.18    39.8  1091.3    73.2 1084.78    90.5 1080.11
   107.5 1076.99   111.7 1074.63   120.3 1066.74   124.4 1064.55   126.3 1064.11
   132.7 1063.26   145.6 1063.06   149.8 1063.14   154.9  1064.1   158.2  1065.5
   162.5 1066.27   308.7 1074.44   348.7 1077.56   357.6 1077.64   390.8 1081.28
     425 1081.76   445.2 1080.97   476.3 1081.06   480.6 1082.46   493.8 1088.23
   520.7 1095.08   533.3 1097.41   546.5 1098.41   569.1 1096.52   591.7 1095.69
#Mann= 7 ,-1,0
       0      .1       0   126.3    .045       0   154.9      .1       0
     160     .05       0  270.18     .07       0  421.66     .06       0
  481.66     .05       0
Bank Sta=126.3,154.9
XS Rating Curve= 0 ,0
Exp/Cntr=0.3,0.1

Type RM Length L Ch R = 1 ,5964    ,226.3,227.3,224.1
XS GIS Cut Line= 3
2169368.91759973753682.9712437932169374.05157057753731.230569735
2169401.07944256754270.385765014
#Sta/Elev= 30
       0 1144.67    14.3 1140.77    37.7 1132.35    42.4 1129.83    58.5  1118.4
    62.5  1116.2    67.7 1113.98    78.5 1107.78    94.5  1101.6   102.5 1097.46
   106.6  1094.8   110.6 1090.85   117.2 1082.97   126.6 1073.18   134.6 1066.86
   141.1 1063.82   146.6 1062.59   162.6 1062.62   166.6 1062.92  168.55 1063.77
   174.6 1065.94   210.7 1065.83   242.7 1066.94   314.8 1070.44   338.8  1072.9
     463  1078.1     499 1078.19   521.5    1088   559.1 1098.22   588.4 1103.87
#Mann= 7 ,-1,0
       0      .1       0  118.53     .05       0   141.1    .045       0
  168.55     .05       0  318.53     .07       0  418.53     .06       0
  518.53     .05       0
Bank Sta=141.1,168.55
XS Rating Curve= 0 ,0
Exp/Cntr=0.3,0.1

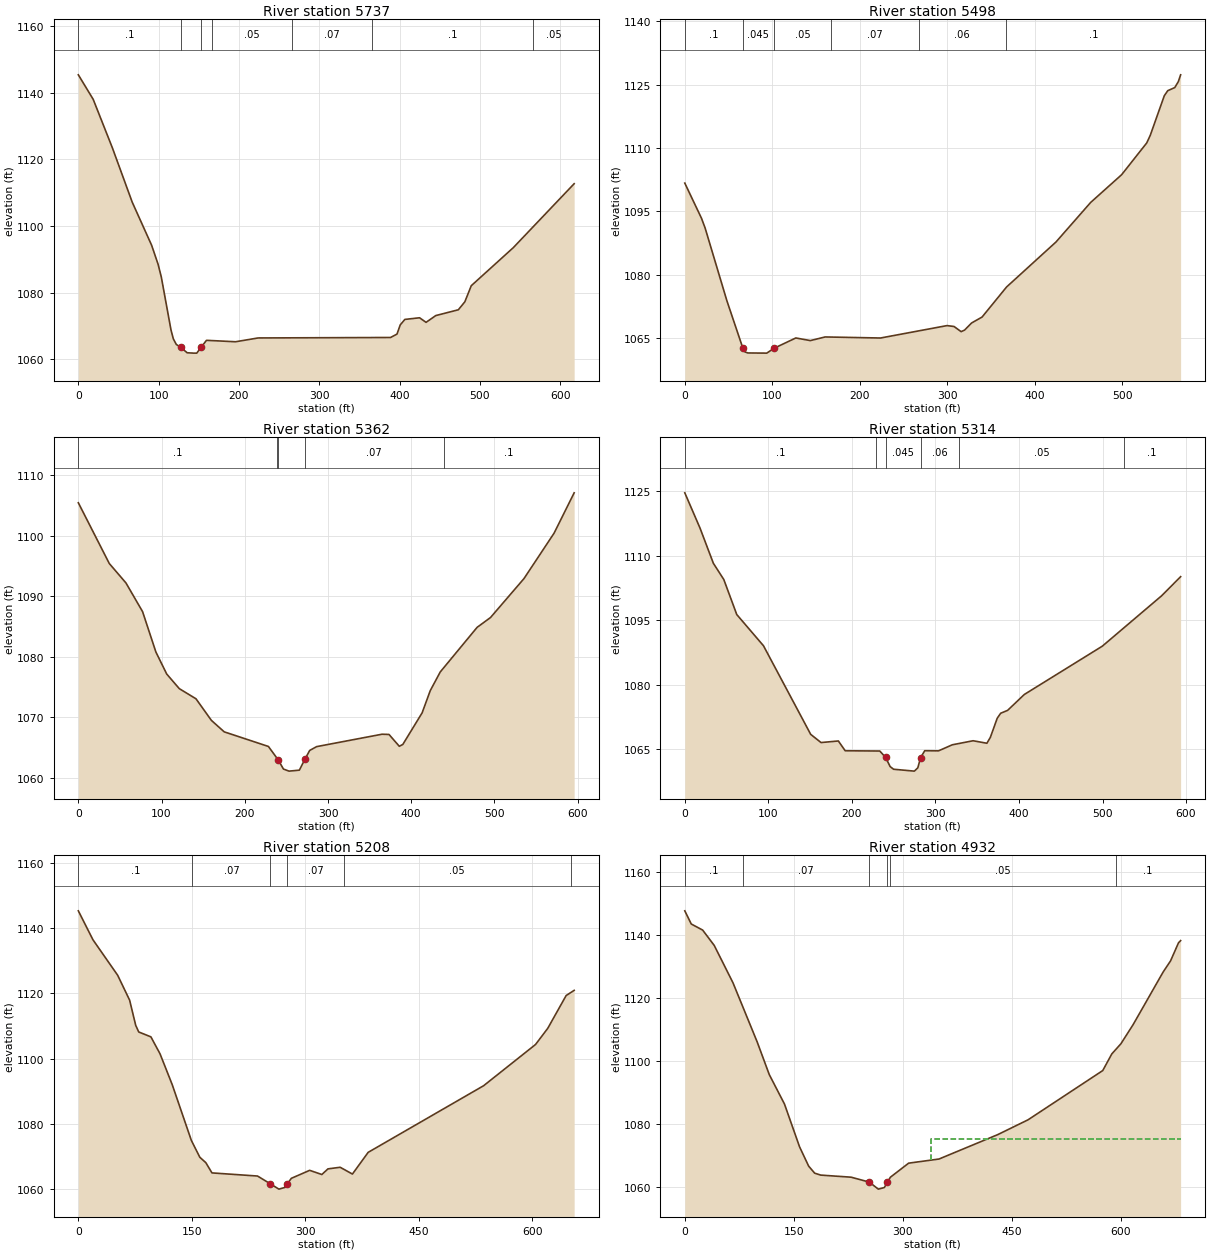
Type RM Length L Ch R = 1 ,5737    ,234.6,238.8,233.4
XS GIS Cut Line= 3
2169140.96612009753734.998174765   2169150.91715753790.090118695
2169207.78396735754348.644562673
#Sta/Elev= 30
       0 1145.36    18.5 1138.02    42.5  1123.4    67.1 1107.18    91.3 1094.24
    99.3 1088.57   103.3 1084.77   115.4 1068.84   118.3  1066.2     122 1064.51
   127.4 1063.67   135.5 1062.02   143.5 1061.91   147.5 1061.91  152.86 1063.66
   159.6 1065.75   195.8 1065.32   223.9 1066.46   388.8  1066.6   396.8 1067.62
   400.8 1070.36   406.6 1072.02   424.9 1072.51     433 1071.14   445.1 1073.17
   473.2 1074.91   481.3 1077.31   489.3 1082.13   541.6 1093.53   617.4 1112.71
#Mann= 7 ,-1,0
       0      .1       0   127.4    .045       0  152.86      .1       0
  165.98     .05       0  265.98     .07       0  365.98      .1       0
  565.98     .05       0
Bank Sta=127.4,152.86
XS Rating Curve= 0 ,0
Exp/Cntr=0.3,0.1

Type RM Length L Ch R = 1 ,5498    ,134.8,135.6,134.9
XS GIS Cut Line= 4
2168913.15581975753834.7836886952168951.97662551753976.708319613
2168938.66937308754297.745784485 2168932.8188144754395.853886288
#Sta/Elev= 30
       0 1101.71    19.1 1093.37    23.2 1091.09    48.1 1073.85    66.3 1062.66
    68.8 1061.72    72.1 1061.48    93.7 1061.44     102 1062.59   126.9 1065.03
   143.5 1064.41   160.4 1065.27   223.7 1065.02   299.7 1067.96   307.7 1067.75
   315.8 1066.53   319.8  1066.9   327.8 1068.58   339.8 1069.99   367.8 1077.11
   424.2 1087.75   463.9 1097.13   499.3  1103.7     528 1111.23     532 1113.02
     548 1122.38     552  1123.6     560 1124.33   564.1 1125.75   566.7 1127.35
#Mann= 6 ,-1,0
       0      .1       0    66.3    .045       0     102     .05       0
  167.14     .07       0  267.14     .06       0  367.14      .1       0
Bank Sta=66.3,102
XS Rating Curve= 0 ,0
Exp/Cntr=0.3,0.1

Type RM Length L Ch R = 1 ,5362    ,48.3,48.1,47.9
XS GIS Cut Line= 4
2168808.09239004753764.0458650662168814.69106119753902.617959234
2168887.27644385754173.1634764192168868.58020892754349.128040442
#Sta/Elev= 30
       0  1105.4    37.2 1095.38    57.2 1092.18    77.2 1087.44    93.2 1080.78
   106.2 1077.15   121.3 1074.74   141.4 1073.06   159.9  1069.5   175.3 1067.61
   228.4  1065.2     240 1063.02   246.5 1061.47   253.2 1061.13   265.6 1061.29
  272.23 1063.08     278 1064.54   286.3 1065.17     365 1067.22   373.3 1067.18
   385.7 1065.23   389.9 1065.53   413.1 1070.74   422.9 1074.41   434.9 1077.49
   479.2 1084.85   495.3 1086.47   535.5 1092.89   571.7 1100.39   595.8 1107.04
#Mann= 5 ,-1,0
       0      .1       0  238.73     .07       0     240    .045       0
  272.23     .07       0  438.84      .1       0
Bank Sta=240,272.23
XS Rating Curve= 0 ,0
Exp/Cntr(USF)=0,0
Exp/Cntr=0.3,0.1

Type RM Length L Ch R = 1 ,5314    ,99,106.5,113.1
XS GIS Cut Line= 4
2168762.45158124753775.0436503172168769.05025239753913.615744485
2168831.73762833754152.2676844412168822.93940013754360.125825693
#Sta/Elev= 30
       0 1124.65    18.2 1116.45    34.2 1108.25    46.7 1104.47    62.2 1096.32
    94.2 1089.05   150.7 1068.43   163.1 1066.52   183.8 1066.89     192 1064.61
   233.4 1064.55   240.3 1063.08   245.8 1060.93   249.9 1060.31   274.8 1059.87
   278.9 1060.64  282.28 1063.01   287.2 1064.62   303.7 1064.59   320.2    1066
   345.1 1066.94   361.6 1066.36   365.7 1067.71     374 1072.19   378.1 1073.34
   386.4 1074.01   406.4 1077.71   499.8 1088.96   570.6 1100.66   593.5 1105.13
#Mann= 6 ,-1,0
       0      .1       0  228.73     .06       0   240.3    .045       0
  282.28     .06       0  328.73     .05       0  525.48      .1       0
Bank Sta=240.3,282.28
XS Rating Curve= 0 ,0
Exp/Cntr(USF)=0,0
Exp/Cntr=0.3,0.1

Type RM Length L Ch R = 1 ,5208    ,267.6,275.9,273.5
XS GIS Cut Line= 3
2168716.79893358753753.4023288632168716.10299531753834.114054957
2168641.50069453754403.705302547
#Sta/Elev= 30
       0 1145.37    19.3 1136.49      52 1125.58    67.8 1117.93    75.8 1110.22
    79.8 1108.17    95.9 1106.67     108 1101.44   124.1 1091.98   149.3  1074.9
   160.5 1069.71   168.5 1068.03   176.6 1064.89   236.8 1063.93   253.71061.545
     265 1059.91   273.4 1060.46  276.35 1061.59   281.5 1063.23   305.7 1065.68
   321.8  1064.4   329.9 1066.13     346 1066.62   362.2 1064.54     383  1071.2
   535.6 1091.67   604.2 1104.33   620.3 1109.28   644.6 1119.35   655.2 1120.95
#Mann= 6 ,-1,0
       0      .1       0  150.71     .07       0   253.7    .045       0
  276.35     .07       0  350.71     .05       0  650.71      .1       0
Bank Sta=253.7,276.35
XS Rating Curve= 0 ,0
Exp/Cntr=0.3,0.1

Type RM Length L Ch R = 1 ,4932    ,307.8,312.3,312.7
XS GIS Cut Line= 3
2168531.56642943753725.5712974192168451.88165668753997.109031976
2168337.58665668754379.957031976
#Sta/Elev= 30
       0 1147.57     8.9  1143.4    24.6 1141.47    40.5 1136.62    66.3  1124.8
    99.6 1106.08   116.3 1095.71   137.2  1086.4     158 1072.83   170.5 1066.73
   178.8  1064.5   187.2 1063.89   228.9 1063.23   253.9 1061.68   266.4 1059.45
   274.7 1059.96     279 1061.69     283 1063.22   308.1 1067.67   349.9 1068.98
   430.7  1076.7   472.5  1081.4   575.3 1096.99   587.8 1102.27   600.3 1105.48
   617.1 1111.53   658.4 1128.18   668.6  1131.7   679.6 1137.45   682.5 1138.14
#Mann= 6 ,-1,0
       0      .1       0      80     .07       0   253.9    .045       0
     279     .07       0  282.99     .05       0  592.99      .1       0
#XS Ineff= 2 , 0
                          338.89          1075.2
Permanent Ineff=
       F       F
Bank Sta=253.9,279
XS Rating Curve= 0 ,0
Exp/Cntr=0.3,0.1

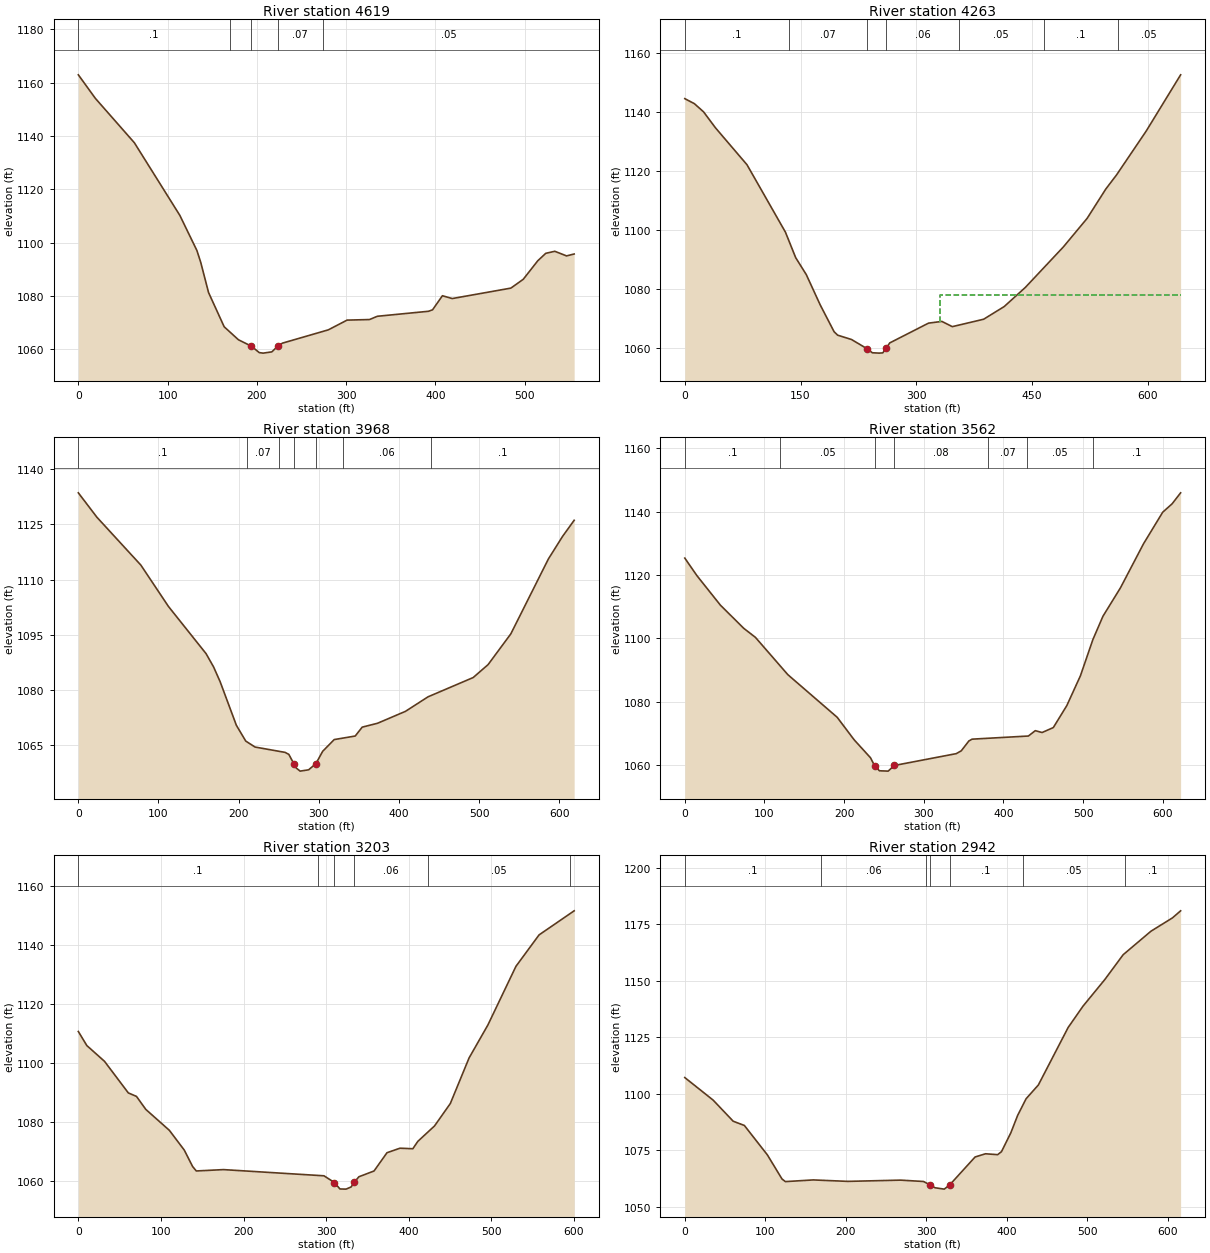
Type RM Length L Ch R = 1 ,4619    ,354.2,356.2,356
XS GIS Cut Line= 3
2168300.57526268753651.6930723782168210.34287849753856.302904073
2168069.54657466754156.875803513
#Sta/Elev= 30
       0 1162.93    19.1 1154.09    62.8 1137.43   113.7  1110.2   132.8 1097.03
   137.1  1092.6   145.9 1081.22   163.4 1068.37   179.4 1063.49     194 1061.07
   202.7 1058.67   207.1 1058.48   216.8 1058.95  223.18 1061.02   228.7 1062.23
   280.1 1067.22   301.1 1070.87   326.2 1071.08     335 1072.31   392.4 1074.19
   396.9 1074.75   407.9 1080.02   418.9 1078.96   484.6 1082.88   498.5  1086.2
   514.7 1093.13   523.7 1095.94   533.8  1096.7     547 1094.97   555.5 1095.69
#Mann= 5 ,-1,0
       0      .1       0     170     .07       0     194    .045       0
  223.18     .07       0  273.62     .05       0
Bank Sta=194,223.18
XS Rating Curve= 0 ,0
Exp/Cntr=0.3,0.1

Type RM Length L Ch R = 1 ,4263    ,293.6,295.6,295.9
XS GIS Cut Line= 4
2168007.72618517753490.2539858772167957.82398856753582.665461084
2167785.01452992753916.2708865842167717.55415302754063.205132164
#Sta/Elev= 30
       0 1144.49    12.4 1142.79    24.3 1140.03    39.7 1134.63    80.6 1122.12
   130.4 1099.31   143.7 1090.67   157.4 1084.95   175.4 1074.73   193.4 1065.64
     198 1064.46     216 1062.99   235.7 1059.94     243  1058.5     252 1058.38
   256.5 1058.47  260.83 1059.95   265.5 1061.83   315.8 1068.53   333.1 1069.11
   346.6 1067.34   387.2 1069.85   413.8 1074.13   441.2 1080.61   490.5 1094.32
   521.3 1103.99   545.4 1113.88   559.4 1118.69   597.8 1133.52   642.4 1152.55
#Mann= 7 ,-1,0
       0      .1       0  135.02     .07       0   235.7    .045       0
  260.83     .06       0  355.02     .05       0  465.02      .1       0
  560.73     .05       0
#XS Ineff= 2 , 0
                          330.27         1077.96
Permanent Ineff=
       F       F
Bank Sta=235.7,260.83
XS Rating Curve= 0 ,0
Exp/Cntr=0.3,0.1

Type RM Length L Ch R = 1 ,3968    ,398.9,405.1,409
XS GIS Cut Line= 2
2167783.69990778753329.4077785722167459.68930335753856.495451978
#Sta/Elev= 30
       0 1133.56    23.2 1126.93      78 1113.94   112.4 1102.72   159.4 1089.89
   168.8 1086.27   176.9  1082.3   197.2 1070.44   208.9 1066.15   220.5 1064.53
     258 1063.08   262.7 1062.53   268.9 1060.01   272.1  1058.8   276.8 1057.99
   287.4 1058.35  296.47 1060.03   304.9 1063.37   319.3 1066.56   345.5 1067.52
   354.2 1069.93   373.4 1070.99   408.2 1074.22   436.4 1078.17   492.7  1083.4
   511.3 1086.91   539.7 1095.27   586.6 1115.62   604.3 1121.75   618.7  1126.1
#Mann= 7 ,-1,0
       0      .1       0     210     .07       0     250     .08       0
   268.9    .045       0  296.47     .08       0     330     .06       0
     440      .1       0
Bank Sta=268.9,296.47
XS Rating Curve= 0 ,0
Exp/Cntr=0.3,0.1

Type RM Length L Ch R = 1 ,3562    ,360.7,359.3,355.9
XS GIS Cut Line= 4
2167543.64285073753127.5833061492167219.27857275753413.689233391
2167141.09846472753489.3742315862167081.57520675753544.430934927
#Sta/Elev= 30
       0  1125.3    15.3 1119.74    44.7 1110.45      74 1103.14    88.6  1100.3
   129.4  1088.5   191.3 1075.06   212.6 1067.95   233.1 1062.29   238.2  1059.8
   244.3 1058.18   255.3 1058.07  262.96 1059.85   340.8 1063.59   347.1 1064.49
   356.6 1067.59   360.7 1068.16   431.3 1069.15     440 1070.84   448.5 1070.25
   462.6 1071.82   479.6 1078.78   496.6 1088.15   512.3 1099.61   524.9 1106.95
   546.9 1115.93   575.8 1129.81   599.9 1139.78   611.7 1142.43   622.4  1145.9
#Mann= 7 ,-1,0
       0      .1       0     120     .05       0   238.2    .045       0
  262.96     .08       0     380     .07       0     430     .05       0
  512.51      .1       0
Bank Sta=238.2,262.96
XS Rating Curve= 0 ,0
Exp/Cntr=0.3,0.1

Type RM Length L Ch R = 1 ,3203    ,254.1,260.9,263.2
XS GIS Cut Line= 4
2167225.93847147752866.910450038     2167045.037      753134.242
2166946.65045751753250.9314692332166858.34615898753339.235767765
#Sta/Elev= 30
       0 1110.78    10.3 1106.01    31.7 1100.66    60.5 1089.95    70.4 1088.76
    81.7 1084.35   110.2 1077.26   128.3 1070.54   138.3 1065.01   142.8 1063.47
   175.7 1063.93   297.4 1061.83   310.1 1059.55   316.7 1057.37   324.1 1057.31
   330.3 1058.05     334 1059.61   339.7 1061.51     358 1063.46   373.7 1069.66
   389.4 1071.19     405 1071.01     411  1073.5   431.3 1078.76   450.4 1086.36
   473.1 1101.82   495.9 1113.01   529.8 1132.87   557.8 1143.54   600.3 1151.71
#Mann= 6 ,-1,0
       0      .1       0     290     .06       0   310.1    .045       0
     334     .06       0  422.79     .05       0  595.42      .1       0
Bank Sta=310.1,334
XS Rating Curve= 0 ,0
Exp/Cntr=0.3,0.1

Type RM Length L Ch R = 1 ,2942    ,192.5,209.8,227.1
XS GIS Cut Line= 4
2167102.24850777 752780.551285592167068.36430019 752801.08716897
2166690.50404601753092.6967129582166616.57486585753158.411539772
#Sta/Elev= 30
       0 1107.17    35.2 1097.19    60.1 1087.85      74 1085.97   102.6 1072.93
   120.7 1062.29   124.9 1061.12   159.6 1061.86   202.4 1061.22     268 1061.77
   296.5 1061.17     305 1059.57   310.7  1058.4   322.2 1057.79  328.81 1059.59
   360.6 1072.03   373.5 1073.44   388.5 1073.04   393.3 1074.37   404.9  1082.7
   413.4 1090.43   423.9 1097.81   439.1 1103.88   476.1 1129.33   494.6  1138.8
   521.7 1150.58   544.4 1161.54   578.9 1171.94   605.7 1177.87   615.8 1180.98
#Mann= 7 ,-1,0
       0      .1       0  169.62     .06       0  299.62      .1       0
     305    .045       0  328.81      .1       0  419.62     .05       0
  546.92      .1       0
Bank Sta=305,328.81
XS Rating Curve= 0 ,0
Exp/Cntr=0.3,0.1