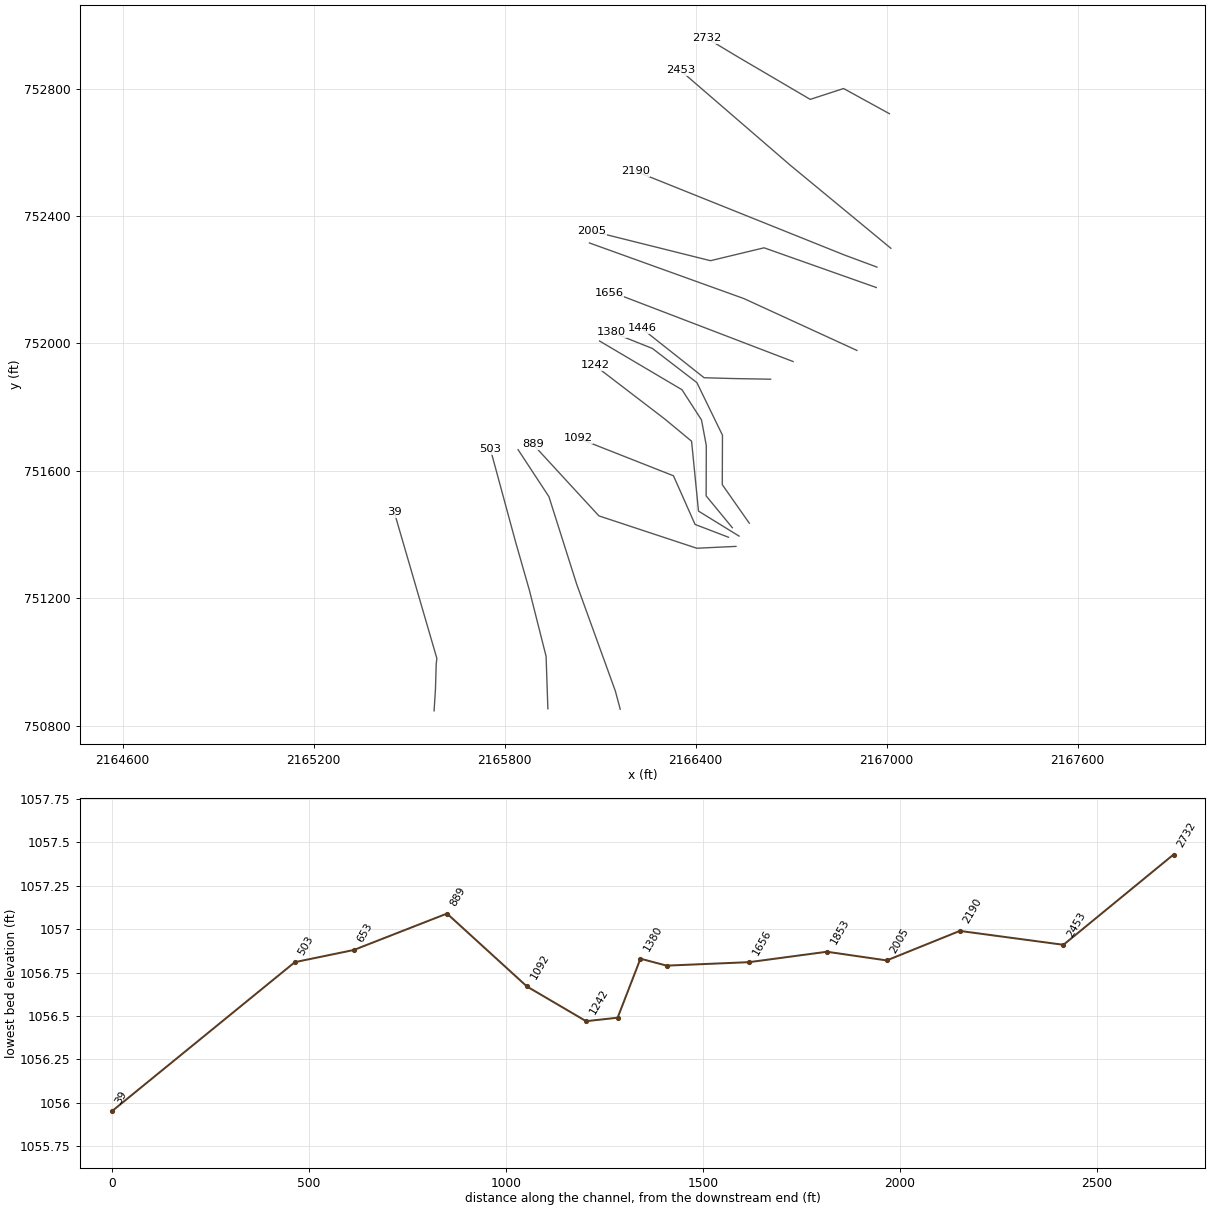
HEC-RAS study HACKERSCK.prj: HACKERSCK

--- HACKERSCK.g01 (geometry) --- (continued)

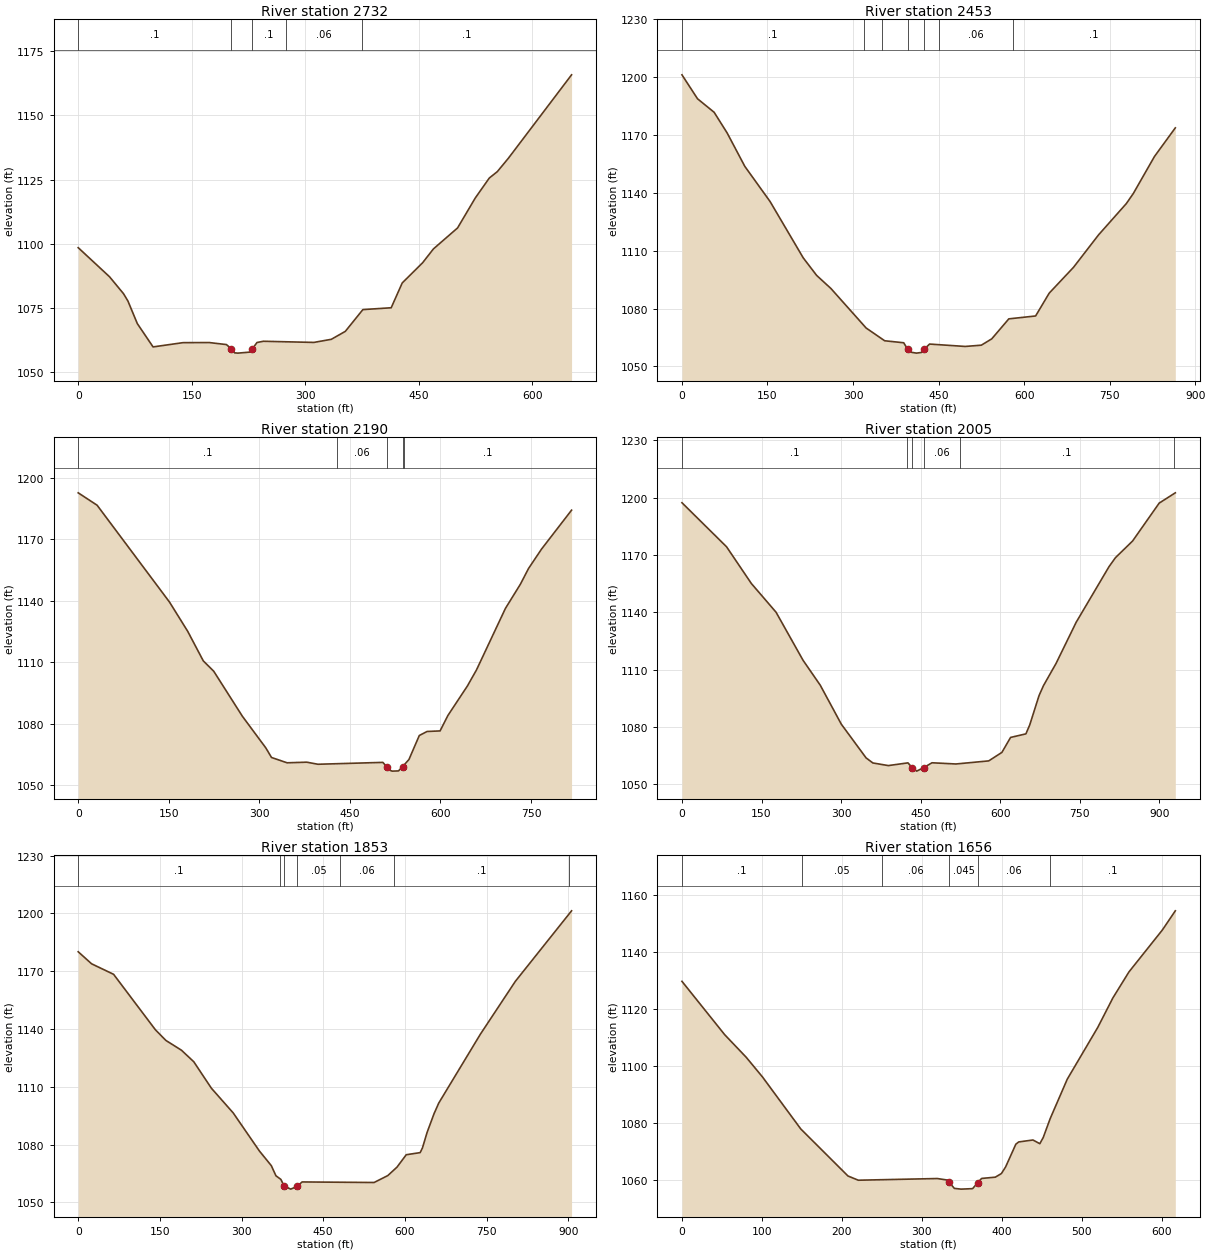
Type RM Length L Ch R = 1 ,2732    ,294.4,279.3,254.8
XS GIS Cut Line= 5
2167008.59461162752721.5722285242166864.70994472752800.584039827
2166759.91533183752766.4842054752166531.35094982 752900.68620336
2166435.02494343752958.587619238
#Sta/Elev= 30
       0  1098.5    41.3  1087.2    59.8  1080.6    65.7 1077.72    78.1 1068.93
    98.9 1059.85   138.5 1061.51   173.1 1061.55   195.8 1060.76   202.2 1059.18
   206.8 1057.53     211 1057.43   227.6 1057.85   230.2 1059.15   236.2 1061.56
   244.6 1062.05   311.3  1061.6   334.4 1062.81   352.9 1065.91   376.1 1074.38
   413.5  1075.1   428.1 1084.77     455 1092.62   469.3 1098.02   501.2 1106.19
   524.5 1117.81   543.1 1125.62   553.7 1128.11   568.3 1133.32   651.8 1165.82
#Mann= 5 ,-1,0
       0      .1       0   202.2    .045       0   230.2      .1       0
  274.15     .06       0  374.35      .1       0
Bank Sta=202.2,230.2
XS Rating Curve= 0 ,0
Exp/Cntr=0.3,0.1

Type RM Length L Ch R = 1 ,2453    ,254,263,262.7
XS GIS Cut Line= 3
     2167013.265      752298.841      2166697.11      752559.851
     2166352.482       752857.27
#Sta/Elev= 30
       0 1201.17    27.3 1188.76    56.4 1181.76    79.2 1171.06   110.3 1153.69
   154.5 1135.51   212.7 1106.29   236.1 1097.23   261.3 1090.39     323 1069.93
   355.5 1063.32   388.9 1062.28   395.6 1058.98   399.5 1057.49   411.2 1056.91
   420.1 1057.27  424.66 1058.93   434.3 1061.61   496.7 1060.37     525 1061.03
   543.3 1064.31   573.2 1074.67   620.2 1076.17   644.1 1088.02   686.7  1101.4
   730.4 1118.14   779.3 1134.43   791.6 1139.68   828.6 1158.82   865.2 1173.68
#Mann= 7 ,-1,0
       0      .1       0     320     .07       0     350      .1       0
   395.6    .045       0  424.66      .1       0  449.98     .06       0
  579.98      .1       0
Bank Sta=395.6,424.66
XS Rating Curve= 0 ,0
Exp/Cntr=0.3,0.1

Type RM Length L Ch R = 1 ,2190    ,174.3,185.4,195.6
XS GIS Cut Line= 3
      2166969.54      752239.8042166867.45239481752277.690091749
2166210.05637795752541.405576439
#Sta/Elev= 30
       0 1192.65    31.3 1186.61   151.2 1139.41   181.4 1125.13   207.2 1110.73
   224.5 1105.68   271.9 1083.75   310.7 1068.34   320.2 1063.64     346 1061.05
   378.6 1061.35   397.1 1060.34   504.6 1061.25   510.9 1059.15     514 1057.65
   520.1 1056.99   530.5 1057.09   537.3 1059.17   547.8 1062.63     565 1074.36
   577.9 1076.32   599.4 1076.59   612.4 1084.13   644.7 1098.51   659.8 1106.37
   707.7 1136.34   732.4 1148.08     746  1155.8   767.5 1165.24   817.2  1184.2
#Mann= 5 ,-1,0
       0      .1       0  428.89     .06       0   510.9    .045       0
   537.3     .06       0  538.89      .1       0
Bank Sta=510.9,537.3
XS Rating Curve= 0 ,0
Exp/Cntr=0.3,0.1

Type RM Length L Ch R = 1 ,2005    ,162.7,151.6,141.5
XS GIS Cut Line= 4
2166967.45169941752175.6630118012166614.93030756752300.367099839
2166446.59781155 752259.89371282     2166074.855      752352.715
#Sta/Elev= 30
       0 1197.35    84.1 1174.29   130.8 1155.08   177.4 1140.03   228.3 1114.87
   260.8 1101.79   300.5 1081.38   347.2 1063.74   359.9  1061.1   389.1 1059.72
   426.1 1061.15  433.84 1058.69   442.6 1056.82     456 1058.68   471.4 1061.19
   516.6 1060.56   578.4 1062.18   603.2 1066.62   619.6 1074.46   648.5 1076.33
   655.7 1081.01   673.2 1096.31   681.5 1101.53   705.2 1113.13   743.3 1134.77
   805.2 1163.88   817.3 1168.57   849.6  1177.3   899.8 1197.16   930.2 1202.54
#Mann= 6 ,-1,0
       0      .1       0  423.93     .06       0  433.84    .045       0
     456     .06       0  523.93      .1       0  927.06     .05       0
Bank Sta=433.84,456
XS Rating Curve= 0 ,0
Exp/Cntr=0.3,0.1

Type RM Length L Ch R = 1 ,1853    ,191.9,197.4,202.4
XS GIS Cut Line= 3
     2166906.536      751978.093     2166551.418      752140.999
     2166066.449      752315.579
#Sta/Elev= 30
       0 1180.07    24.6 1173.81      65 1168.36   141.7  1139.6     161 1134.05
   189.7 1128.95   212.3 1122.97   244.6 1109.24   284.7 1096.41   332.9 1076.62
   354.7 1069.04   363.1 1063.82   372.2 1061.92   378.2 1058.46   390.3 1056.87
   402.7 1058.36   402.7 1058.45   411.2  1060.6   543.4 1060.31   568.5 1063.88
   585.5 1068.29   602.5 1074.73     628 1075.81   632.2 1078.23   640.7 1086.24
   653.5 1095.99   662.2 1101.55   738.5 1137.22   802.9 1164.73   906.1 1201.31
#Mann= 7 ,-1,0
       0      .1       0     370     .05       0   378.2    .045       0
   402.7     .05       0   480.7     .06       0   580.7      .1       0
   900.7     .05       0
Bank Sta=378.2,402.7
XS Rating Curve= 0 ,0
Exp/Cntr=0.3,0.1

Type RM Length L Ch R = 1 ,1656    ,199.9,209.3,216.7
XS GIS Cut Line= 3
2166706.08031143751943.2178062042166177.67775869752145.584741298
2166128.64903163752159.793930848
#Sta/Elev= 30
       0 1129.77    53.4 1111.05    80.4 1103.09   100.6 1096.23   148.6 1077.93
   207.6 1061.42   220.5 1059.94   319.2 1060.53   331.3 1060.02   334.4 1059.14
   340.6 1057.07     349 1056.81   363.4 1056.98  370.01 1059.13   374.7 1060.56
   391.8 1061.01   399.4 1062.27   404.7  1064.6   417.5 1072.59   421.1 1073.38
   438.9 1074.06   447.5 1072.76   451.8 1074.98   460.4 1081.55   481.8 1095.42
     520 1113.63   538.8 1123.93   558.9 1133.07   600.7  1147.8   616.9 1154.53
#Mann= 6 ,-1,0
       0      .1       0     150     .05       0     250     .06       0
   334.4    .045       0  370.01     .06       0     460      .1       0
Bank Sta=334.4,370.01
XS Rating Curve= 0 ,0
Exp/Cntr=0.3,0.1

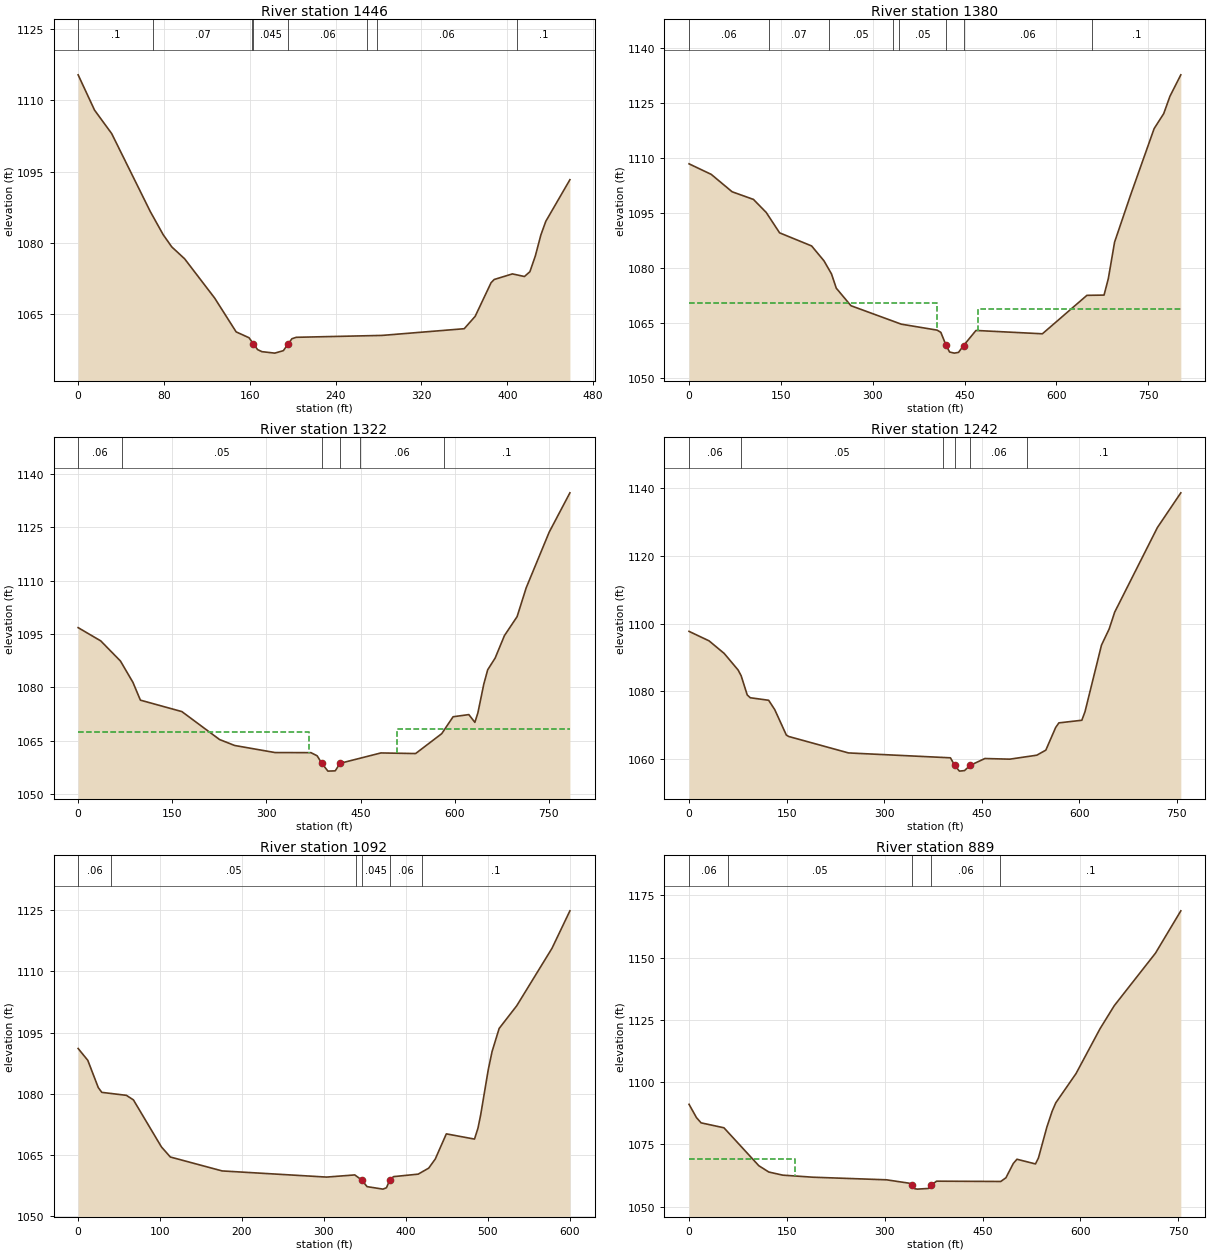
Type RM Length L Ch R = 1 ,1446    ,82.3,66.4,47
XS GIS Cut Line= 4
2166635.42359806751887.6713674352166513.07419518 751889.91030857
2166426.54848025751892.3545378052166230.90486186752047.116159052
#Sta/Elev= 30
       0 1115.38    15.3 1107.95    31.3    1103    67.3 1086.58    79.3 1081.72
    87.3 1079.15    99.3 1076.64   127.3 1068.37   147.3 1061.26   159.3 1060.03
   163.3 1058.75   167.3 1057.53   171.3  1057.1   183.3 1056.79   191.3 1057.31
  195.65  1058.7   199.3 1059.82   203.3 1060.12   283.4 1060.52   359.9 1061.93
   370.1 1064.54   384.9 1071.61   387.8 1072.29   404.8 1073.47     416 1072.92
   421.1 1073.93   426.2 1077.27   431.3 1081.64   435.9 1084.53   458.4  1093.3
#Mann= 8 ,-1,0
       0      .1       0      70     .07       0  162.37     .06       0
   163.3    .045       0  195.65     .06       0  268.93      .1       0
  278.93     .06       0  408.93      .1       0
Bank Sta=163.3,195.65
XS Rating Curve= 0 ,0
Exp/Cntr=0.3,0.1

Type RM Length L Ch R = 1 ,1380    ,58.1,57.9,55.8
XS GIS Cut Line= 6
2166568.56741834751435.4876858822166483.66823641751556.569121055
2166484.29863008751711.7767359512166403.90144489751877.037616621
2166264.32299837751984.2338635422166135.63862553 752035.52283334
#Sta/Elev= 30
       0 1108.43    36.3 1105.55    70.4 1100.81   105.2 1098.73   126.1 1095.17
   147.9 1089.62   200.2 1086.05   220.5 1081.97   232.7 1078.42   240.5 1074.53
   264.5 1069.75   346.8 1064.72   405.2  1063.1   411.3 1062.49   419.9 1058.93
   425.6 1057.13   433.3 1056.83   440.2 1057.03  448.34 1058.89   468.7 1063.01
   577.2  1062.1   649.9 1072.58   677.9 1072.65   684.9 1077.16   695.1 1087.09
   721.1 1099.86   759.7 1118.03   775.4 1122.13   785.5 1126.84   803.3 1132.69
#Mann= 8 ,-1,0
       0     .06       0     130     .07       0  227.88     .05       0
  333.09     .06       0  343.09     .05       0   419.9    .045       0
  448.34     .06       0  658.82      .1       0
#XS Ineff= 2 , 0
          404.63 1070.43  471.19         1068.82
Permanent Ineff=
       F       F
Bank Sta=419.9,448.34
XS Rating Curve= 0 ,0
Exp/Cntr=0.3,0.1

Type RM Length L Ch R = 1 ,1322    ,75.5,80,87.7
XS GIS Cut Line= 6
2166515.21031477751421.4027178572166432.96235153751521.356700994
 2166433.5106749751679.1695041122166418.41760332751759.791721551
2166357.00308686751854.7050651792166098.23258437752007.651226344
#Sta/Elev= 30
       0 1096.82      36  1093.1    67.4 1087.44    87.3 1081.44    99.2 1076.44
   165.3 1073.22   225.3 1065.37   249.3  1063.7   313.7 1061.71   370.9 1061.68
   380.8 1060.79   388.1  1058.7   397.9 1056.49   409.5 1056.57  417.39 1058.69
   482.3  1061.6   537.6 1061.43   579.2 1067.02   597.3 1071.77   622.4 1072.38
     632  1070.2   636.8 1072.86   646.2 1080.92   652.4 1084.96   664.3 1088.27
   679.1 1094.58   699.3 1099.92   713.7 1107.99   750.4 1123.66   783.4 1134.71
#Mann= 6 ,-1,0
       0     .06       0      70     .05       0   388.1    .045       0
  417.39     .05       0  449.28     .06       0  582.33      .1       0
#XS Ineff= 2 , 0
          368.04 1067.35  508.63         1068.23
Permanent Ineff=
       F       F
Bank Sta=388.1,417.39
XS Rating Curve= 0 ,0
Exp/Cntr=0.3,0.1

Type RM Length L Ch R = 1 ,1242    ,144.2,150.1,157.9
XS GIS Cut Line= 5
2166536.39943858751395.0245386362166409.01790588751473.467809712
2166387.23019523751692.9950601882166303.11464023 751762.63912186
2166083.32883521751930.870231872
#Sta/Elev= 30
       0 1097.71    30.8 1094.91    54.1 1091.19    75.4 1086.32    80.1 1084.63
    89.5 1078.94    94.2 1078.12   122.4 1077.38   131.8 1074.61   149.6 1067.12
   153.3 1066.69   245.2 1061.84   401.9  1060.4  408.59 1058.16   415.7 1056.47
   423.6 1056.63   432.2 1058.16   454.9 1060.19   493.2    1060   534.7 1061.17
   548.6 1062.66   563.7 1069.33   568.7 1070.71     604 1071.48   608.9 1074.04
   634.2 1093.65     646 1098.41   654.5 1103.38   720.1 1128.32   756.2 1138.59
#Mann= 6 ,-1,0
       0     .06       0      80     .05       0   390.2     .06       0
  408.59    .045       0   432.2     .06       0  519.41      .1       0
Bank Sta=408.59,432.2
XS Rating Curve= 0 ,0
Exp/Cntr(USF)=0,0
Exp/Cntr=0.3,0.1

Type RM Length L Ch R = 1 ,1092    ,201.6,202.8,203.7
XS GIS Cut Line= 5
2166503.15784711751391.3741508822166398.06515305751431.721654684
 2166356.4782719 751525.668418512166330.24869023751584.458860181
2166031.77414021751702.039743522
#Sta/Elev= 30
       0 1091.13    11.8 1088.23    24.6 1081.55    28.9 1080.38    58.9 1079.65
    67.5 1078.54   101.7 1067.02   112.6 1064.54   175.8 1061.13   303.4 1059.62
   337.8 1060.15   346.4  1058.9   352.8 1057.28   372.2 1056.67   376.5 1057.01
   380.5 1058.88   385.1 1059.73   415.2 1060.34   428.1 1061.82   436.1 1064.05
   449.6 1070.21     484 1068.93   488.3 1071.66   491.6 1074.93   500.8 1085.94
   505.5 1090.42   514.1 1096.04   535.6 1101.61   578.6 1115.67   600.5 1124.86
#Mann= 6 ,-1,0
       0     .06       0      40     .05       0  339.69     .06       0
   346.4    .045       0   380.5     .06       0  419.69      .1       0
Bank Sta=346.4,380.5
XS Rating Curve= 0 ,0
Exp/Cntr=0.3,0.1

Type RM Length L Ch R = 1 ,889     ,250.8,236.6,213.7
XS GIS Cut Line= 4
2166526.61508452751362.6865676572166403.60984156751356.868359766
2166096.06305407751458.5211082132165888.33532782751684.200193802
#Sta/Elev= 30
       0 1091.12    11.4 1085.77    18.5 1083.68    53.5  1081.7     107 1066.47
   122.3 1063.95   143.6  1062.7     190 1061.87   302.6 1060.83   337.4 1059.47
   341.6  1058.7   345.8 1057.26     350 1057.09   366.9 1057.36   371.1 1058.66
   379.4 1060.28   477.8 1060.16   485.7 1061.64     497 1067.38   502.6 1069.08
     531  1067.2   535.5 1069.54   548.5    1082   556.4 1088.24   562.1 1091.71
   593.2 1103.47     630 1121.47   651.8  1130.7     715 1151.79   753.8 1168.75
#Mann= 5 ,-1,0
       0     .06       0      60     .05       0   341.6    .045       0
   371.1     .06       0  477.05      .1       0
#XS Ineff= 2 , 0
          162.77 1069.35
Permanent Ineff=
       F       F
Bank Sta=341.6,371.1
XS Rating Curve= 0 ,0
Exp/Cntr=0.3,0.1

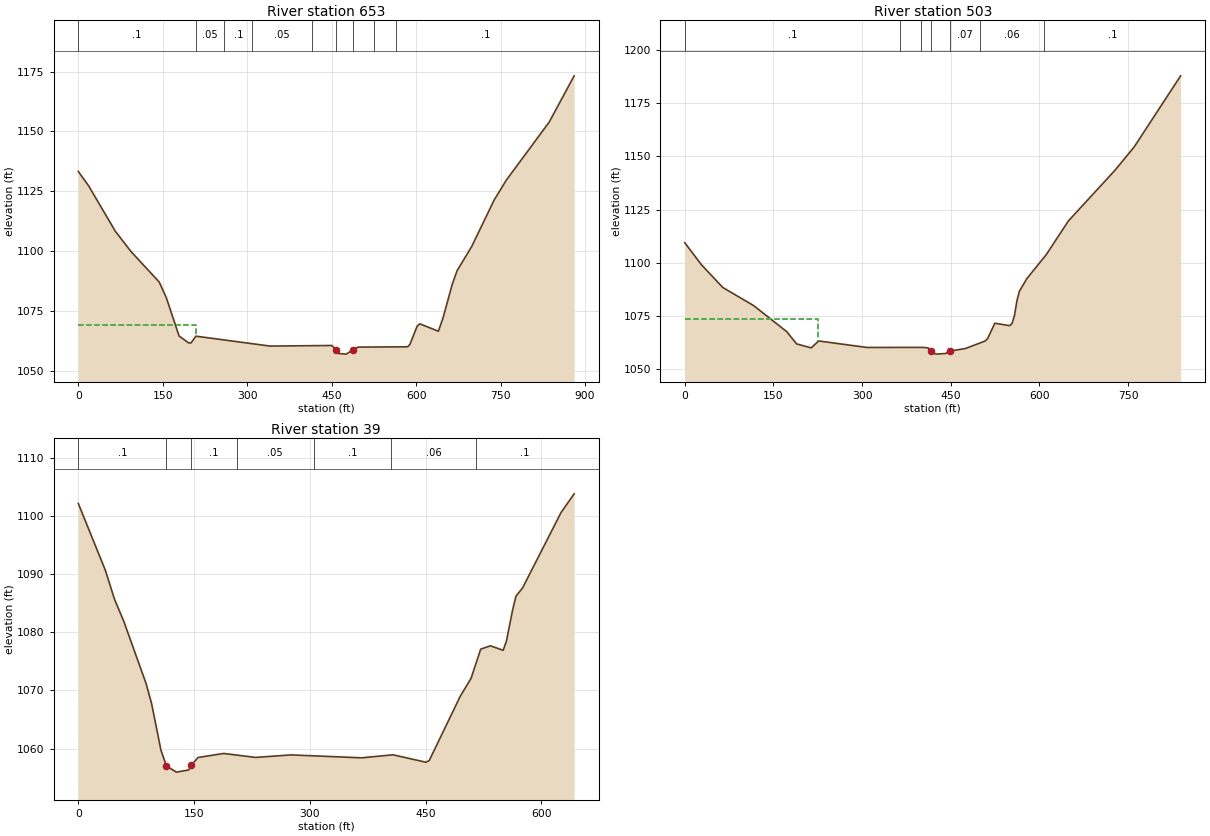
Type RM Length L Ch R = 1 ,653     ,149.5,149.4,148.3
XS GIS Cut Line= 5
2166163.11190805750851.3821874432166147.77456223750908.548658218
 2166026.5496443751243.2202309172165939.12238599751518.907888454
2165842.28917881 751666.38376385
#Sta/Elev= 30
       0 1133.24    18.4  1127.2    65.6  1108.3    93.9 1099.68   143.7 1087.02
   156.2 1080.56     179 1064.44     196 1061.55   200.3 1061.58   208.8 1064.39
   340.4 1060.25   450.4 1060.49   457.51058.676   463.2 1057.11   475.9 1056.88
   488.2  1058.7   496.9 1059.81     585 1059.94   589.2 1061.03   601.8 1068.54
   606.6 1069.55   639.6 1066.45     648 1072.12   663.9  1085.8   672.6 1091.63
     699 1101.96   738.9 1121.42   760.7 1129.76   836.3 1153.82   880.8 1173.22
#Mann= 9 ,-1,0
       0      .1       0  209.19     .05       0  259.19      .1       0
  309.19     .05       0  415.14     .07       0   457.5    .045       0
   488.2     .07       0  525.14     .06       0  565.14      .1       0
#XS Ineff= 2 , 0
          209.25 1069.19
Permanent Ineff=
       F       F
Bank Sta=457.5,488.2
XS Rating Curve= 0 ,0
Exp/Cntr(USF)=0,0
Exp/Cntr=0.3,0.1

Type RM Length L Ch R = 1 ,503     ,465.7,464.7,452.2
XS GIS Cut Line= 5
2165935.84032911750852.7764916082165930.26311245751017.304383108
2165877.78227004751224.9631248822165834.16461057 751377.62493302
     2165755.191      751668.386
#Sta/Elev= 30
       0 1109.31    28.4 1098.88    64.4 1088.22   116.5 1079.69   172.6 1067.38
   189.2 1061.63     214 1059.75   226.4 1063.02   307.9 1059.96     404 1059.98
   412.3 1059.68  416.99  1058.2   424.8 1056.81   441.4  1057.1   448.2 1058.24
   474.7 1059.45     508 1062.96   512.2 1064.09   524.6 1071.38   549.6 1070.24
   553.7 1071.27   557.8 1075.05     562 1082.04   566.1 1086.46   578.6 1092.36
   611.7 1103.77     649  1119.6   727.8 1143.49   760.5 1154.58   838.9 1188.03
#Mann= 7 ,-1,0
       0      .1       0  364.62     .05       0  398.81     .07       0
  416.99    .045       0   448.2     .07       0  498.81     .06       0
  607.58      .1       0
#XS Ineff= 2 , 0
          225.65 1073.14
Permanent Ineff=
       F       F
Bank Sta=416.99,448.2
XS Rating Curve= 0 ,0
Exp/Cntr(USF)=0,0
Exp/Cntr=0.3,0.1

Type RM Length L Ch R = 1 ,39      ,0,,0
XS GIS Cut Line= 5
2165578.44652558750846.3223900492165582.76798159750914.385322242
2165585.06261735 750992.31983769 2165587.0894376751011.077900515
2165453.55518516751469.455553852
#Sta/Elev= 30
       0 1102.15    34.9 1090.71      47 1085.65      59 1081.86    87.8 1071.19
      95 1067.71     107 1059.76   114.11057.018     127 1055.95     143 1056.32
   146.2  1057.1   155.1 1058.47   188.4 1059.16   229.7 1058.48   275.5 1058.91
   367.2 1058.41   407.8 1058.93   450.5 1057.65   454.7 1057.94   494.9    1069
   508.9 1072.08   521.4  1077.1   533.9 1077.68   550.5 1076.91   554.7 1078.47
     563    1084   567.2 1086.24   575.6 1087.62   625.5  1100.6   642.5 1103.82
#Mann= 7 ,-1,0
       0      .1       0   114.1    .045       0   146.2      .1       0
  205.04     .05       0  305.04      .1       0  405.04     .06       0
  515.04      .1       0
Bank Sta=114.1,146.2
XS Rating Curve= 0 ,0
Exp/Cntr(USF)=0,0
Exp/Cntr=0.3,0.1
LCMann Table=0

Chan Stop Cuts=-1
Use User Specified Reach Order=0
Composite Channel Slope=5